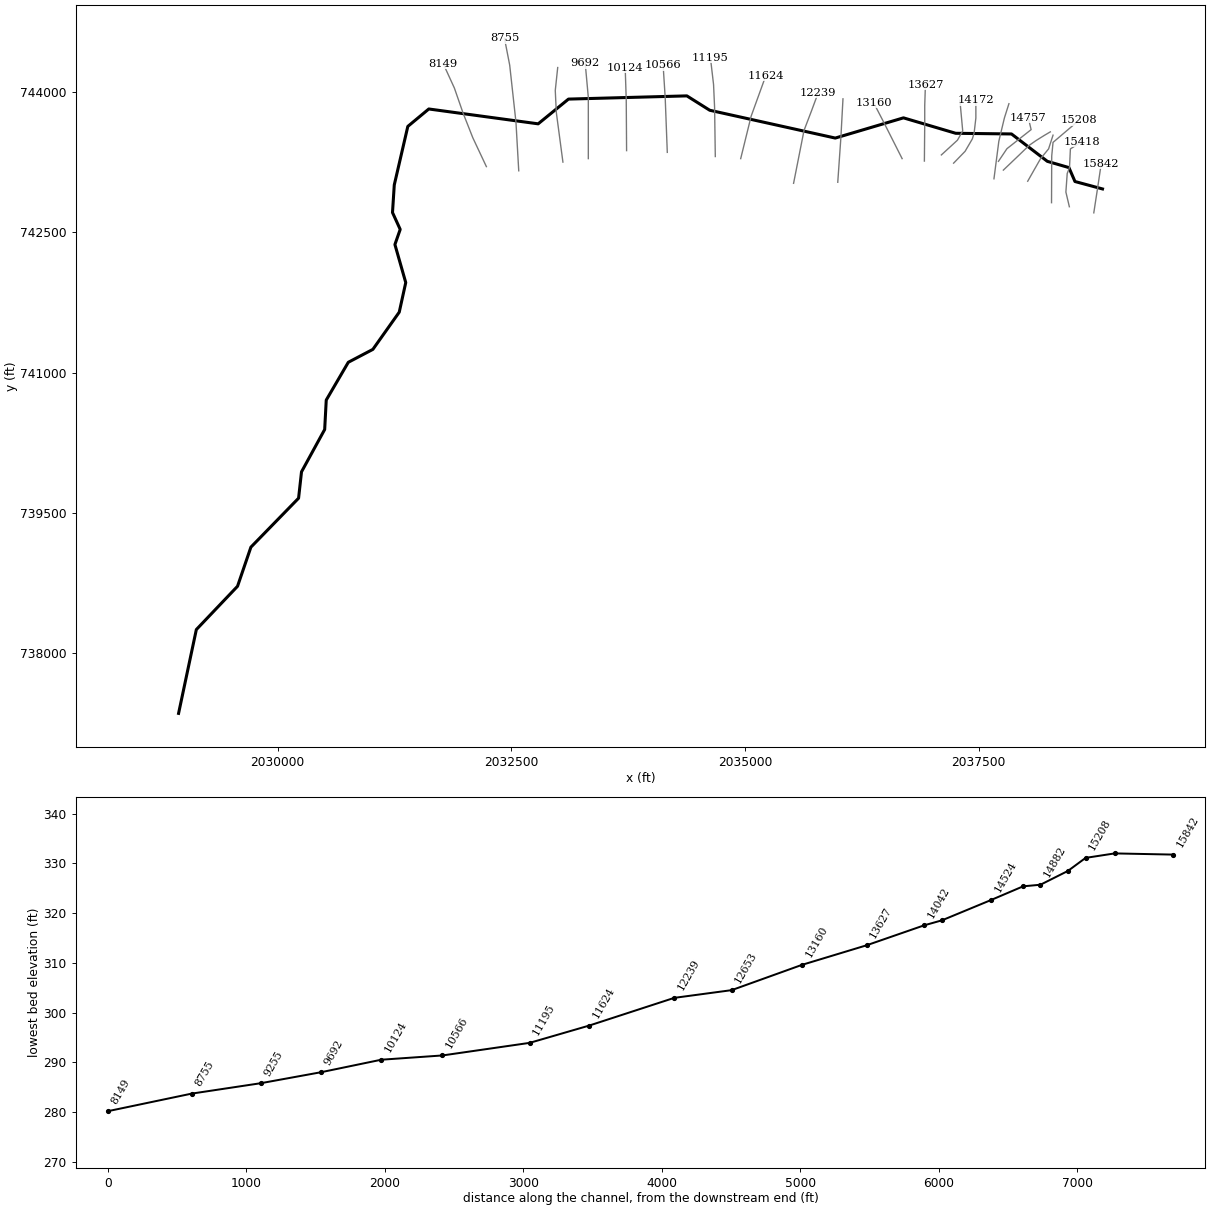
--- Bachelor_Branch_ADJ.prj (project) ---

Proj Title=Bachelor Branch (B28, S6) LDS Adjusted
Current Plan=p02
Default Exp/Contr=0.3,0.1
English Units
Geom File=g01
Flow File=f01
Flow File=f02
Plan File=p01
Plan File=p02
Y Axis Title=Elevation
X Axis Title(PF)=Main Channel Distance
X Axis Title(XS)=Station
BEGIN DESCRIPTION:
Bachelor Branch (B28, S6)
END DESCRIPTION:
DSS Export Rating Curves= 0
DSS Export Rating Curve Sorted= 0
DSS Export Volume Flow Curves= 0
DXF OffsetX= 0
DXF OffsetY= 0
DXF ScaleX= 1
DXF ScaleY= 10

--- Bachelor_Branch_ADJ.p02 (plan) ---

Plan Title=Floodway Run
Program Version=3.10
Short Identifier=Floodway
Geom File=g01
Flow File=f02
Subcritical Flow
K Sum by GR= 0
Std Step Tol= 0.01
Critical Tol= 0.01
Num of Std Step Trials= 20
Max Error Tol= 0.3
Flow Tol Ratio= 0.001
Split Flow NTrial= 30
Split Flow Tol= 0.02
Split Flow Ratio= 0.02
Log Output Level= 0
Friction Slope Method= 1
Unsteady Friction Slope Method= 2
Parabolic Critical Depth
Global Vel Dist= 0 , 0 , 0
Global Log Level= 0
CheckData=True
Encroach Param=-1 ,0,0, 2
Encroach River=Bachelor Branch
Encroach Reach=Reach-1
Encroach Node=15842
       1  4893.4 5074.05
Encroach Node=15418
       1    4980    5140
Encroach Node=15324
       1    4980    5140
Encroach Node=15208
       1    4980    5120
Encroach Node=15080
       1 4959.39 5023.69
Encroach Node=14882
       1 4852.04 5009.05
Encroach Node=14810
       1 4852.04 5009.05
Encroach Node=14757
       1 4852.49  5009.5
Encroach Node=14524
       1 4881.64 5038.54
Encroach Node=14172
       1  4905.8    5009
Encroach Node=14094
       1  4905.8    5009
Encroach Node=14042
       1  4905.8    5009
Encroach Node=13627
       1  4937.1 5058.78
Encroach Node=13160
       1 4943.21 5037.23
Encroach Node=12653
       1 4925.59 5085.14
Encroach Node=12239
       1 4911.75 5013.41
Encroach Node=11624
       1 4804.99  5001.1
Encroach Node=11195
       1  4900.8 5061.97
Encroach Node=10566
       1 4812.75 5037.99
Encroach Node=10124
       1 4896.91 5052.51
Encroach Node=9692
       1 4844.05 5037.77
Encroach Node=9255
       1 4882.04 5154.55
Encroach Node=8755
       1  4916.4 5099.59
Encroach Node=8149
       1  4993.4 5255.13
Encroach Node=7588
       1    4653 5061.03
Encroach Node=6924
       1 4737.88 5012.69
Encroach Node=6398
       1 4726.95  5027.2
Encroach Node=5747
       1  4815.9 5122.46
Encroach Node=5149
       1    4875 5296.69
Encroach Node=4482
       1  4790.7 5167.37
Encroach Node=3984
       1 4928.55 5346.95
Encroach Node=3349
       1  4991.1  5402.7
Encroach Node=2830
       1 4967.19  5318.4
Encroach Node=2377
       1 4851.23    5026
Encroach Node=2319
       1 4851.23    5026
Encroach Node=2232
       1 4851.23    5026
Encroach Node=1425
       1 4539.01  5005.1
Encroach Node=559
       4      .7
BEGIN DESCRIPTION:
Floodway Run
END DESCRIPTION:
Computation Interval=1HOUR
Output Interval=1HOUR
Run HTab= 0
Run UNet= 0
Run PostProcess= 0
UNET Theta= 1
UNET Theta Warmup= 1
UNET ZTol= 0.02
UNET ZSATol= 0.05
UNET MxIter= 20
UNET MaxInSteps= 1
UNET DtIC= 0
UNET DtMin= 0
UNET MaxCRTS= 20
UNET WFStab= 2
UNET SFStab= 1
UNET WFX= 1
UNET SFX= 1
UNET DSS MLevel= 4
UNET Convert EG Bridges=-1
UNET Use Existing IB Tables=-1
UNET Froude Reduction=False
UNET Froude Limit= 1
UNET Froude Power= 10
Instantaneous Interval=1HOUR
Write IC File= 0
Echo Input=False
Echo Output=False
Write Detailed= 0

--- Bachelor_Branch_ADJ.p01 (plan) ---

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Plan Title=100-yr future
Short Identifier=100 yr
Geom File=g01
Flow File=f01
Encroach Param=-1 ,0,0, 0
100-yr future

--- Bachelor_Branch_ADJ.f02 (steady flow) ---

Flow Title=Floodway
Number of Profiles=2
Profile Names=100-year,100-FW
River Rch & RM= Bachelor Branch ,Reach-1,15842
    1550    1550
River Rch & RM= Bachelor Branch ,Reach-1,11195
    1840    1840
River Rch & RM= Bachelor Branch ,Reach-1,7588
    2370    2370
River Rch & RM= Bachelor Branch ,Reach-1,5149
    2580    2580
Boundary for River Rch & Prof#=Bachelor Branch ,Reach-1,1
Up Type=0
Dn Type=3
Dn Slope=0.0035
Boundary for River Rch & Prof#=Bachelor Branch ,Reach-1,2
Up Type=0
Dn Type=3
Dn Slope=0.0035

--- Bachelor_Branch_ADJ.f01 (steady flow) ---

Flow Title=100-yr
Number of Profiles=2
Profile Names=100-year,100-yr future
River Rch & RM= Bachelor Branch ,Reach-1,15842
    1550    1650
River Rch & RM= Bachelor Branch ,Reach-1,11195
    1840    1890
River Rch & RM= Bachelor Branch ,Reach-1,7588
    2370    2480
River Rch & RM= Bachelor Branch ,Reach-1,5149
    2580    2730
Boundary for River Rch & Prof#=Bachelor Branch ,Reach-1,1
Up Type=0
Dn Type=3
Dn Slope=0.0035
Boundary for River Rch & Prof#=Bachelor Branch ,Reach-1,2
Up Type=0
Dn Type=3
Dn Slope=0.0035

--- Bachelor_Branch_ADJ.g01 (geometry) ---

Geom Title=Existing Conditions
Program Version=3.11

River Reach=Bachelor Branch ,Reach-1
Reach XY= 30
 2038827.0487962  742965.6682385 2038532.2458091  743045.3190456
 2038467.6551546  743194.4105563 2038236.7828152  743261.2812339
 2037852.8989255  743554.5342053 2037256.0228775  743561.7242782
  2036696.887212  743726.9759526 2035967.0098163  743510.5937601
 2034623.3662016  743808.4767784 2034378.8637241   743962.288337
 2033111.8508859   743927.847988 2032787.4775991  743662.9753041
 2031617.0857399  743821.9769152 2031392.5834651  743635.4750255
 2031247.6219963  743009.0786784 2031228.5818033  742713.1556799
 2031311.0826393  742532.4038484 2031254.4620656  742370.4622075
 2031370.4232406  741963.1280801 2031300.7125342  741646.0748675
 2031018.4596742  741247.6408303 2030755.5770105    741109.44943
 2030519.5746192  740704.7553294 2030502.8244495  740389.8121382
 2030254.8219365   739936.307543 2030223.4216184  739653.9846823
 2029713.1964484  739129.7993709 2029570.1449989  738710.9751271
 2029129.3105321  738247.1704275 2028939.1886056  737349.7813345

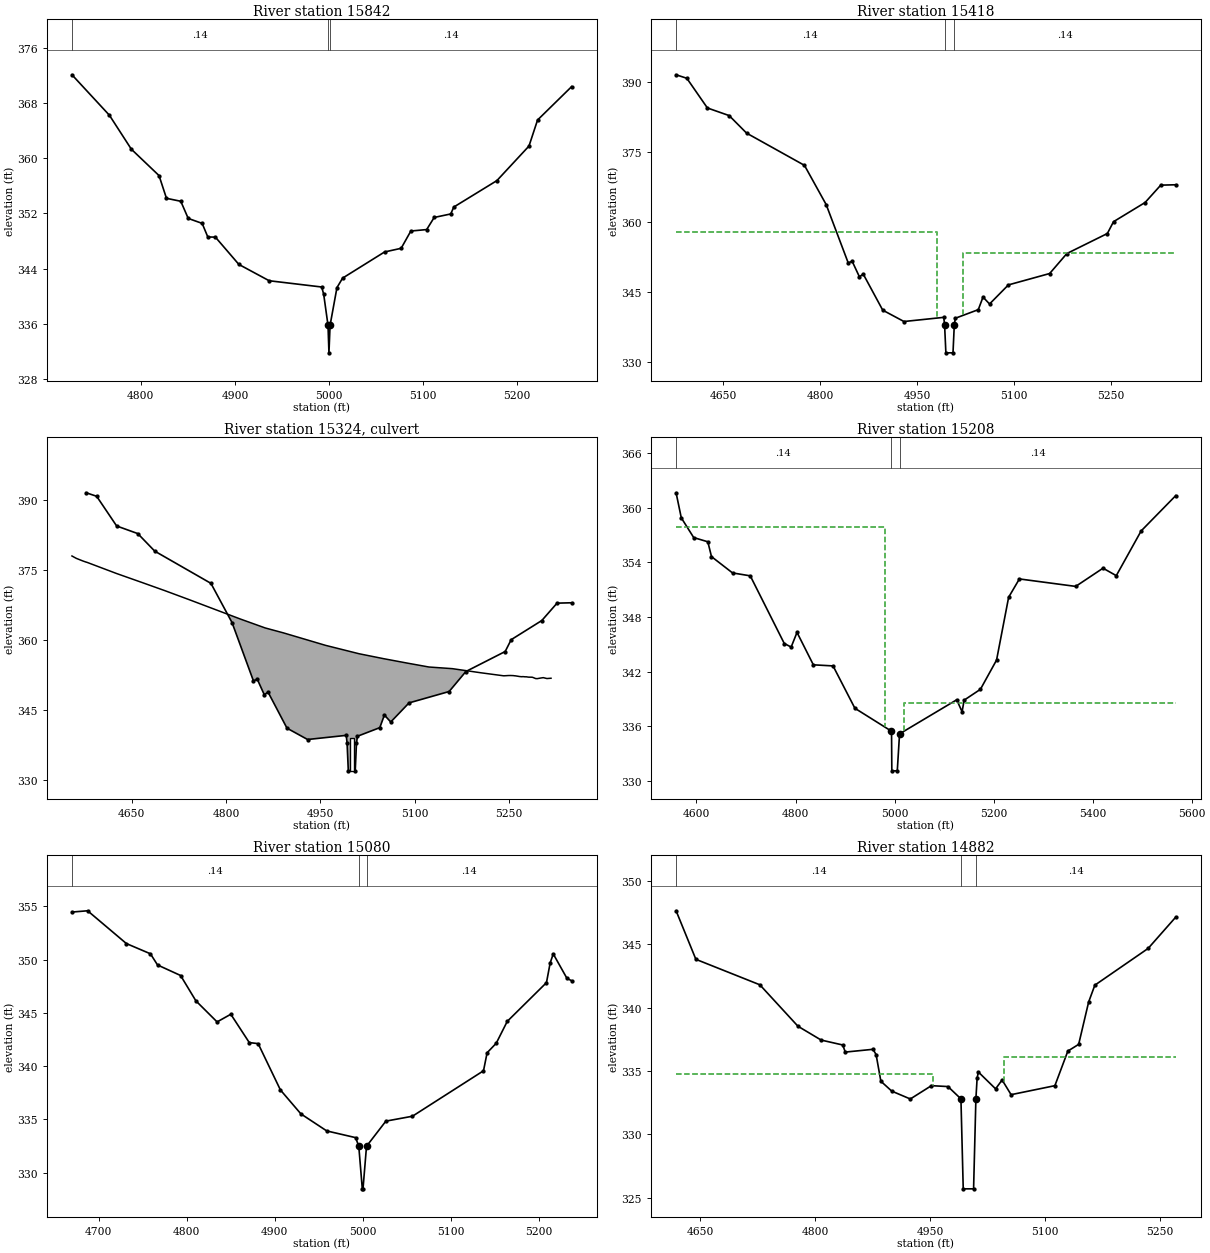
Type RM Length L Ch R = 1 ,15842   ,424.0043,424.0043,424.0043
BEGIN DESCRIPTION:
Bachelor Branch 25.0
END DESCRIPTION:
XS GIS Cut Line= 3
 2038733.7699749  742709.8297905 2038775.6704194  742983.2926918
 2038813.1608172  743234.7153593
#Sta/Elev= 30
  4726.9  372.14  4766.7  366.26    4790  361.33  4819.4   357.5  4827.3   354.2
  4842.5  353.77  4850.4  351.28  4865.2  350.56  4871.2  348.59  4879.3  348.56
  4904.2   344.6  4936.4  342.23  4992.2  341.32  4994.3  340.28  4998.9  335.76
  4999.9  331.76  5001.1  335.76  5008.4  341.23  5014.4  342.61    5059  346.41
  5076.6  346.94  5086.9  349.45  5103.7  349.66  5111.7  351.42  5129.3  351.93
  5132.5  352.93  5178.3  356.77  5212.4  361.79  5221.5  365.57  5257.7  370.42
#Mann= 3 ,-1 , 0
  4726.9     .14       0  4998.9     .05       0  5001.1     .14       0
Bank Sta=4998.9,5001.1
XS Rating Curve= 0
Exp/Cntr=0.5,0.3

Type RM Length L Ch R = 1 ,15418   ,210.0021,210.0021,210.0021
BEGIN DESCRIPTION:
NC Hwy 55-U
END DESCRIPTION:
XS GIS Cut Line= 6
 2038472.2071998  742775.1404834 2038435.0568057  742932.4821527
 2038449.2669565  743131.0542595 2038473.8672175  743194.2249297
  2038483.347318  743394.5370549 2038603.6985949  743471.7678743
#Sta/Elev= 30
  4577.5  391.56  4594.1  390.81  4625.9  384.45  4659.5  382.82  4686.5  379.06
  4775.9  372.16  4809.5  363.75  4843.5  351.28  4849.7   351.6  4860.8   348.3
  4866.8  348.86  4896.9  341.14  4929.7  338.71  4991.2   339.6  4992.5     338
  4994.5     332  5005.5     332  5007.5     338  5009.1  339.41  5044.6  341.25
  5051.9  343.95    5062  342.46  5091.1  346.55  5154.9  348.99  5181.5  353.27
  5244.1  357.56  5253.6  360.09  5302.4   364.2  5326.6  367.92  5349.8     368
#Mann= 3 ,-1 , 0
  4577.5     .14       0  4992.5     .05       0  5007.5     .14       0
#XS Ineff= 2 , 0
       0  4980.5  357.93  5020.5       0   353.4
Permanent Ineff=
       F       F
Bank Sta=4992.5,5007.5
XS Rating Curve= 0
Exp/Cntr=0.5,0.3

Type RM Length L Ch R = 2 ,15324   ,,,
Node Photo=N:\NC_flood\60273\Approximates\Survey\Photos\NCF_2001.jpg
BEGIN DESCRIPTION:
NC Hwy 55-TOR
Structure ID: NCF-2001
Approximate Survey Structure
END DESCRIPTION:
Bridge Culvert--1,0,-1,-1, 0
Deck Dist Width WeirC Skew NumUp NumDn MinLoCord MaxHiCord MaxSubmerge Is_Ogee
4,180,3,0, 45, 45, , , , 0, 1,1,,
  4554.8  4560.6  4562.1  4572.2  4577.7  4578.1  4625.9  4666.5  4702.1  4741.2
  4822.7  4862.2  4891.6  4958.3  5011.7  5050.5  5087.8  5122.8  5159.9  5205.6
  5241.4  5242.6    5249  5252.2    5257  5258.3  5260.2    5264  5266.4  5269.9
  5272.6  5275.6  5277.8  5281.2  5285.7  5287.2  5288.3  5292.7  5295.3  5298.8
  5304.5  5304.7  5310.5  5316.3    5317
  378.02  377.59  377.49  376.95  376.69  376.69  374.26  372.33  370.62  368.67
  364.52  362.61  361.54  358.88  357.08  356.03  355.09  354.24  353.89     353
  352.36  352.36  352.41  352.42   352.4  352.37  352.35  352.27  352.21  352.16
  352.18  352.14  352.14  352.07  352.06  352.05     352  351.76  351.75  351.84
  351.96  351.96  351.77  351.83  351.83
     312     312     312     312     312     312     312     312     312     312
     312     312     312     312     312     312     312     312     312     312
     312     312     312     312     312     312     312     312     312     312
     312     312     312     312     312     312     312     312     312     312
     312     312     312     312     312
  4554.8  4560.6  4562.1  4572.2  4577.7  4578.1  4625.9  4666.5  4702.1  4741.2
  4822.7  4862.2  4891.6  4958.3  5011.7  5050.5  5087.8  5122.8  5159.9  5205.6
  5241.4  5242.6    5249  5252.2    5257  5258.3  5260.2    5264  5266.4  5269.9
  5272.6  5275.6  5277.8  5281.2  5285.7  5287.2  5288.3  5292.7  5295.3  5298.8
  5304.5  5304.7  5310.5  5316.3    5317
  378.02  377.59  377.49  376.95  376.69  376.69  374.26  372.33  370.62  368.67
  364.52  362.61  361.54  358.88  357.08  356.03  355.09  354.24  353.89     353
  352.36  352.36  352.41  352.42   352.4  352.37  352.35  352.27  352.21  352.16
  352.18  352.14  352.14  352.07  352.06  352.05     352  351.76  351.75  351.84
  351.96  351.96  351.77  351.83  351.83
   311.1   311.1   311.1   311.1   311.1   311.1   311.1   311.1   311.1   311.1
   311.1   311.1   311.1   311.1   311.1   311.1   311.1   311.1   311.1   311.1
   311.1   311.1   311.1   311.1   311.1   311.1   311.1   311.1   311.1   311.1
   311.1   311.1   311.1   311.1   311.1   311.1   311.1   311.1   311.1   311.1
   311.1   311.1   311.1   311.1   311.1
Culvert=2,7,7,180,0.015,0.4,1,8,1,332,5000,331.1,5000,Culvert #1  , 0 ,4
Culvert Bottom n=0.015
BC Design=,, 0 ,, 0 ,,,,,,
BC HTab HWMax=391.56

Type RM Length L Ch R = 1 ,15208   ,128.0013,128.0013,128.0013
BEGIN DESCRIPTION:
NC Hwy 55 D
END DESCRIPTION:
XS GIS Cut Line= 4
 2038281.4751763  742818.3009413 2038283.5051978  743317.7962407
  2038297.565347  743464.2077941 2038573.5382749  743699.2302875
#Sta/Elev= 30
  4558.8  361.63  4569.3  358.88  4594.4  356.71  4622.9  356.25  4630.3  354.62
  4672.8  352.83  4708.6  352.51  4777.3  345.08  4791.2  344.69    4803   346.3
    4836  342.74  4875.8  342.62  4919.9  337.97  4992.1  335.51  4993.9  335.43
  4994.5   331.1  5005.5   331.1  5010.1  335.16  5125.5   338.9  5136.4  337.59
  5140.5  338.86  5173.4  340.05    5206  343.26  5230.4  350.16  5252.1  352.17
  5365.8  351.35    5421  353.35  5447.8  352.53    5498  357.44  5567.9  361.32
#Mann= 3 ,-1 , 0
  4558.8     .14       0  4992.1     .05       0  5010.1     .14       0
#XS Ineff= 2 , 0
       0    4980   357.9    5020       0   338.5
Permanent Ineff=
       F       F
Bank Sta=4992.1,5010.1
XS Rating Curve= 0
Exp/Cntr=0.5,0.3

Type RM Length L Ch R = 1 ,15080   ,198.002,198.002,198.002
BEGIN DESCRIPTION:
Bachelor Branch 24.0
END DESCRIPTION:
XS GIS Cut Line= 5
 2038026.5224713  743048.3033815 2038089.8131428  743159.9945665
 2038164.2739328  743290.3059491 2038249.9048413  743394.5570551
  2038297.565347  743541.6886161
#Sta/Elev= 30
  4669.5  354.47  4687.3  354.59  4731.4  351.51  4758.7  350.55  4766.8   349.5
    4793  348.51  4810.4  346.13  4834.5  344.15  4850.1  344.87  4871.1  342.21
  4881.2  342.11  4906.5  337.76  4929.8  335.51  4959.2  333.91    4992  333.28
  4995.6  332.47  4999.6  328.47  5000.4  328.47  5004.4  332.47  5026.4  334.83
  5056.6  335.29  5137.4  339.56  5141.5  341.25  5151.9  342.15  5164.4   344.2
    5209  347.84  5213.2  349.69  5216.7  350.54  5232.3  348.24  5237.6  348.02
#Mann= 3 ,-1 , 0
  4669.5     .14       0  4995.6     .05       0  5004.4     .14       0
Bank Sta=4995.6,5004.4
XS Rating Curve= 0
Exp/Cntr=0.5,0.3

Type RM Length L Ch R = 1 ,14882   ,125.0013,125.0013,125.0013
BEGIN DESCRIPTION:
Highfield Ave-U
END DESCRIPTION:
XS GIS Cut Line= 6
 2037765.9097064  743167.4446456 2037933.4414838  743327.5363441
 2038041.4126293  743431.7874501 2038115.8734193  743483.9080031
 2038205.2343674  743539.7585956 2038268.5250389  743576.9889906
#Sta/Elev= 30
  4618.9  347.64  4644.7  343.81  4728.1   341.8  4777.8  338.53    4808  337.44
  4836.2  337.05  4839.5  336.49  4875.7  336.71  4879.7  336.29  4885.9  334.19
  4900.1  333.41  4924.3  332.79  4951.8  333.84  4973.4  333.77  4990.3   332.8
  4993.3   325.7  5006.8   325.7  5009.8   332.8  5011.4  334.43    5013  334.92
  5035.5  333.59    5044  334.29  5055.7  333.13  5112.8  333.84  5129.7  336.57
  5143.8   337.1  5156.8  340.44  5164.9  341.77  5234.4  344.67  5270.4  347.14
#Mann= 3 ,-1 , 0
  4618.9     .14       0  4990.3     .05       0  5009.8     .14       0
#XS Ineff= 2 , 0
       0    4954  334.79    5046       0  336.14
Permanent Ineff=
       F       F
Bank Sta=4990.3,5009.8
XS Rating Curve= 0
Exp/Cntr=0.5,0.3

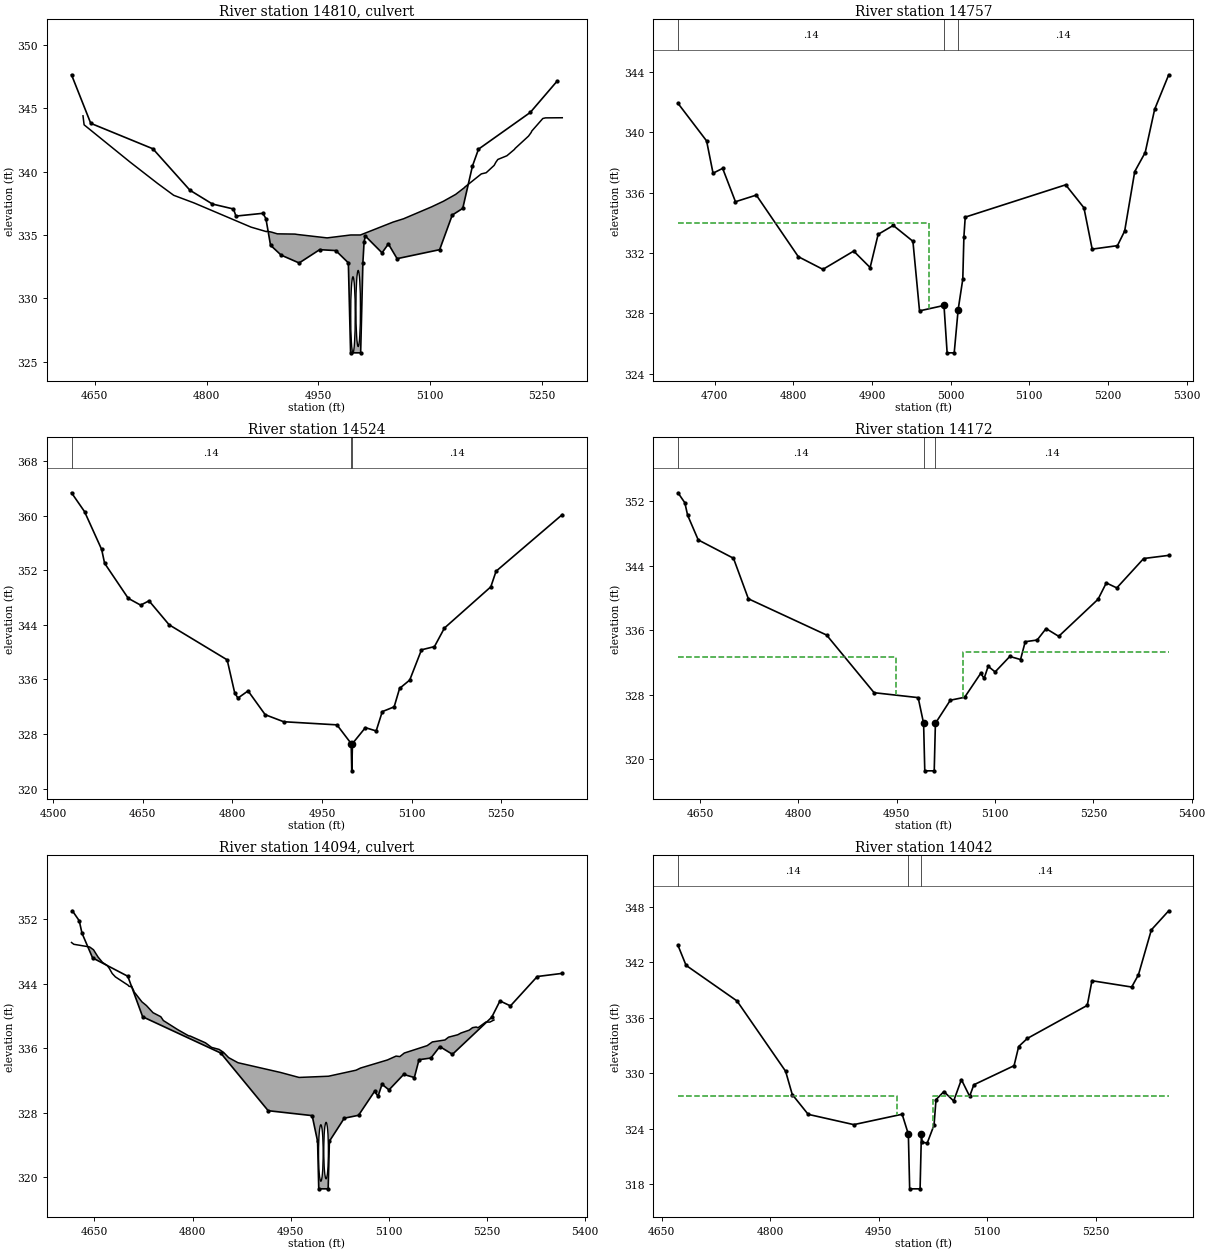
Type RM Length L Ch R = 2 ,14810   ,,,
Node Photo=N:\NC_flood\60273\Approximates\Survey\Photos\NCF_1067.jpg
BEGIN DESCRIPTION:
Highfield Ave-TOR
Structure ID: NCF-1067
Approximate Survey Structure
END DESCRIPTION:
Bridge Culvert--1,0,-1,-1, 0
Deck Dist Width WeirC Skew NumUp NumDn MinLoCord MaxHiCord MaxSubmerge Is_Ogee
39.5,65,3,0, 38, 38, , , , 0, 1,1,,
  4634.3  4635.8  4697.5  4734.5    4756  4783.2  4859.7  4880.6  4881.3  4887.6
    4895  4918.6  4921.8  4961.8  4993.5  5006.5  5050.4  5064.4    5102  5117.8
  5134.2  5146.1  5146.4  5168.7  5175.2  5185.7    5186  5188.2  5190.9    5203
  5213.3  5213.9    5232  5235.6  5236.4  5251.2  5254.8  5277.3
   344.4  343.69  340.75  339.06  338.13  337.53  335.62  335.26   335.3  335.22
  335.09  335.07  335.04  334.77     335     335  336.02  336.28  337.22  337.66
   338.2  338.74  338.77  339.82  339.91  340.48   340.5  340.74  340.96  341.25
  341.76  341.82   342.8  343.09   343.2  344.19  344.24  344.25
   305.7   305.7   305.7   305.7   305.7   305.7   305.7   305.7   305.7   305.7
   305.7   305.7   305.7   305.7   305.7   305.7   305.7   305.7   305.7   305.7
   305.7   305.7   305.7   305.7   305.7   305.7   305.7   305.7   305.7   305.7
   305.7   305.7   305.7   305.7   305.7   305.7   305.7   305.7
  4634.3  4635.8  4697.5  4734.5    4756  4783.2  4859.7  4880.6  4881.3  4887.6
    4895  4918.6  4921.8  4961.8  4993.5  5006.5  5050.4  5064.4    5102  5117.8
  5134.2  5146.1  5146.4  5168.7  5175.2  5185.7    5186  5188.2  5190.9    5203
  5213.3  5213.9    5232  5235.6  5236.4  5251.2  5254.8  5277.3
   344.4  343.69  340.75  339.06  338.13  337.53  335.62  335.26   335.3  335.22
  335.09  335.07  335.04  334.77     335     335  336.02  336.28  337.22  337.66
   338.2  338.74  338.77  339.82  339.91  340.48   340.5  340.74  340.96  341.25
  341.76  341.82   342.8  343.09   343.2  344.19  344.24  344.25
  305.38  305.38  305.38  305.38  305.38  305.38  305.38  305.38  305.38  305.38
  305.38  305.38  305.38  305.38  305.38  305.38  305.38  305.38  305.38  305.38
  305.38  305.38  305.38  305.38  305.38  305.38  305.38  305.38  305.38  305.38
  305.38  305.38  305.38  305.38  305.38  305.38  305.38  305.38
Culvert=1,6,,65,0.015,0.5,1,1,1,325.7,4996.5,325.38,4996.5,Culvert #1  , 0 ,39.5
Culvert Bottom n=0.015
Culvert=1,6,,65,0.015,0.5,1,1,3,326.2,5003.5,325.38,5003.5,Culvert #2  , 0 ,39.5
Culvert Bottom n=0.015
BC Design=,, 0 ,, 0 ,,,,,,
BC HTab HWMax=347.64

Type RM Length L Ch R = 1 ,14757   ,233.0024,233.0024,233.0024
BEGIN DESCRIPTION:
Highfield Avenue D
END DESCRIPTION:
XS GIS Cut Line= 4
 2037713.2291475  743261.1656399 2037804.2301129  743396.6570774
 2038063.0728591  743600.8992443 2038032.7425373   743728.300596
#Sta/Elev= 30
  4653.3  341.91  4689.7  339.42  4697.9  337.28  4710.1   337.6  4726.4  335.39
  4752.9  335.83  4806.3  331.75  4837.6  330.91  4876.7  332.12  4897.6  331.03
  4907.8  333.23    4927  333.82    4952  332.77  4960.4  328.16  4991.5  328.52
  4995.5  325.38  5004.5  325.38  5009.5  328.24  5015.4  330.26  5016.8  333.05
  5018.5  334.37  5146.2  336.51  5169.4  334.99  5179.9  332.25    5212  332.48
  5221.2  333.45    5234  337.39  5247.3  338.65  5259.3  341.51  5277.2   343.8
#Mann= 3 ,-1 , 0
  4653.3     .14       0  4991.5     .05       0  5009.5     .14       0
#XS Ineff= 2 , 0
       0    4973     334    5027       0     334
Permanent Ineff=
       F       F
Bank Sta=4991.5,5009.5
XS Rating Curve= 0
Exp/Cntr=0.5,0.3

Type RM Length L Ch R = 1 ,14524   ,352.0036,352.0036,352.0036
BEGIN DESCRIPTION:
Bachelor Branch 23.0
END DESCRIPTION:
XS GIS Cut Line= 4
 2037665.3786398   743074.363658 2037717.5091929   743476.457924
 2037777.0698248  743725.9105706 2037825.4703383  743878.5521901
#Sta/Elev= 30
  4530.5  363.37  4552.3  360.61    4581  355.06  4585.9  353.04  4625.5   347.9
  4646.3   346.9  4660.3  347.53    4694  344.02  4791.2  338.88  4803.8  334.05
  4809.2  333.27  4826.2  334.33  4854.9  330.84  4885.8  329.81  4975.1  329.35
  4998.9  326.61  4999.9  322.61  5001.1  326.61  5022.7  328.94  5040.8  328.46
    5051  331.29  5070.9  331.99    5080  334.69    5097  335.92  5116.7  340.35
  5138.4  340.82  5155.1  343.54  5232.8  349.58  5241.6  351.87  5352.5  360.17
#Mann= 3 ,-1 , 0
  4530.5     .14       0  4998.9     .05       0  5001.1     .14       0
Bank Sta=4998.9,5001.1
XS Rating Curve= 0
Exp/Cntr=0.5,0.3

Type RM Length L Ch R = 1 ,14172   ,130.0013,130.0013,130.0013
BEGIN DESCRIPTION:
Glenmore Rd-U
END DESCRIPTION:
XS GIS Cut Line= 6
 2037233.5040578  743241.9054356 2037356.3653613  743368.4867785
 2037434.5461908  743502.5182005 2037453.1663883  743565.8188721
 2037471.7765858  743725.9105706 2037471.7765858  743915.7825851
#Sta/Elev= 30
  4616.3  353.07  4626.8  351.83    4631  350.29  4647.2  347.22    4701  344.94
  4723.7  339.91    4843  335.41  4915.5  328.25  4982.7  327.64    4991  324.45
  4992.8  318.55  5007.2  318.55    5009  324.45  5031.8  327.32  5053.6  327.68
    5078  330.64  5083.4  330.05  5089.5  331.53  5100.1  330.83  5122.5  332.75
  5138.9  332.37    5146  334.58  5164.2  334.79  5177.8  336.21  5197.1  335.25
  5257.1  339.85  5269.7  341.88  5285.7  341.26  5326.7  344.91  5364.9   345.3
#Mann= 3 ,-1 , 0
  4616.3     .14       0    4991     .05       0    5009     .14       0
#XS Ineff= 2 , 0
       0  4949.5  332.74  5050.5       0  333.31
Permanent Ineff=
       F       F
Bank Sta=4991,5009
XS Rating Curve= 0
Exp/Cntr=0.5,0.3

Type RM Length L Ch R = 2 ,14094   ,,,
Node Photo=N:\NC_flood\60273\Approximates\Survey\Photos\NCF_1066.jpg
BEGIN DESCRIPTION:
Glenmore Rd-TOR
Structure ID: NCF-1066
Approximate Survey Structure
END DESCRIPTION:
Bridge Culvert--1,0,-1,-1, 0
Deck Dist Width WeirC Skew NumUp NumDn MinLoCord MaxHiCord MaxSubmerge Is_Ogee
43,70,3,0, 53, 53, , , , 0, 1,1,,
    4615  4618.5  4642.6  4648.6  4655.6  4662.3  4669.5  4672.6  4677.2  4682.1
  4701.6  4702.6  4705.8  4706.5  4710.4  4710.7    4712  4722.5  4729.4  4739.5
  4751.4  4755.4  4777.8  4793.9  4796.3  4819.6    4829  4840.5  4847.2  4855.1
  4869.3  4934.3  4962.7  5007.6  5049.8  5056.7  5097.7  5110.9  5116.7  5123.5
  5158.5  5166.4  5185.6  5191.1  5205.2  5210.2  5222.7  5227.8  5233.4  5236.2
  5248.1  5254.2  5260.5
  349.13  348.91  348.58  348.23  347.32  346.67  346.27  345.94  345.28  344.86
  343.82  343.71  343.64  343.75  343.09  342.94  342.87  341.77  341.31  340.42
  339.92  339.44  338.29  337.55  337.52  336.68  336.11  335.86   335.5  334.84
  334.21     333  332.38  332.53  333.28  333.55  334.55  335.03  334.97  335.41
  336.33  336.79  337.03  337.38  337.68   337.9  338.25  338.56  338.64  338.55
  339.26  339.25  339.51
  297.87  297.87  297.87  297.87  297.87  297.87  297.87  297.87  297.87  297.87
  297.87  297.87  297.87  297.87  297.87  297.87  297.87  297.87  297.87  297.87
  297.87  297.87  297.87  297.87  297.87  297.87  297.87  297.87  297.87  297.87
  297.87  297.87  297.87  297.87  297.87  297.87  297.87  297.87  297.87  297.87
  297.87  297.87  297.87  297.87  297.87  297.87  297.87  297.87  297.87  297.87
  297.87  297.87  297.87
    4615  4618.5  4642.6  4648.6  4655.6  4662.3  4669.5  4672.6  4677.2  4682.1
  4701.6  4702.6  4705.8  4706.5  4710.4  4710.7    4712  4722.5  4729.4  4739.5
  4751.4  4755.4  4777.8  4793.9  4796.3  4819.6    4829  4840.5  4847.2  4855.1
  4869.3  4934.3  4962.7  5007.6  5049.8  5056.7  5097.7  5110.9  5116.7  5123.5
  5158.5  5166.4  5185.6  5191.1  5205.2  5210.2  5222.7  5227.8  5233.4  5236.2
  5248.1  5254.2  5260.5
  349.13  348.91  348.58  348.23  347.32  346.67  346.27  345.94  345.28  344.86
  343.82  343.71  343.64  343.75  343.09  342.94  342.87  341.77  341.31  340.42
  339.92  339.44  338.29  337.55  337.52  336.68  336.11  335.86   335.5  334.84
  334.21     333  332.38  332.53  333.28  333.55  334.55  335.03  334.97  335.41
  336.33  336.79  337.03  337.38  337.68   337.9  338.25  338.56  338.64  338.55
  339.26  339.25  339.51
  297.52  297.52  297.52  297.52  297.52  297.52  297.52  297.52  297.52  297.52
  297.52  297.52  297.52  297.52  297.52  297.52  297.52  297.52  297.52  297.52
  297.52  297.52  297.52  297.52  297.52  297.52  297.52  297.52  297.52  297.52
  297.52  297.52  297.52  297.52  297.52  297.52  297.52  297.52  297.52  297.52
  297.52  297.52  297.52  297.52  297.52  297.52  297.52  297.52  297.52  297.52
  297.52  297.52  297.52
Culvert=1,7,,70,0.024,0.5,1,2,1,319.5,4996,319.15,4996,Culvert #1  , 0 ,43
Culvert Bottom n=0.024
Culvert=1,7,,70,0.024,0.5,1,1,3,319.8,5004,319.15,5004,Culvert #2  , 0 ,43
Culvert Bottom n=0.024
BC Design=,, 0 ,, 0 ,,,,,,
BC HTab HWMax=353.07

Type RM Length L Ch R = 1 ,14042   ,415.0042,415.0042,415.0042
BEGIN DESCRIPTION:
Glenmore Rd D
END DESCRIPTION:
XS GIS Cut Line= 4
 2037102.5226682  743329.9263694 2037274.4144918  743487.6580429
 2037331.0350926  743586.7490942 2037300.6947707  743916.3725913
#Sta/Elev= 30
  4672.5  343.81  4683.7  341.65  4754.1  337.81  4821.3  330.22  4830.5  327.71
  4852.5  325.57  4915.6  324.46  4982.4  325.58    4991  323.43  4992.8  317.53
  5007.2  317.53    5009  323.43    5010  322.54  5017.1  322.48  5026.5  324.41
  5029.2  327.15  5040.1  328.03  5053.6  327.01  5064.3  329.32  5075.7  327.52
  5081.5  328.76  5137.1  330.82  5143.5  332.89  5155.4  333.76  5238.3  337.33
  5244.8  339.99  5299.7  339.31    5309  340.62  5326.9  345.48  5350.9  347.54
#Mann= 3 ,-1 , 0
  4672.5     .14       0    4991     .05       0    5009     .14       0
#XS Ineff= 2 , 0
       0  4975.5   327.5  5024.5       0   327.5
Permanent Ineff=
       F       F
Bank Sta=4991,5009
XS Rating Curve= 0
Exp/Cntr=0.5,0.3

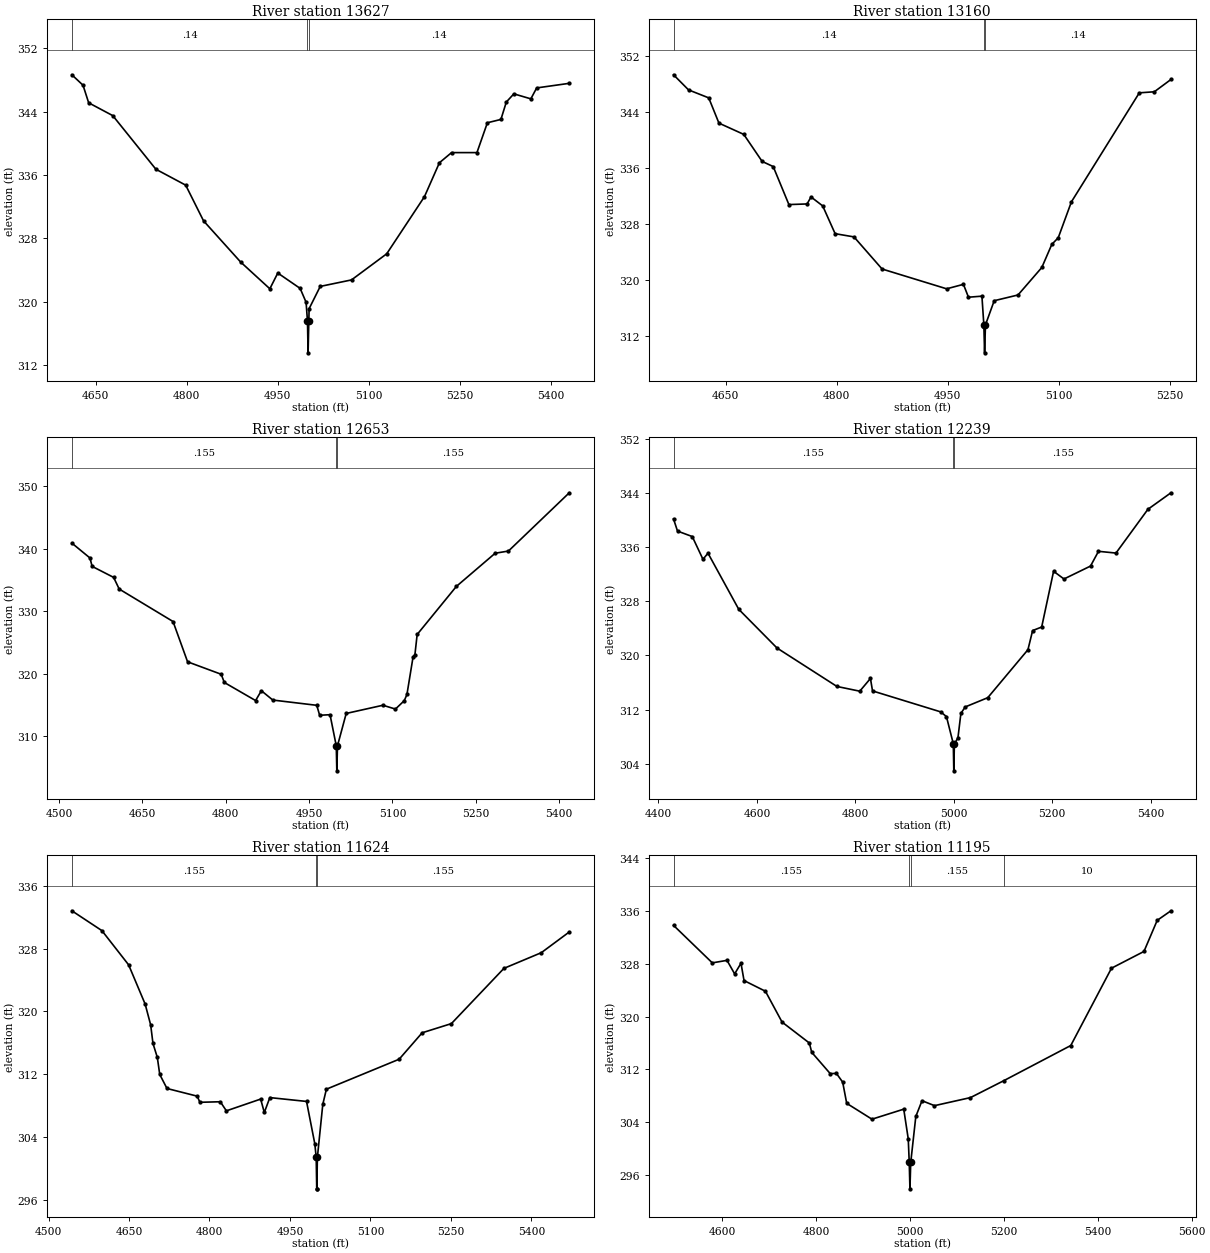
Type RM Length L Ch R = 1 ,13627   ,467.0047,467.0047,467.0047
BEGIN DESCRIPTION:
Bachelor Branch 22.0
END DESCRIPTION:
XS GIS Cut Line= 4
 2036920.7607398  743264.2456726 2036924.4907793  743666.3399386
 2036924.4907793  743859.9419926 2036931.9308583  744083.3243626
#Sta/Elev= 30
  4610.8  348.64  4629.2  347.32  4638.5   345.1  4678.2  343.48  4749.2  336.71
  4798.3   334.7  4827.7  330.19  4888.8  324.99  4936.9  321.61    4950   323.6
  4986.8  321.66  4996.6  319.91  4998.9  317.52  4999.9  313.52  5001.1  317.52
  5001.6   319.1  5019.9  321.91  5071.4  322.73  5129.4  326.03  5191.6  333.25
  5216.2  337.53  5236.2  338.81    5278  338.81  5295.2  342.58  5317.5     343
  5326.4   345.2  5338.8  346.23  5366.8   345.6  5376.4  346.98  5430.1  347.56
#Mann= 3 ,-1 , 0
  4610.8     .14       0  4998.9     .05       0  5001.1     .14       0
Bank Sta=4998.9,5001.1
XS Rating Curve= 0
Exp/Cntr=0.3,0.1

Type RM Length L Ch R = 1 ,13160   ,507.0051,507.0051,507.0051
BEGIN DESCRIPTION:
Bachelor Branch 21.0
END DESCRIPTION:
XS GIS Cut Line= 3
 2036682.4882118  743290.3059491 2036488.8861578  743673.7900176
 2036377.1949728  743889.7223086
#Sta/Elev= 30
  4579.3  349.32  4599.6  347.16  4626.9  346.02  4640.7  342.41  4674.3   340.8
  4699.1  336.94  4714.1   336.2  4735.3  330.77  4759.9  330.86  4765.2  331.86
    4781  330.58  4797.8  326.61  4823.3  326.15  4861.3  321.56  4948.6  318.73
  4971.3  319.37  4978.1  317.53  4996.3  317.68  4998.9  313.58  4999.9  309.58
  5001.1  313.58  5012.9  317.03  5045.1  317.85  5077.3  321.78  5090.8  325.08
  5099.5  326.03  5117.3  331.16  5209.1  346.74  5229.4  346.89  5251.9  348.65
#Mann= 3 ,-1 , 0
  4579.3     .14       0  4998.9     .05       0  5001.1     .14       0
Bank Sta=4998.9,5001.1
XS Rating Curve= 0
Exp/Cntr=0.3,0.1

Type RM Length L Ch R = 1 ,12653   ,414.0042,414.0042,414.0042
BEGIN DESCRIPTION:
Bachelor Branch 20.0
END DESCRIPTION:
XS GIS Cut Line= 3
 2035993.7109042   743037.133263 2036027.2212597  743517.4183586
 2036049.5614968  743930.6827431
#Sta/Elev= 30
    4523  340.89  4555.6  338.51  4559.5  337.17  4598.2  335.41  4608.2  333.55
  4705.1  328.36  4731.3  321.92  4791.8  319.93  4797.4  318.62  4853.7  315.73
  4864.1   317.3  4884.7  315.81  4963.8  314.97    4969  313.38  4987.7  313.47
  4998.9   308.5  4999.9   304.5  5001.1   308.5  5016.8  313.67  5082.9  314.98
  5105.4  314.37  5121.3  315.71  5126.1   316.7  5137.2  322.74  5140.4  323.01
  5144.5  326.29  5215.1  333.97  5284.9  339.27  5308.8  339.62  5418.3  348.93
#Mann= 3 ,-1 , 0
    4523    .155       0  4998.9     .05       0  5001.1    .155       0
Bank Sta=4998.9,5001.1
XS Rating Curve= 0
Exp/Cntr=0.3,0.1

Type RM Length L Ch R = 1 ,12239   ,615.0062,615.0062,615.0062
BEGIN DESCRIPTION:
Bachelor Branch 19.0
END DESCRIPTION:
XS GIS Cut Line= 4
 2035520.8858878  743025.9631445 2035632.5770728  743591.8791486
 2035710.7579022  743796.6513211 2035785.2186922  743997.6934541
#Sta/Elev= 30
  4430.6  340.17  4438.7  338.38  4468.7  337.57  4490.4  334.21  4500.6  335.11
  4563.1  326.82  4640.8   321.1  4762.5  315.42  4808.9  314.72  4830.6   316.6
  4834.8  314.76  4973.4  311.66    4985  310.96  4998.9  306.95  4999.9  302.95
  5001.1  306.95  5008.3  307.82  5014.3  311.43    5023  312.39  5068.9  313.76
  5150.5  320.85    5160  323.68  5178.4   324.2  5202.6  332.44  5223.7   331.3
  5277.6  333.21  5293.8  335.39  5329.3  335.13  5394.2   341.6    5441  344.04
#Mann= 3 ,-1 , 0
  4430.6    .155       0  4998.9     .05       0  5001.1    .155       0
Bank Sta=4998.9,5001.1
XS Rating Curve= 0
Exp/Cntr=0.3,0.1

Type RM Length L Ch R = 1 ,11624   ,429.0043,429.0043,429.0043
BEGIN DESCRIPTION:
Bachelor Branch 18.0
END DESCRIPTION:
XS GIS Cut Line= 3
 2034954.9698837  743290.3059491 2035066.6610687  743744.5207681
 2035223.0327277  744176.4053501
#Sta/Elev= 30
  4543.5  332.81  4599.5  330.28  4649.3  325.92  4680.1  320.92  4690.4  318.26
  4694.7   315.9  4702.8  314.12  4707.3  311.95  4720.8  310.16  4777.2  309.18
  4782.1   308.4  4820.2  308.47  4831.5  307.31  4895.4  308.81  4902.2   307.1
  4912.5     309  4980.9  308.51  4996.4  303.08  4998.9  301.37  4999.9  297.37
  5000.1  297.37  5001.1  301.37  5011.2  308.14  5017.9  310.07  5153.5  313.89
  5196.4  317.26  5250.9  318.43  5348.8  325.47  5418.5  327.47  5470.6  330.11
#Mann= 3 ,-1 , 0
  4543.5    .155       0  4998.9     .05       0  5001.1    .155       0
Bank Sta=4998.9,5001.1
XS Rating Curve= 0
Exp/Cntr=0.3,0.1

Type RM Length L Ch R = 1 ,11195   ,629.0064,629.0064,629.0064
BEGIN DESCRIPTION:
Bachelor Branch 17.0
END DESCRIPTION:
XS GIS Cut Line= 4
 2034683.1870002  743312.6461861 2034675.7369211  743833.8817161
 2034664.5668026  744083.3243626 2034631.0664472  744370.0074042
#Sta/Elev= 30
  4496.3  333.81  4578.9  328.13  4610.2  328.51  4626.5  326.46    4640  328.07
  4646.5  325.45  4692.1  323.83  4727.5  319.16  4785.6  315.99  4790.7  314.58
    4830  311.36  4843.3  311.38  4856.6  310.07  4865.2  306.85    4919  304.45
  4986.7  305.97  4996.3  301.47  4998.4   297.9  4999.9   293.9  5001.6   297.9
  5012.4  304.86  5025.6  307.25  5052.2   306.5  5128.8  307.72    5200  310.29
  5342.5  315.61  5429.2  327.32  5498.4  329.86  5526.6  334.57  5555.9  336.02
#Mann= 4 ,-1 , 0
  4496.3    .155       0  4998.4     .05       0  5001.6    .155       0
    5200      10       0
Bank Sta=4998.4,5001.6
XS Rating Curve= 0
Exp/Cntr=0.3,0.1

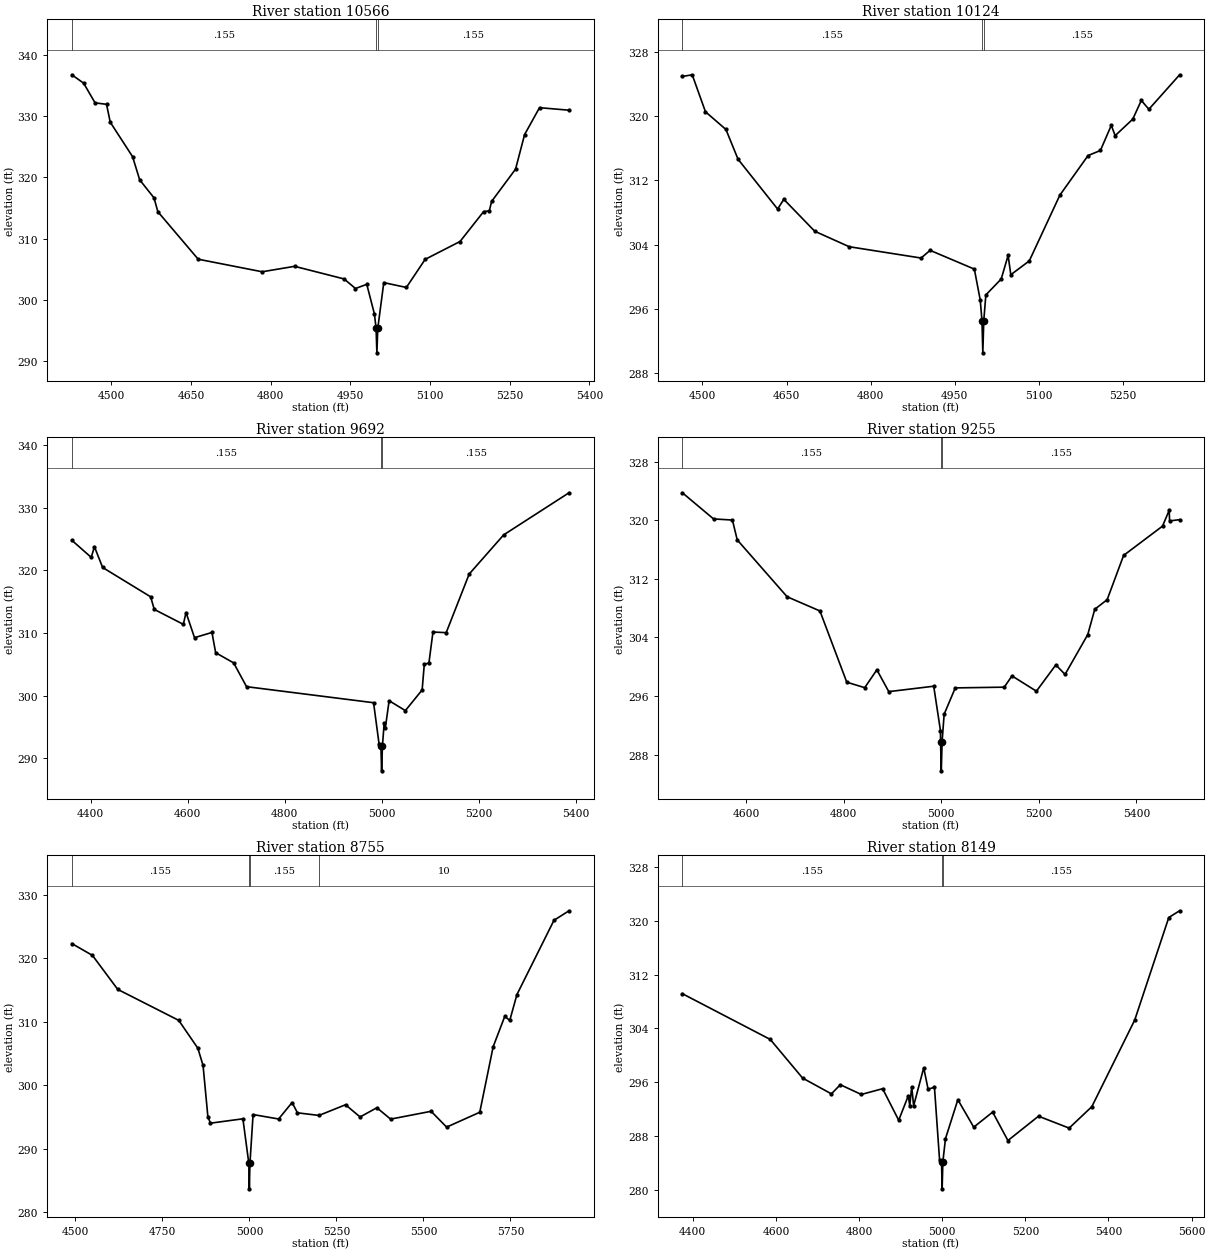
Type RM Length L Ch R = 1 ,10566   ,442.0045,442.0045,442.0045
BEGIN DESCRIPTION:
Bachelor Branch 16.0
END DESCRIPTION:
XS GIS Cut Line= 3
 2034169.4015492  743357.3266601 2034147.0613122  743941.8428616
 2034124.7210751  744291.8165746
#Sta/Elev= 30
  4425.8  336.75    4448  335.38  4469.5  332.17  4491.1  331.93  4498.1  329.01
  4540.1  323.39  4553.5   319.6  4580.4  316.67  4587.7   314.4  4663.6  306.65
    4784   304.6    4845  305.49  4938.2  303.43  4959.6  301.87  4980.9  302.55
  4995.3   297.7  4998.4  295.37  4999.9  291.37  5001.6  295.37  5012.9  302.83
  5055.4  302.04  5090.8  306.63  5156.4  309.54  5200.9  314.43  5211.5  314.53
  5215.8  316.08  5260.9  321.35  5277.9  326.99    5306  331.38  5361.5  330.97
#Mann= 3 ,-1 , 0
  4425.8    .155       0  4998.4     .05       0  5001.6    .155       0
Bank Sta=4998.4,5001.6
XS Rating Curve= 0
Exp/Cntr=0.3,0.1

Type RM Length L Ch R = 1 ,10124   ,432.0044,432.0044,432.0044
BEGIN DESCRIPTION:
Bachelor Branch 15.0
END DESCRIPTION:
XS GIS Cut Line= 3
 2033733.7969276  743375.9368576 2033730.0768881  743919.5126246
 2033718.9067696  744262.0362586
#Sta/Elev= 30
  4464.4  324.97  4481.9  325.18  4505.5  320.57    4542  318.36  4563.6  314.65
  4634.1  308.44  4645.2  309.65  4700.3  305.67  4761.8  303.74  4889.9  302.33
  4905.9  303.29  4984.8  300.95  4995.3   297.1  4998.4  294.51  4999.9  290.51
  5001.6  294.51  5005.3  297.73  5032.7  299.72    5045  302.66  5049.8  300.25
  5082.7  301.97  5137.3  310.18  5187.5  315.11  5209.5  315.74  5228.9  318.88
  5235.8  317.59  5267.2  319.65  5282.4  321.98  5295.9  320.88  5350.6  325.17
#Mann= 3 ,-1 , 0
  4464.4    .155       0  4998.4     .05       0  5001.6    .155       0
Bank Sta=4998.4,5001.6
XS Rating Curve= 0
Exp/Cntr=0.3,0.1

Type RM Length L Ch R = 1 ,9692    ,437.0044,437.0044,437.0044
BEGIN DESCRIPTION:
Bachelor Branch 14.0
END DESCRIPTION:
XS GIS Cut Line= 3
 2033324.2625827  743290.3059491 2033324.2625827  743945.5729011
 2033290.7522271  744314.1568116
#Sta/Elev= 30
    4361   324.8    4401  322.07  4407.6  323.77  4424.5  320.46  4523.5  315.78
    4531  313.77  4590.9  311.39  4596.6  313.26    4614  309.26    4650  310.09
  4657.6  306.86  4694.8  305.23  4721.3  301.44  4983.3  298.88  4994.7  292.27
  4998.4  292.01  4999.9  288.01  5001.6  292.01  5005.2   295.6  5007.6  294.88
  5015.4   299.2  5048.9  297.62  5083.5  300.92  5087.9  304.98  5097.5  305.24
  5105.8  310.16  5133.1  310.06  5180.5  319.41  5251.6  325.66  5386.4  332.38
#Mann= 3 ,-1 , 0
    4361    .155       0  4998.4     .05       0  5001.6    .155       0
Bank Sta=4998.4,5001.6
XS Rating Curve= 0
Exp/Cntr=0.3,0.1

Type RM Length L Ch R = 1 ,9255    ,500.0051,500.0051,500.0051
BEGIN DESCRIPTION:
Bachelor Branch 13.0
END DESCRIPTION:
XS GIS Cut Line= 4
 2033052.4696991  743253.0755541 2032981.7289485  743785.4812026
 2032970.5688301  744020.0336911 2032996.6291066  744265.7562981
#Sta/Elev= 30
  4469.3  323.74  4533.2  320.17  4571.8  320.02  4581.7  317.31  4683.9  309.55
  4751.2  307.61  4806.2  297.89    4843  297.14  4867.9  299.58  4892.3   296.6
  4984.4  297.34  4998.3  291.25  4998.4  289.79  4999.9  285.79  5001.6  289.79
  5005.8  293.52  5028.6  297.11    5129  297.21  5144.8  298.75  5194.9  296.66
  5234.7  300.25  5253.6  298.95  5300.1  304.38  5314.5  307.84  5339.9  309.15
  5373.6  315.19  5453.4  319.19    5467  321.34  5467.9   319.9  5488.3  320.07
#Mann= 3 ,-1 , 0
  4469.3    .155       0  4998.4     .05       0  5001.6    .155       0
Bank Sta=4998.4,5001.6
XS Rating Curve= 0
Exp/Cntr=0.3,0.1

Type RM Length L Ch R = 1 ,8755    ,606.0061,606.0061,606.0061
BEGIN DESCRIPTION:
Bachelor Branch 12.0
END DESCRIPTION:
XS GIS Cut Line= 4
 2032579.6346825  743159.9945665 2032549.8543666  743681.2300966
 2032482.8436556  744291.8165746 2032426.9930631  744578.4996162
#Sta/Elev= 30
  4489.9  322.28  4549.1  320.42  4621.8  315.07    4797   310.2  4851.9  305.82
  4866.9   303.1  4880.7  295.07    4888  294.02  4981.4  294.71  4998.4  287.69
  4999.9  283.69  5001.6  287.69  5010.6  295.38  5083.9  294.68  5122.7  297.27
  5138.1  295.65    5200  295.24  5276.2  296.92  5318.1     295  5366.3  296.45
  5405.7  294.66  5522.1  295.89  5566.7   293.4  5661.9  295.74  5700.4  306.05
  5733.7  310.82  5748.1  310.19  5768.7  314.26  5875.1  325.94  5918.3  327.44
#Mann= 4 ,-1 , 0
  4489.9    .155       0  4998.4     .05       0  5001.6    .155       0
    5200      10       0
Bank Sta=4998.4,5001.6
XS Rating Curve= 0
Exp/Cntr=0.3,0.1

Type RM Length L Ch R = 1 ,8149    ,561.0057,561.0057,561.0057
BEGIN DESCRIPTION:
Bachelor Branch 11.0
END DESCRIPTION:
XS GIS Cut Line= 5
  2032233.391009  743204.6750406 2032088.1894685   743513.688319
 2031983.9483626  743778.0311236  2031890.867375  744046.0939676
  2031771.726111  744306.7067326
#Sta/Elev= 30
  4375.1  309.16  4586.5  302.36  4664.2  296.62  4733.5  294.27  4754.9  295.63
  4805.5  294.18  4856.7  295.04  4895.4  290.35  4918.6     294    4922  292.46
  4926.7  295.34  4931.3   292.5  4955.6  298.14  4966.1  294.97  4981.4  295.25
  4993.7  284.44  4998.4  284.15  4999.9  280.15  5001.6  284.15  5007.9  287.61
  5037.7   293.4  5075.9  289.32  5121.4  291.56  5158.1  287.33  5231.7  290.95
  5305.4  289.18    5360  292.37  5463.1  305.24  5545.1  320.49    5571  321.49
#Mann= 3 ,-1 , 0
  4375.1    .155       0  4998.4     .05       0  5001.6    .155       0
Bank Sta=4998.4,5001.6
XS Rating Curve= 0
Exp/Cntr=0.3,0.1