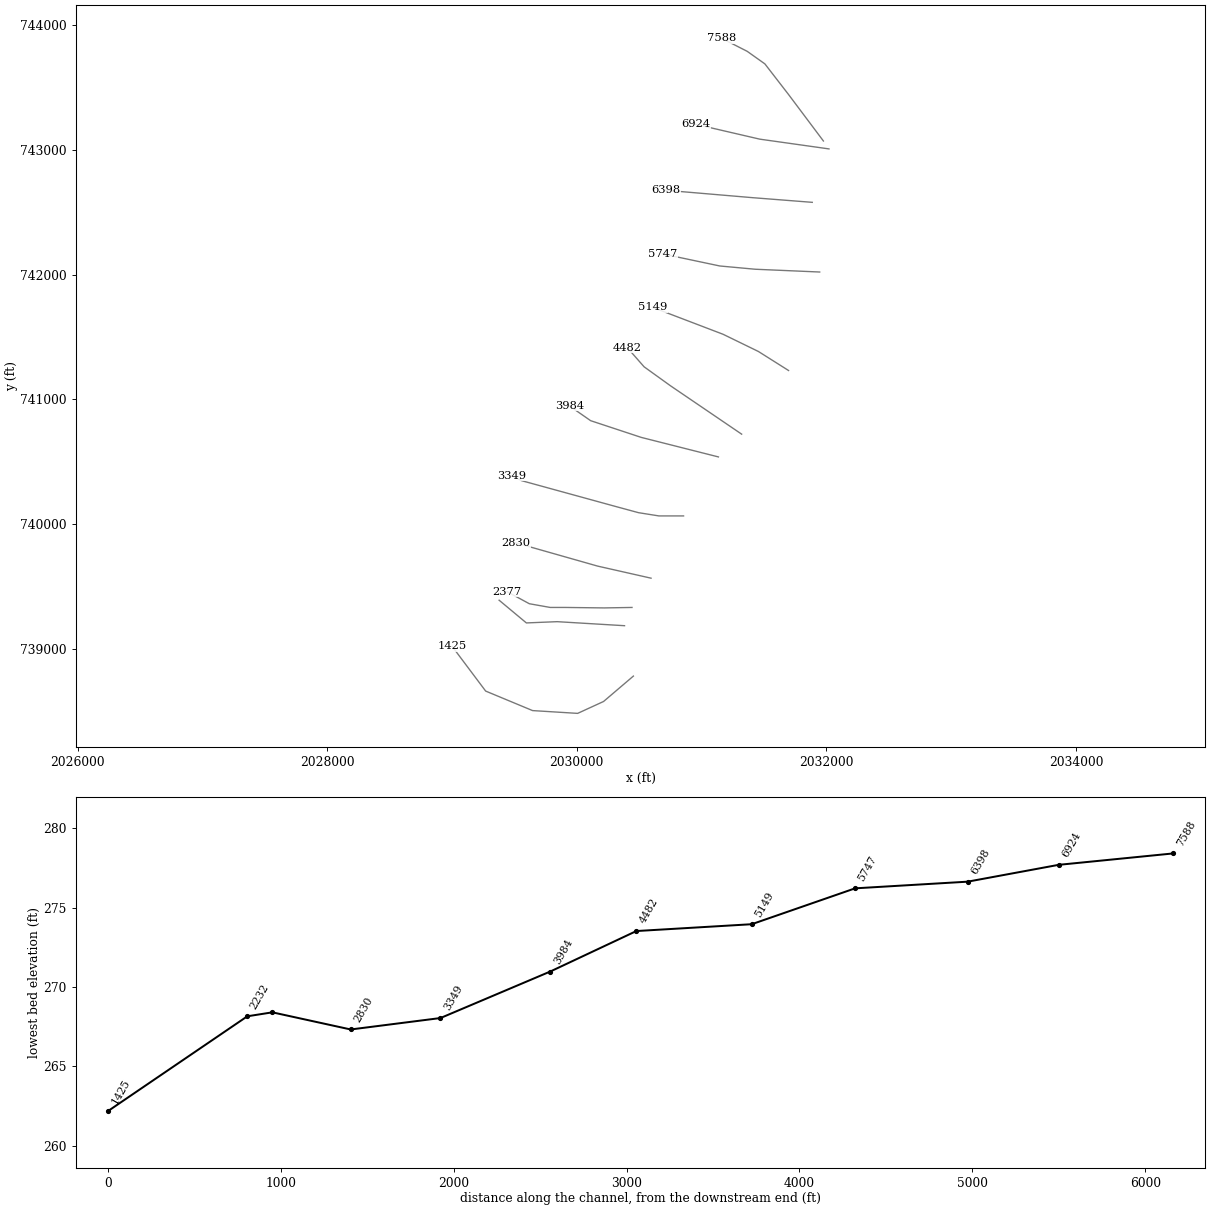
HEC-RAS study Bachelor_Branch_ADJ.prj: Bachelor Branch (B28, S6) LDS Adjusted

--- Bachelor_Branch_ADJ.g01 (geometry) --- (continued)

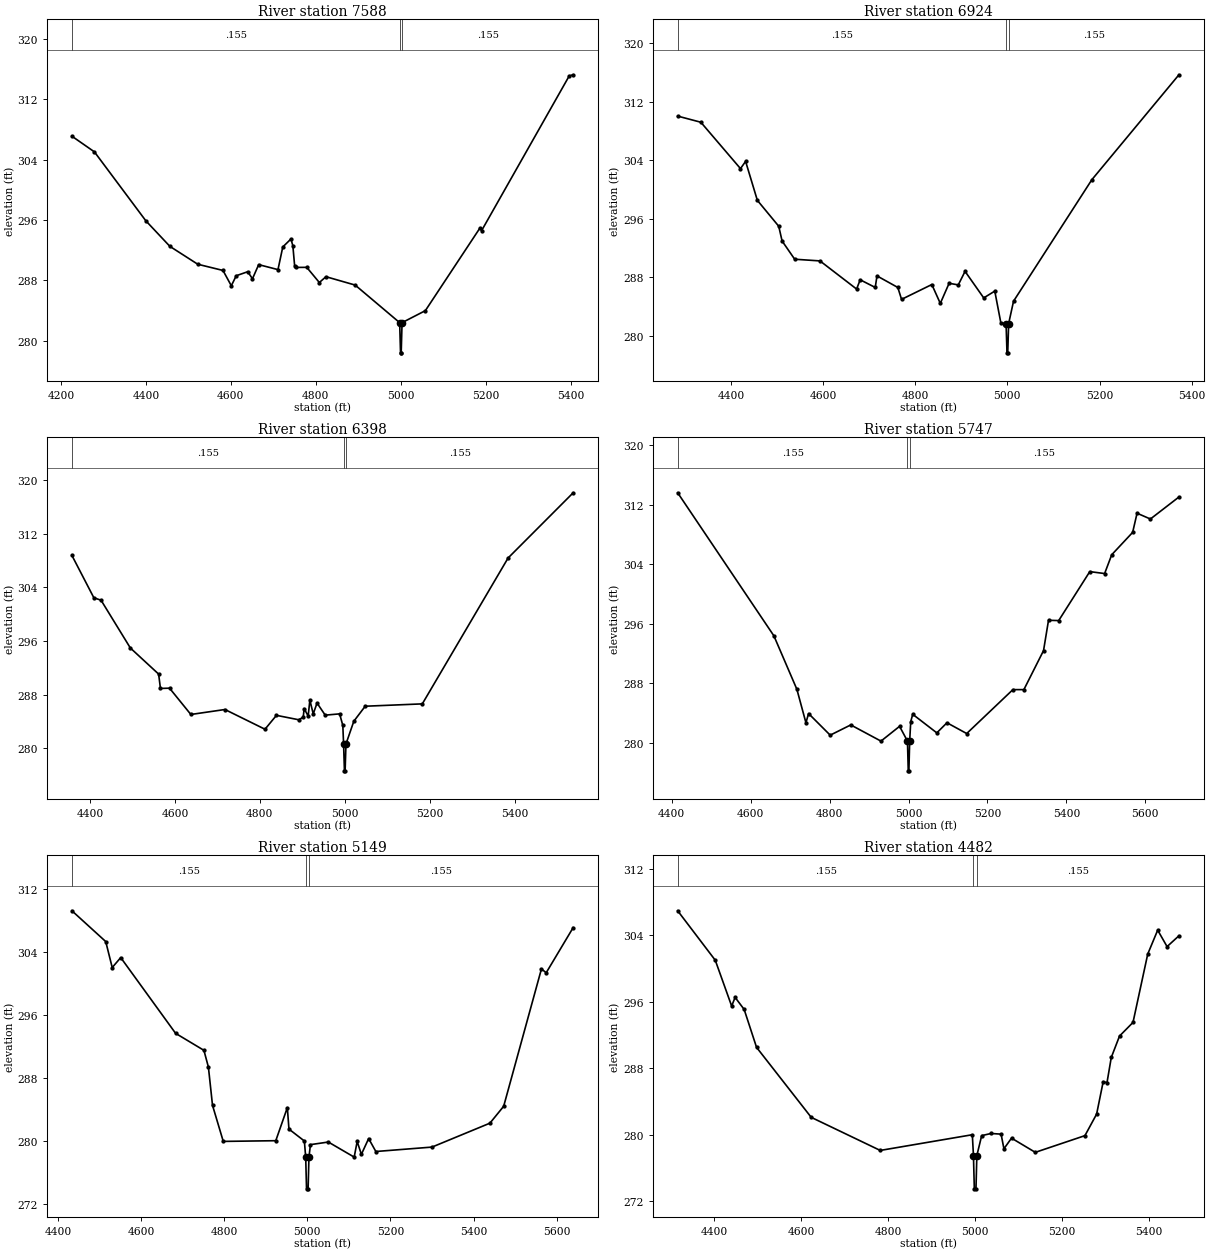
Type RM Length L Ch R = 1 ,7588    ,664.0067,664.0067,664.0067
BEGIN DESCRIPTION:
Bachelor Branch 10.0
END DESCRIPTION:
XS GIS Cut Line= 5
 2031976.4982835  743070.6436186  2031697.265321  743442.9575686
 2031507.3933066  743688.6801756 2031365.9118055  743789.2012421
  2031161.139633  743893.4523482
#Sta/Elev= 30
  4226.1  307.12  4279.1  305.04    4400  295.91  4456.6  292.52  4522.2  290.15
  4581.5  289.33  4601.1   287.3  4612.7  288.63  4639.7  289.16  4650.9  288.23
  4665.5   290.1  4710.9  289.44  4722.2  292.44  4741.4   293.5  4745.9   292.6
  4750.1  289.93  4753.9  289.73  4778.6  289.74  4808.2  287.73  4823.8   288.5
  4892.5  287.39  4997.2  282.41  4999.2  278.41  5000.8  278.41  5002.8  282.41
  5057.6     284  5186.4  294.98  5190.1  294.62  5396.1  315.11  5405.4  315.26
#Mann= 3 ,-1 , 0
  4226.1    .155       0  4997.2     .05       0  5002.8    .155       0
Bank Sta=4997.2,5002.8
XS Rating Curve= 0
Exp/Cntr=0.3,0.1

Type RM Length L Ch R = 1 ,6924    ,526.0053,526.0053,526.0053
BEGIN DESCRIPTION:
Bachelor Branch 9.0
END DESCRIPTION:
XS GIS Cut Line= 3
 2032021.1787576  743007.3529471  2031466.432872  743085.5337765
  2030952.647421  743204.6750406
#Sta/Elev= 30
  4284.6  310.06  4334.9  309.22  4420.9  302.88    4432  303.87  4457.5  298.54
  4503.9     295  4511.2  292.98  4538.5  290.49  4593.4  290.26  4672.9  286.41
  4680.6  287.68  4713.3  286.63  4717.1  288.21  4762.3  286.63  4770.4     285
  4836.1  287.03  4854.5  284.45  4873.6   287.2  4893.5  286.98  4908.2  288.83
  4948.7   285.2  4972.7  286.13    4986  281.75  4997.2  281.69  4999.2  277.69
  5000.8  277.69  5002.8  281.69  5013.4  284.75  5183.3  301.36  5372.3  315.71
#Mann= 3 ,-1 , 0
  4284.6    .155       0  4997.2     .05       0  5002.8    .155       0
Bank Sta=4997.2,5002.8
XS Rating Curve= 0
Exp/Cntr=0.3,0.1

Type RM Length L Ch R = 1 ,6398    ,651.0066,651.0066,651.0066
BEGIN DESCRIPTION:
Bachelor Branch 8.0
END DESCRIPTION:
XS GIS Cut Line= 3
 2031887.1473356  742579.1984046 2031410.5922795  742616.4287996
 2030710.6448534  742675.9994316
#Sta/Elev= 30
  4357.4  308.73  4409.1  302.42    4426  302.06    4495  294.94  4561.6  291.05
  4565.9  288.91  4587.3  288.95  4637.5  285.03  4717.8  285.77  4812.1  282.83
  4839.1   284.9  4891.8  284.24  4902.2  284.64  4904.3  285.91  4913.8   284.8
  4917.8  287.17  4925.7  285.12  4934.7  286.73  4953.9  284.93  4987.9  285.12
  4995.4  283.39  4997.2  280.63  4999.2  276.63  5000.8  276.63  5002.8  280.63
  5021.3  284.02  5048.1  286.26  5182.6  286.61  5384.6  308.35  5537.9  318.07
#Mann= 3 ,-1 , 0
  4357.4    .155       0  4997.2     .05       0  5002.8    .155       0
Bank Sta=4997.2,5002.8
XS Rating Curve= 0
Exp/Cntr=0.3,0.1

Type RM Length L Ch R = 1 ,5747    ,598.0061,598.0061,598.0061
BEGIN DESCRIPTION:
Bachelor Branch 7.0
END DESCRIPTION:
XS GIS Cut Line= 4
 2031946.7179676  742020.7324795  2031429.202477  742043.0727165
  2031146.249475   742069.132993 2030688.3046164    742165.93402
#Sta/Elev= 30
  4414.9  313.63  4658.7  294.38    4717  287.18  4739.9  282.68  4746.6  283.92
  4801.4  281.01  4853.5  282.39  4930.1  280.21  4977.2   282.2  4997.2  280.21
  4999.2  276.21  5000.8  276.21  5002.8  280.21  5005.5  282.84  5010.5  283.82
  5071.6  281.32  5097.3  282.68  5147.3  281.23  5264.4  287.14  5292.2  287.14
    5342  292.39  5354.6  296.47  5380.4  296.43  5459.2  303.02  5496.8  302.76
  5514.8  305.29  5567.8   308.3    5579  310.88  5612.8   310.1  5685.1  313.06
#Mann= 3 ,-1 , 0
  4414.9    .155       0  4997.2     .05       0  5002.8    .155       0
Bank Sta=4997.2,5002.8
XS Rating Curve= 0
Exp/Cntr=0.3,0.1

Type RM Length L Ch R = 1 ,5149    ,667.0068,667.0068,667.0068
BEGIN DESCRIPTION:
Bachelor Branch 6.0
END DESCRIPTION:
XS GIS Cut Line= 4
  2031697.265321  741231.4341054 2031455.2627535   741384.085725
 2031172.3097515  741521.8371865 2030606.4037475  741737.7794775
#Sta/Elev= 30
  4433.4  309.18  4514.8  305.28  4530.4  301.99  4550.9  303.25    4683  293.65
  4751.1   291.5  4761.9  289.38  4771.8  284.53  4797.7  279.96  4924.1  280.05
  4951.9  284.24  4955.8  281.52  4992.9  280.01  4996.1  277.95  4998.1  273.95
  5001.9  273.95  5003.9  277.95  5007.5  279.55  5050.6  279.88  5112.8  277.97
    5120  279.95  5130.1  278.32  5147.6  280.32  5164.9  278.68  5300.1  279.24
  5439.5  282.27  5472.6  284.41  5563.5  301.81    5575  301.33  5639.9  307.05
#Mann= 3 ,-1 , 0
  4433.4    .155       0  4996.1     .05       0  5003.9    .155       0
Bank Sta=4996.1,5003.9
XS Rating Curve= 0
Exp/Cntr=0.3,0.1

Type RM Length L Ch R = 1 ,4482    ,498.005,498.005,498.005
BEGIN DESCRIPTION:
Bachelor Branch 5.0
END DESCRIPTION:
XS GIS Cut Line= 4
 2031321.2313315   740721.378694  2030751.605288  741108.5728019
 2030539.3830364  741261.2244215 2030405.3516144  741413.8660409
#Sta/Elev= 30
  4315.5  306.97    4402  301.02  4439.7  295.51  4447.7  296.55  4468.5   295.1
    4497  290.54  4622.8  282.12  4781.6  278.14  4993.5  280.03  4996.1  277.52
  4998.1  273.52  5001.9  273.52  5003.9  277.52    5015  279.92  5036.5  280.18
  5059.7   280.1  5066.2  278.34  5083.7  279.62  5138.4  277.91  5252.6  279.92
  5279.5  282.51  5294.6  286.41  5303.4   286.3  5313.2  289.32  5332.2   291.9
  5363.2  293.54  5397.1  301.76    5420  304.64  5441.6  302.66  5468.9  303.96
#Mann= 3 ,-1 , 0
  4315.5    .155       0  4996.1     .05       0  5003.9    .155       0
Bank Sta=4996.1,5003.9
XS Rating Curve= 0
Exp/Cntr=0.3,0.1

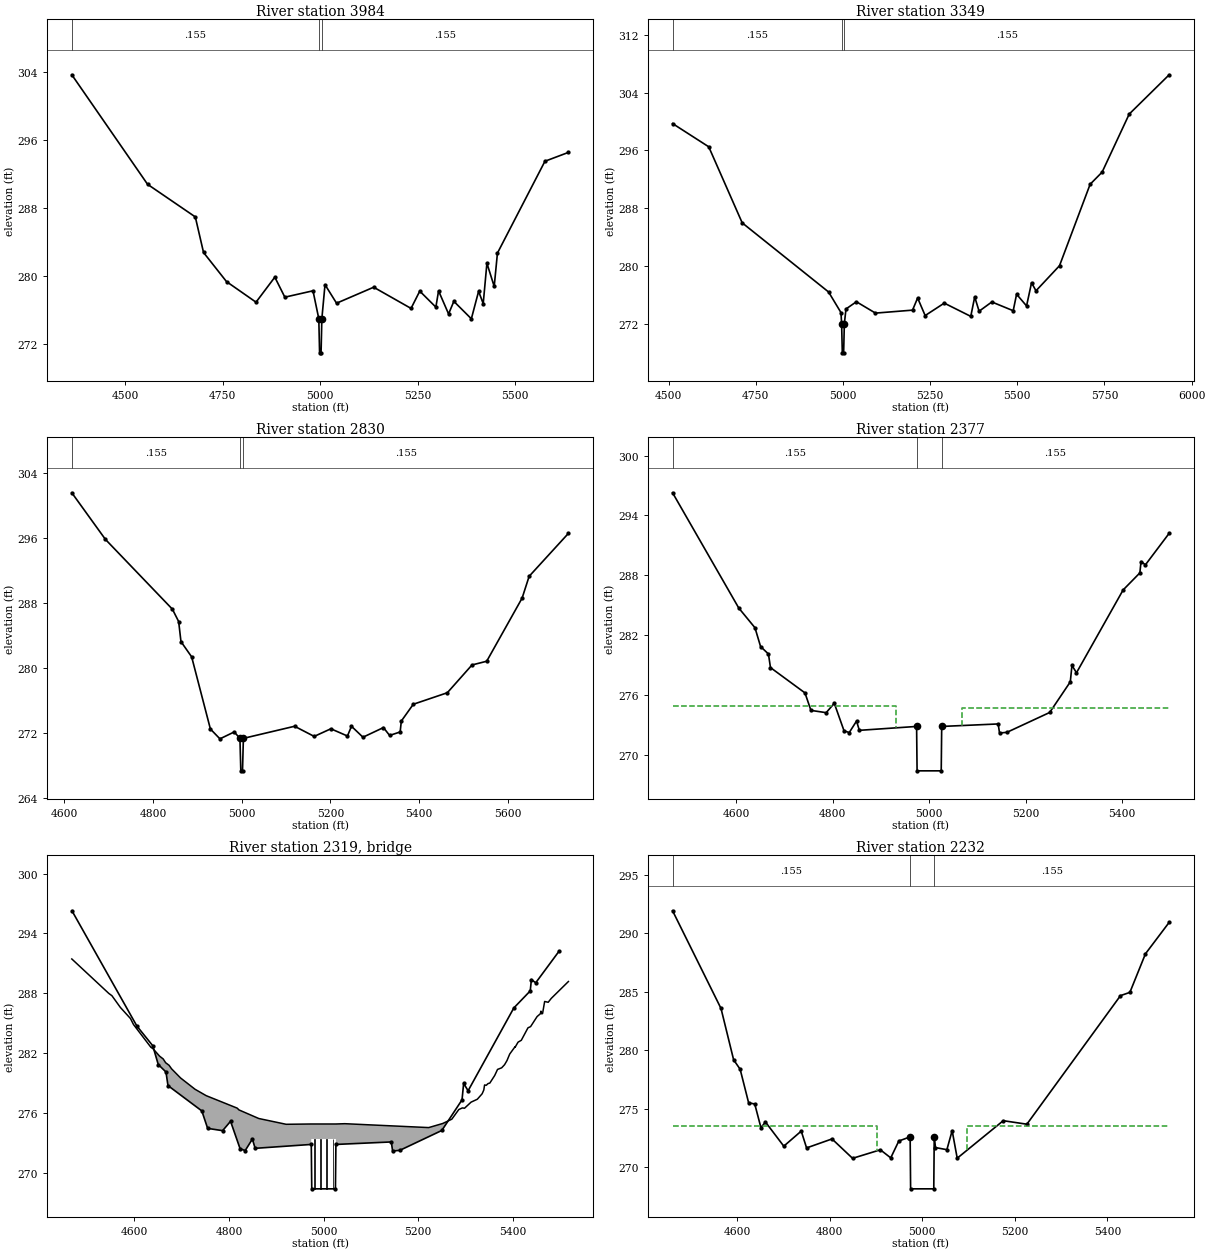
Type RM Length L Ch R = 1 ,3984    ,635.0064,635.0064,635.0064
BEGIN DESCRIPTION:
Bachelor Branch 4.0
END DESCRIPTION:
XS GIS Cut Line= 4
 2031135.0793565  740538.9467585 2030517.0427994  740695.3084174
 2030111.2284939  740829.3398394 2029939.9666769  740948.4811034
#Sta/Elev= 30
  4362.7  303.64    4557  290.77  4679.4  286.94  4700.5  282.76  4759.4  279.34
  4835.1  276.92  4883.3  279.86    4909  277.51  4981.2  278.26  4996.1  274.97
  4998.1  270.97  5001.9  270.97  5003.9  274.97    5012  278.98  5041.6   276.8
  5136.8  278.68  5232.6  276.19    5255  278.22  5296.3  276.34  5303.2  278.25
  5328.9  275.54  5342.4  277.02  5387.3  274.97  5405.9   278.2  5417.7  276.75
  5427.2   281.5  5445.9  278.77  5454.2  282.69    5576  293.48  5636.2  294.52
#Mann= 3 ,-1 , 0
  4362.7    .155       0  4996.1     .05       0  5003.9    .155       0
Bank Sta=4996.1,5003.9
XS Rating Curve= 0
Exp/Cntr=0.3,0.1

Type RM Length L Ch R = 1 ,3349    ,519.0053,519.0053,519.0053
BEGIN DESCRIPTION:
Bachelor Branch 3.0
END DESCRIPTION:
XS GIS Cut Line= 6
  2030855.846394  740066.1117419 2030658.5243005  740066.1117419
 2030494.7125625  740092.1720184 2030316.0006665  740140.5725319
 2029556.4926084  740349.0647439 2029478.3017789  740390.0151784
#Sta/Elev= 30
  4511.3  299.72    4615  296.51    4711     286  4958.7  276.45  4994.3   273.6
  4996.1  272.04  4998.1  268.04  5001.9  268.04  5003.9  272.04  5008.6   274.1
  5038.5   275.1  5093.2  273.53  5199.5  273.94  5214.1  275.62  5235.7  273.19
  5290.5  274.91  5366.5  273.08  5377.8  275.77  5390.4  273.79  5426.9  275.07
  5488.2  273.86  5497.9  276.14  5526.5  274.52  5540.8  277.73  5553.5  276.61
    5621  280.08  5708.8  291.33  5743.2  293.01  5820.9  301.03  5935.5  306.46
#Mann= 3 ,-1 , 0
  4511.3    .155       0  4996.1     .05       0  5003.9    .155       0
Bank Sta=4996.1,5003.9
XS Rating Curve= 0
Exp/Cntr=0.3,0.1

Type RM Length L Ch R = 1 ,2830    ,453.0046,453.0046,453.0046
BEGIN DESCRIPTION:
Bachelor Branch 2.0
END DESCRIPTION:
XS GIS Cut Line= 3
  2030595.233629  739567.2164489 2030167.0790865  739664.0174759
 2029511.8121344  739850.1694509
#Sta/Elev= 30
  4616.9  301.57  4692.7  295.83  4843.8  287.23  4857.9  285.71  4863.1  283.24
  4887.2  281.36  4929.5  272.47    4951  271.26  4983.2  272.11  4996.1  271.32
  4998.1  267.32  5001.9  267.32  5003.9  271.32  5119.4  272.81  5163.6  271.56
  5201.2   272.5  5238.6  271.61  5247.7  272.81  5273.6  271.46  5319.8  272.65
  5333.7  271.68  5357.5  272.11  5360.1  273.45  5387.1  275.52  5463.9  276.94
  5519.5  280.36  5552.7  280.82  5632.6   288.6  5648.4  291.28    5737  296.57
#Mann= 3 ,-1 , 0
  4616.9    .155       0  4996.1     .05       0  5003.9    .155       0
Bank Sta=4996.1,5003.9
XS Rating Curve= 0
Exp/Cntr=0.5,0.3

Type RM Length L Ch R = 1 ,2377    ,145.0015,145.0015,145.0015
BEGIN DESCRIPTION:
Green Level West Rd-U
END DESCRIPTION:
XS GIS Cut Line= 6
 2030442.5820094  739332.6639604 2030219.1996394  739328.9339208
  2029910.186361  739332.6639604 2029787.3250575  739332.6639604
 2029619.7832799  739362.4442764 2029441.0713839  739459.2453034
#Sta/Elev= 30
  4468.5  296.27  4605.6  284.72  4639.2  282.74  4650.8  280.86  4667.1  280.11
  4671.3  278.75  4742.8  276.21  4755.1  274.46  4786.7  274.23  4803.5  275.17
  4823.7  272.41  4834.5  272.24  4849.6  273.39  4855.4  272.46    4974  272.85
    4975   268.4    5025   268.4    5026  272.85    5143   273.1  5145.8  272.19
  5161.1  272.26  5249.7  274.25  5292.4  277.32  5295.8  278.97  5305.2  278.23
  5401.8  286.53  5436.5  288.24  5438.9  289.38    5448  289.05  5497.2  292.21
#Mann= 3 ,-1 , 0
  4468.5    .155       0    4974     .05       0    5026    .155       0
#XS Ineff= 2 , 0
       0  4931.5  274.93  5068.5       0  274.68
Permanent Ineff=
       F       F
Bank Sta=4974,5026
XS Rating Curve= 0
Exp/Cntr=0.5,0.3

Type RM Length L Ch R = 3 ,2319    ,,,
Node Photo=N:\NC_flood\60273\Approximates\Survey\Photos\NCF_1065.jpg
BEGIN DESCRIPTION:
Green Level West Rd-TOR
Structure ID: NCF-1065
Approximate Survey Structure
END DESCRIPTION:
Bridge Culvert--1,0,-1,-1, 0
Deck Dist Width WeirC Skew NumUp NumDn MinLoCord MaxHiCord MaxSubmerge Is_Ogee
42.5,31,3,0, 60, 60, , , , 0, 1,1,,
  4468.2  4546.5  4552.9  4570.8  4592.1  4598.5  4635.2  4639.8  4653.6  4661.2
  4666.4  4673.7  4678.9    4698  4728.5    4752  4817.5  4821.3  4863.1  4920.9
    4974    4974    5026    5026  5044.8    5222  5251.6  5270.8  5285.6  5293.1
  5297.7  5311.5  5324.7  5334.9  5338.4    5340  5343.6  5347.3  5351.1  5361.4
  5367.4  5376.1  5382.2  5387.4  5393.1  5404.3  5404.6  5410.7  5417.6  5431.7
  5437.2    5451  5457.7  5459.1  5460.6  5462.5  5466.9  5474.4  5480.9  5517.1
  291.44  287.98  287.76  286.58  285.47  284.87  282.59  282.44   281.7  281.42
  281.04  280.78  280.43  279.51  278.38  277.74  276.49  276.31  275.45  274.87
   274.9   274.9   274.9   274.9  274.93  274.54  274.95  275.38  276.35  276.51
  276.48  277.09  277.38  277.93  278.31  278.81  278.78  278.95     279  279.76
  280.37  280.53  280.84  281.26  281.91  282.64   282.6   283.1  283.29  284.54
  284.66  285.67  285.94  286.21  285.94  285.97  287.18   287.1  287.49  289.18
   248.4   248.4   248.4   248.4   248.4   248.4   248.4   248.4   248.4   248.4
   248.4   248.4   248.4   248.4   248.4   248.4   248.4   248.4   248.4   248.4
   248.4   273.4   273.4   248.4   248.4   248.4   248.4   248.4   248.4   248.4
   248.4   248.4   248.4   248.4   248.4   248.4   248.4   248.4   248.4   248.4
   248.4   248.4   248.4   248.4   248.4   248.4   248.4   248.4   248.4   248.4
   248.4   248.4   248.4   248.4   248.4   248.4   248.4   248.4   248.4   248.4
  4468.2  4546.5  4552.9  4570.8  4592.1  4598.5  4635.2  4639.8  4653.6  4661.2
  4666.4  4673.7  4678.9    4698  4728.5    4752  4817.5  4821.3  4863.1  4920.9
    4974    4974    5026    5026  5044.8    5222  5251.6  5270.8  5285.6  5293.1
  5297.7  5311.5  5324.7  5334.9  5338.4    5340  5343.6  5347.3  5351.1  5361.4
  5367.4  5376.1  5382.2  5387.4  5393.1  5404.3  5404.6  5410.7  5417.6  5431.7
  5437.2    5451  5457.7  5459.1  5460.6  5462.5  5466.9  5474.4  5480.9  5517.1
  291.44  287.98  287.76  286.58  285.47  284.87  282.59  282.44   281.7  281.42
  281.04  280.78  280.43  279.51  278.38  277.74  276.49  276.31  275.45  274.87
   274.9   274.9   274.9   274.9  274.93  274.54  274.95  275.38  276.35  276.51
  276.48  277.09  277.38  277.93  278.31  278.81  278.78  278.95     279  279.76
  280.37  280.53  280.84  281.26  281.91  282.64   282.6   283.1  283.29  284.54
  284.66  285.67  285.94  286.21  285.94  285.97  287.18   287.1  287.49  289.18
   248.4   248.4   248.4   248.4   248.4   248.4   248.4   248.4   248.4   248.4
   248.4   248.4   248.4   248.4   248.4   248.4   248.4   248.4   248.4   248.4
   248.4   273.4   273.4   248.4   248.4   248.4   248.4   248.4   248.4   248.4
   248.4   248.4   248.4   248.4   248.4   248.4   248.4   248.4   248.4   248.4
   248.4   248.4   248.4   248.4   248.4   248.4   248.4   248.4   248.4   248.4
   248.4   248.4   248.4   248.4   248.4   248.4   248.4   248.4   248.4   248.4
Pier Skew, UpSta & Num, DnSta & Num=  ,4980.5, 2 ,4980.5, 2 , 0 , 0 , 0 ,0,0
       1       1
   268.4   273.4
       1       1
  268.15   273.4
Pier Skew, UpSta & Num, DnSta & Num=  ,4993.5, 2 ,4993.5, 2 , 0 , 0 , 0 ,0,0
       1       1
   268.4   273.4
       1       1
  268.15   273.4
Pier Skew, UpSta & Num, DnSta & Num=  ,5006.5, 2 ,5006.5, 2 , 0 , 0 , 0 ,0,0
       1       1
   268.4   273.4
       1       1
  268.15   273.4
Pier Skew, UpSta & Num, DnSta & Num=  ,5019.5, 2 ,5019.5, 2 , 0 , 0 , 0 ,0,0
       1       1
   268.4   273.4
       1       1
  268.15   273.4
BR Coef= 1 , 1 , 0 ,1.25, 0 ,,,0.8,0,2,0,
WSPro=,,,, 1 ,,,, 0 ,,,, 0 ,,,,-1 ,-1 ,-1 , 0 , 0 , 0 , 0 , 0
BC Design=,, 0 ,, 0 ,,,,,,
BC HTab HWMax=296.27

Type RM Length L Ch R = 1 ,2232    ,807.0082,807.0082,807.0082
BEGIN DESCRIPTION:
Green Level West Rd D
END DESCRIPTION:
XS GIS Cut Line= 4
 2030382.6613737  739186.3824084 2029842.7256452  739218.7427518
 2029596.0130277  739208.6326445 2029377.6207107  739390.6345754
#Sta/Elev= 30
  4461.1  291.94  4565.7  283.58  4592.9  279.19    4607  278.38  4625.3  275.51
  4638.5  275.41  4651.9  273.38  4661.6  273.87  4701.2   271.8  4738.9  273.09
  4750.4  271.65  4805.3  272.42  4849.7  270.76  4909.7  271.49  4932.1   270.8
  4949.5  272.24    4974   272.6    4975  268.15    5025  268.15    5026   272.6
  5028.7  271.68  5053.3   271.5  5064.7  273.13  5075.6  270.77    5175  273.98
    5226  273.68  5428.1  284.68  5448.4  284.96    5482  288.26  5533.2  290.95
#Mann= 3 ,-1 , 0
  4461.1    .155       0    4974     .05       0    5026    .155       0
#XS Ineff= 2 , 0
       0  4902.5   273.5  5097.5       0   273.5
Permanent Ineff=
       F       F
Bank Sta=4974,5026
XS Rating Curve= 0
Exp/Cntr=0.5,0.3

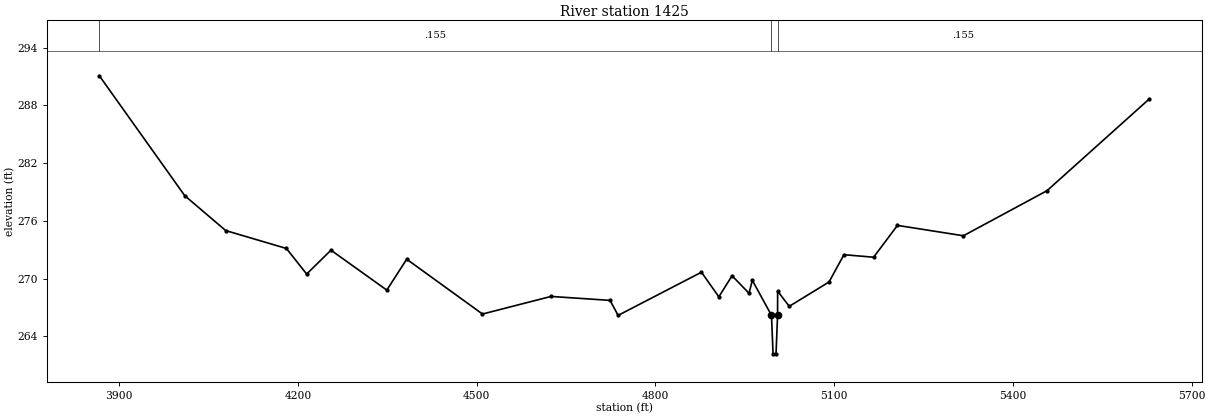
Type RM Length L Ch R = 1 ,1425    ,866.0088,866.0088,866.0088
BEGIN DESCRIPTION:
Bachelor Branch 1.0
END DESCRIPTION:
XS GIS Cut Line= 6
 2030453.6121264  738782.6181247 2030214.6695914  738579.0859653
  2030006.987388  738483.7949543 2029645.8435564  738506.1351913
 2029269.8095669  738662.5068504 2029001.7467229  739019.9206423
#Sta/Elev= 30
  3866.9  291.09  4010.2  278.62    4079  274.99  4180.8  273.13  4214.8  270.47
  4255.6  272.95  4349.3   268.8  4382.7  272.01  4509.9  266.31  4624.9  268.14
    4724  267.73  4737.5  266.17  4877.4  270.66  4906.5   268.1  4928.7  270.29
  4957.2  268.47  4962.7  269.82  4994.9  266.17  4997.5  262.17  5002.5  262.17
  5005.1  266.17  5005.2  268.69  5024.7  267.11  5091.4  269.64  5116.5  272.48
  5166.3  272.22  5206.3  275.53    5317  274.45  5457.3  279.14  5628.9  288.68
#Mann= 3 ,-1 , 0
  3866.9    .155       0  4994.9     .05       0  5005.1    .155       0
Bank Sta=4994.9,5005.1
XS Rating Curve= 0
Exp/Cntr=0.3,0.1