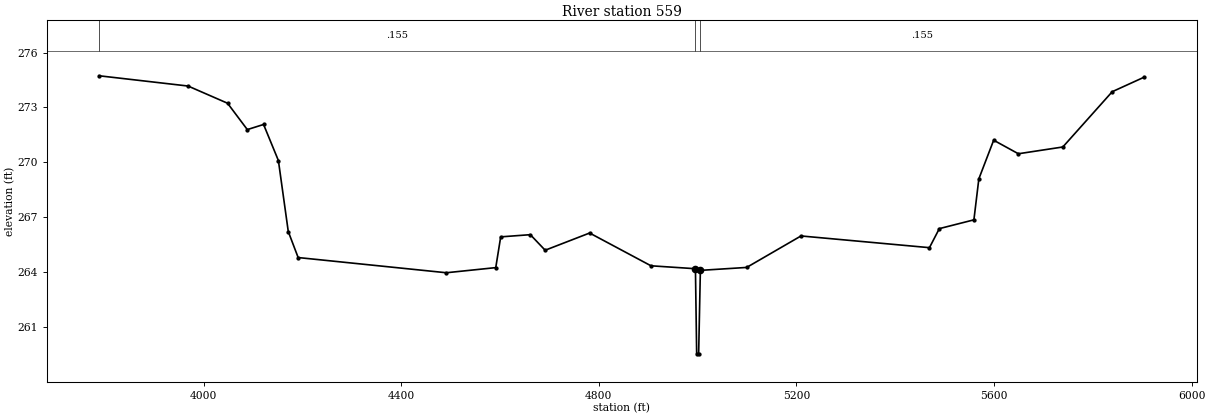
HEC-RAS study Bachelor_Branch_ADJ.prj: Bachelor Branch (B28, S6) LDS Adjusted

--- Bachelor_Branch_ADJ.g01 (geometry) --- (continued)

Type RM Length L Ch R = 1 ,559     ,0,0,0
BEGIN DESCRIPTION:
Bachelor Branch 0.5
END DESCRIPTION:
XS GIS Cut Line= 5
 2030104.5084226  738295.1929533 2029826.8954773  738173.9816673
 2029205.2188816  737802.5377265  2028982.346517  737923.7490125
 2028919.7958534  738756.5678483
#Sta/Elev= 30
  3788.4  274.73  3968.4  274.17  4048.4  273.23  4088.4  271.79  4121.3  272.07
  4151.3   270.1  4171.3  266.22  4191.3   264.8  4491.3  263.97  4591.3  264.25
  4601.3  265.93  4661.3  266.05  4691.3   265.2  4781.3  266.14  4905.5  264.35
  4995.5  264.19    4998  259.54    5002  259.54  5005.5   264.1  5099.2  264.26
  5209.2  265.98  5469.2  265.34  5489.2  266.38  5559.2  266.86  5569.2   269.1
  5599.2  271.21  5649.2  270.47  5739.2  270.84  5839.2  273.86  5904.3  274.66
#Mann= 3 ,-1 , 0
  3788.4    .155       0  4995.5     .05       0  5005.5    .155       0
Bank Sta=4995.5,5005.5
XS Rating Curve= 0
Exp/Cntr=0.3,0.1

Chan Stop Cuts=-1