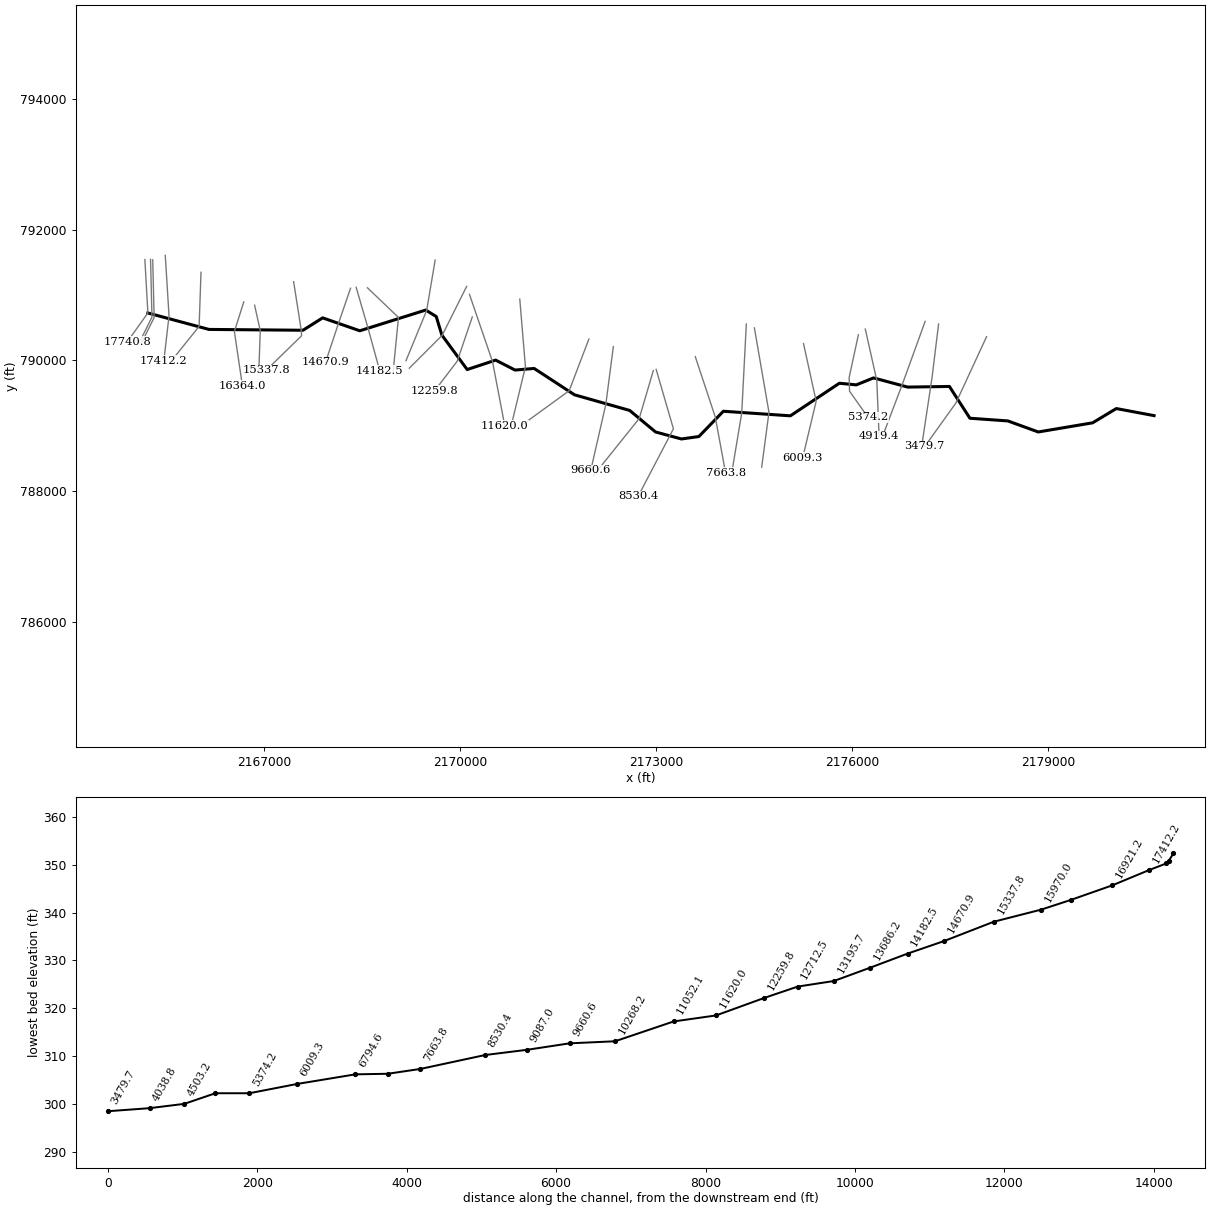
--- Cedar_Fork_fut.prj (project) ---

Proj Title=Cedar Fork (B10, S15)
Current Plan=p01
Default Exp/Contr=.3,.1
English Units
Geom File=g01
Flow File=f01
Flow File=f02
Plan File=p01
Plan File=p02
Y Axis Title=Elevation
X Axis Title(PF)=Main Channel Distance
X Axis Title(XS)=Station
BEGIN DESCRIPTION:
####(Watershed Name)####
CEDAR FORK (B10, S15)
HCFCD Unit X###-##-##
(Flood Hazard, Floodway) Model
10, 2, 1, 0.2% Event
Filename:  N:\NC_flood\60138\Approximates\Eng\Little_River\ENG\Cedar Fork\Cedar Fork (B10, S15).prj
Prepared by:  ________     Date: ________
Reviewed by:  ________     Date: ________
STATUS (Draft RAS, SVSQ, FINAL)
END DESCRIPTION:
DSS Export Rating Curves= 0
DSS Export Rating Curve Sorted= 0
DSS Export Volume Flow Curves= 0
DXF OffsetX= 0
DXF OffsetY= 0
DXF ScaleX= 1
DXF ScaleY= 10

--- Cedar_Fork_fut.p01 (plan) ---

Plan Title=Floodway
Version=Version 3.0.1  Mar 2001
Short Identifier=Plan01
Geom File=g01
Flow File=f01
Subcritical Flow
K Sum by GR= 0
Std Step Tol= 0.01
Critical Tol= 0.01
Num of Std Step Trials= 20
Max Error Tol= 0.3
Flow Tol Ratio= 0.001
Split Flow NTrial= 30
Split Flow Tol= 0.02
Split Flow Ratio= 0.02
Log Output Level= 0
Friction Slope Method= 1
Unsteady Friction Slope Method= 2
Parabolic Critical Depth
Global Vel Dist= 0 , 0 , 0
Global Log Level= 0
CheckData=True
Encroach Param=-1 ,10,10, 2
Encroach River=CedarForkB10S15
Encroach Reach=Reach - 1
Encroach Node=17740.8
       1  4796.9 5127.31
Encroach Node=17678.6
       1    4796    5131
Encroach Node=17661.6
       1    4796    5131
Encroach Node=17644.6
       1    4796    5131
Encroach Node=17412.2
       1 4931.61 5032.76
Encroach Node=16921.2
       1    4950 5072.65
Encroach Node=16364.0
       1    4950 5141.21
Encroach Node=15970.0
       1    4950 5132.75
Encroach Node=15337.8
       1  4934.5 5077.67
Encroach Node=14670.9
       1    4960 5098.06
Encroach Node=14182.5
       1    4960 5126.17
Encroach Node=13686.2
       1    4950    5050
Encroach Node=13195.7
       1    4950 5088.75
Encroach Node=12712.5
       1 4867.48    5050
Encroach Node=12259.8
       1 4951.83    5040
Encroach Node=11620.0
       1 4723.21    5050
Encroach Node=11052.1
       1 4868.07    5050
Encroach Node=10268.2
       1    4800    5100
Encroach Node=9660.6
       1    4790    5140
Encroach Node=9087.0
       1    4938    5120
Encroach Node=8530.4
       1 4752.36 5084.09
Encroach Node=7663.8
       1 4755.74 5043.92
Encroach Node=7226.5
       1 4747.66  5005.5
Encroach Node=6794.6
       1 4766.16 5184.58
Encroach Node=6009.3
       1 4865.62 5182.93
Encroach Node=5374.2
       1    4831    5100
Encroach Node=4919.4
       1 4920.41  5005.3
Encroach Node=4503.2
       1 4712.17 5018.31
Encroach Node=4038.8
       1 4827.99 5027.81
Encroach Node=3479.7
       1  4677.4  5008.7
Encroach Node=3044.1
       1    4765    5106
Encroach Node=2260.7
       1    4825    5075
Encroach Node=1644.4
       1    4812    5182
Encroach Node=906.6
       1 4897.48  5070.4
Encroach Node=884.1
       1 4897.48  5070.4
Encroach Node=861.6
       1 4897.48  5070.4
Encroach Node=343.8
       1    4958  5025.8
Encroach Node=321.3
       1    4958  5025.8
Encroach Node=298.8
       1    4958  5025.8
Encroach Node=158.4
       1    4945    5040
Computation Interval=1HOUR
Output Interval=1HOUR
Run HTab= 0
Run UNet= 0
Run PostProcess= 0
UNET Theta= 1
UNET ZTol= 0.02
UNET ZSATol= 0.1
UNET MxIter= 20
UNET MaxInSteps= 20
UNET DtIC= 0
UNET DtMin= 0
UNET MaxCRTS= 20
UNET WFStab= 2
UNET SFStab= 1
UNET WFX= 1
UNET SFX= 1
UNET Convert EG Bridges=-1
UNET Use Existing IB Tables=-1
Instantaneous Interval=1HOUR
Write IC File= 0
Write Velocity= 0
Write Detailed= 0

--- Cedar_Fork_fut.p02 (plan) ---

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Plan Title=100yr Future
Short Identifier=Plan02
Geom File=g01
Flow File=f02
Interactive Comp Mode
Encroach Param= -1, 0, 0, 0

--- Cedar_Fork_fut.f01 (steady flow) ---

Flow Title= Floodway
Number of Profiles= 2
Profile Names=100-year,Floodway
River Rch & RM=CedarForkB10S15,Reach - 1,17740.8
    1307    1307
River Rch & RM=CedarForkB10S15,Reach - 1,16364
    1995    1995
River Rch & RM=CedarForkB10S15,Reach - 1,10268.2
    2219    2219
River Rch & RM=CedarForkB10S15,Reach - 1,7663.8
    2316    2316
River Rch & RM=CedarForkB10S15,Reach - 1,3479.7
    2368    2368
Boundary for River Rch & Prof#=CedarForkB10S15,Reach - 1, 1
Up Type= 0
Dn Type= 3
Dn Slope= 0.00730
Boundary for River Rch & Prof#=CedarForkB10S15,Reach - 1, 2
Up Type= 0
Dn Type= 3
Dn Slope= 0.00730

--- Cedar_Fork_fut.f02 (steady flow) ---

Flow Title= 100yr Future
Number of Profiles= 2
Profile Names=Q-Existing,Q-Future
River Rch & RM=CedarForkB10S15,Reach - 1,17740.8
    1307    1794
River Rch & RM=CedarForkB10S15,Reach - 1,16364
    1995    2519
River Rch & RM=CedarForkB10S15,Reach - 1,10268.2
    2219    2760
River Rch & RM=CedarForkB10S15,Reach - 1,7663.8
    2316    2849
River Rch & RM=CedarForkB10S15,Reach - 1,3479.7
    2368    2904
Boundary for River Rch & Prof#=CedarForkB10S15,Reach - 1, 1
Up Type= 0
Dn Type= 3
Dn Slope= 0.00730
Boundary for River Rch & Prof#=CedarForkB10S15,Reach - 1, 2
Up Type= 0
Dn Type= 3
Dn Slope= 0.00730

--- Cedar_Fork_fut.g01 (geometry) ---

Geom Title=Geom 01 by CodeH2 for Windows

River Reach=CedarForkB10S15,Reach - 1
Reach XY= 30
      2180627.25       789153.95       2180049.1       789262.28
      2179686.35       789043.81      2178853.68       788903.66
      2178387.88       789072.67      2177806.66       789113.89
      2177492.73       789600.66      2176854.52       789590.84
      2176330.87       789731.57      2176067.12       789625.03
      2175807.43       789649.76       2175057.2       789150.99
       2174030.8       789221.06      2173655.68       788833.58
      2173387.74       788796.48      2172992.02       788903.66
       2172596.3       789233.43      2171751.26       789472.51
      2171132.94       789876.48      2170840.27       789851.75
      2170543.48       790004.27      2170107.31       789859.73
      2169719.83       790387.37      2169633.26       790671.79
       2169472.5       790770.72      2168462.58       790453.32
      2167893.73       790651.18      2167592.81       790461.56
      2166152.64       790474.12      2165216.47          790726

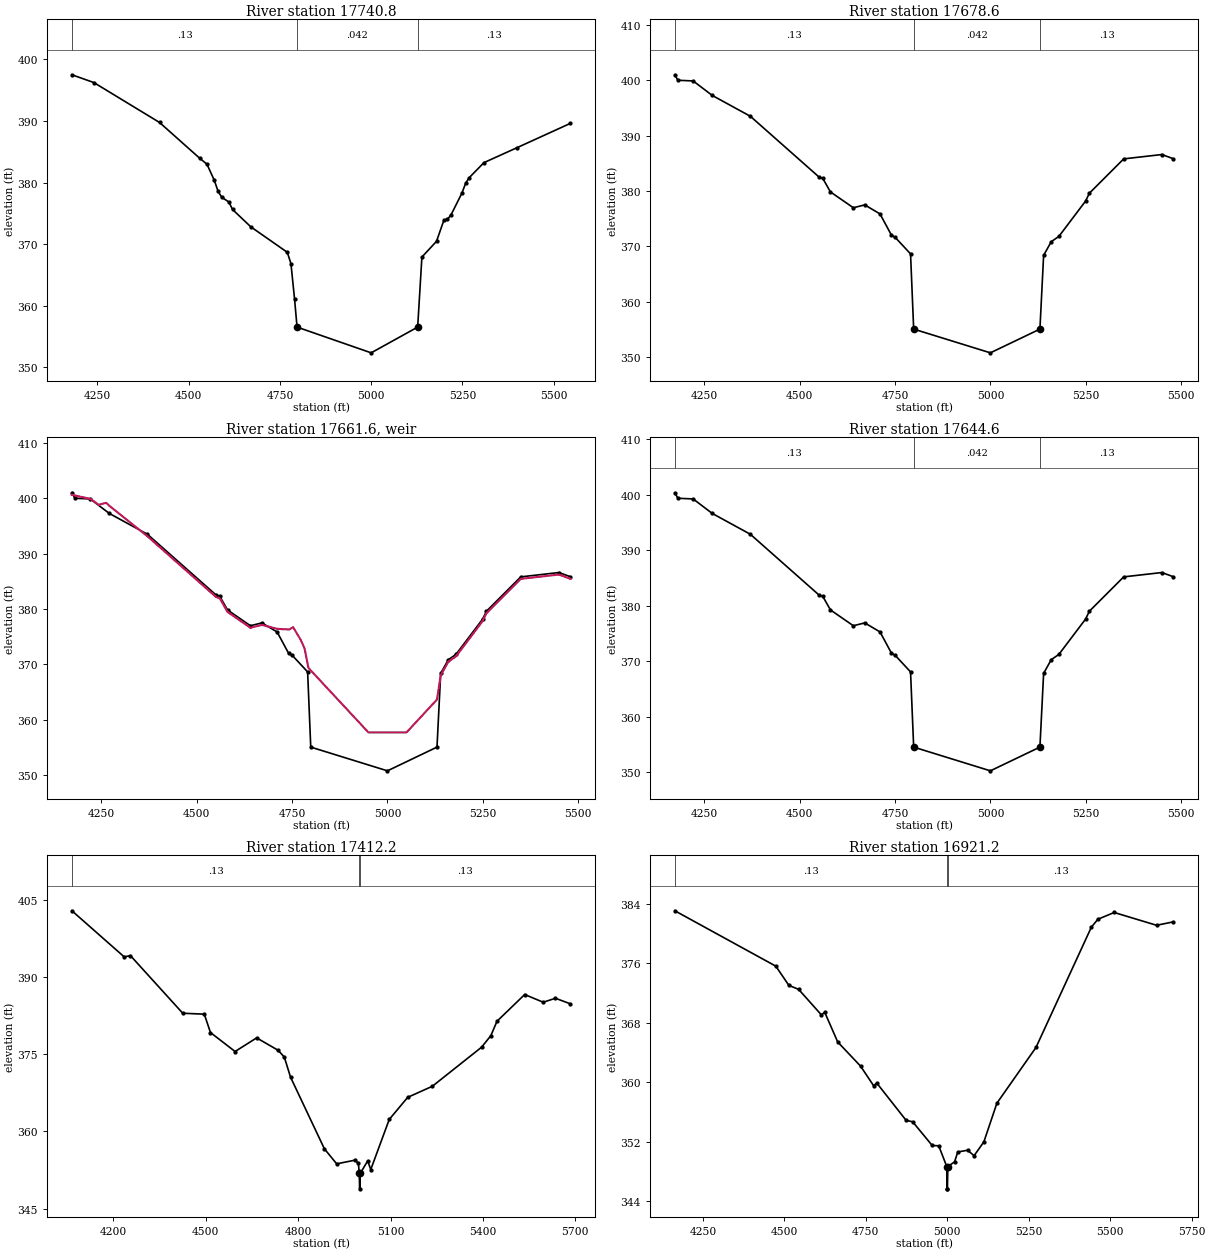
Type RM Length L Ch R = 1 ,17740.8,62.2,62.2,62.2
XS GIS Cut Line= 3
      2165171.00       791543.89      2165217.16       790726.53
      2164899.45       790281.19
BEGIN DESCRIPTION:
Cedar Fork (B10, S15) 37.0
END DESCRIPTION:
#Sta/Elev= 28
  4180.2  397.49  4240.2  396.23  4420.2  389.75  4530.2  383.94  4550.2  382.97
  4570.2  380.36  4580.2  378.64  4590.2  377.63  4610.2  376.83  4620.2  375.62
  4670.2  372.81  4770.2  368.67  4780.2  366.83  4790.2  361.01  4796.9  356.53
  4999.9  352.35 5127.31  356.53  5138.9   367.9  5178.9  370.45  5198.9  373.84
  5208.9  374.02  5218.9  374.77  5248.9  378.33  5258.9  379.92  5268.9  380.81
  5308.9  383.23  5398.9  385.64  5545.9  389.61
#Mann= 3 , 1 , 0
 4180.20    0.13       0  4796.9   0.042       0 5127.31    0.13       0
Bank Sta=4796.90,5127.31
Exp/Cntr=0.5,0.3

Type RM Length L Ch R = 1 ,17678.6,34,34,34
XS GIS Cut Line= 3
      2165257.97       791547.03      2165279.57       790661.32
      2165091.21       790284.61
BEGIN DESCRIPTION:
Upstream Section of Bridge/Culvert/Weir
END DESCRIPTION:
#Sta/Elev= 25
  4172.6  400.95  4180.6  399.96  4220.6  399.84  4270.6  397.23  4370.6  393.47
  4550.6  382.52  4560.6  382.26  4580.6  379.83  4640.6  376.98  4670.6  377.49
  4710.6  375.86  4740.6  372.03  4750.6  371.62  4790.6  368.66 4798.81   355.1
  4999.9  350.82 5129.81   355.1  5139.5  368.39  5159.5  370.86  5179.5  371.81
  5249.5  378.18  5259.5   379.6  5349.5  385.79  5449.5  386.57  5479.8  385.81
#Mann= 3 , 1 , 0
 4172.60    0.13       0 4798.81   0.042       0 5129.81    0.13       0
#XS Ineff= 2 , 0
       0    4788     362    5140       0     362
Bank Sta=4798.81,5129.81
Exp/Cntr=0.5,0.3

Type RM Length L Ch R = 5 ,17661.6,,,
BEGIN DESCRIPTION:
Dam_2-TOR
Structure ID: Dam_2
Approximate Survey Structure
END DESCRIPTION:
#Inline Weir SE= 28
  4172.6  400.58  4222.6  399.82  4242.6  398.79  4262.6  399.14  4270.6  398.61
  4370.6  393.11  4550.6  382.16  4560.6   381.9  4580.6  379.47  4640.6  376.62
  4670.6  377.13  4710.6  376.42  4742.6   376.3  4752.6  376.72  4772.6  374.42
  4782.6  372.89  4792.6  369.39    4950  357.75    5050  357.75 5129.81  363.68
  5139.5  368.03  5159.5   370.5  5179.5  371.45  5249.5  377.82  5259.5  379.24
  5349.5  385.43  5449.5  386.21  5479.8  385.44
IW Dist,WD,Coef,Skew,MaxSub,Min_El,Is_Ogee,SpillHt,DesHd
10.0,14.0,3.0,,0.95,, 0 ,,,1.0,1.0,

Type RM Length L Ch R = 1 ,17644.6,232.4,232.4,232.4
XS GIS Cut Line= 3
      2165291.31       791540.37      2165312.91       790654.66
      2165124.55       790277.94
BEGIN DESCRIPTION:
Downstream Section of Bridge/Culvert/Weir
END DESCRIPTION:
#Sta/Elev= 25
  4172.6  400.38  4180.6  399.39  4220.6  399.27  4270.6  396.66  4370.6   392.9
  4550.6  381.95  4560.6  381.69  4580.6  379.26  4640.6  376.41  4670.6  376.92
  4710.6  375.29  4740.6  371.46  4750.6  371.05  4790.6  368.09 4798.81  354.53
  4999.9  350.25 5129.81  354.53  5139.5  367.82  5159.5  370.29  5179.5  371.24
  5249.5  377.61  5259.5  379.03  5349.5  385.22  5449.5     386  5479.8  385.24
#Mann= 3 , 1 , 0
 4172.60    0.13       0 4798.81   0.042       0 5129.81    0.13       0
#XS Ineff= 2 , 0
       0    4788     362    5140       0     362
Bank Sta=4798.81,5129.81
Exp/Cntr=0.5,0.3

Type RM Length L Ch R = 1 ,17412.2,491,491,491
XS GIS Cut Line= 3
      2165483.46       791608.51      2165541.07       790679.59
      2165461.86       789995.51
BEGIN DESCRIPTION:
Cedar Fork (B10, S15) 36.0
END DESCRIPTION:
#Sta/Elev= 30
  4065.1  402.91  4235.1  393.94  4255.1   394.2  4425.1  382.99  4495.1  382.81
  4515.1  379.24  4595.1  375.55  4665.1   378.2  4735.1  375.78  4755.1  374.45
  4775.1  370.58  4885.1  356.64  4925.1  353.71  4985.1  354.43  4995.8  353.78
  4998.3  351.85  4999.8  348.85  5001.7  351.85  5025.8  354.29  5035.8   352.6
  5095.8  362.34  5155.8  366.64  5235.8  368.79  5395.8  376.39  5425.8  378.63
  5445.8  381.43  5535.8  386.63  5595.8  385.13  5635.8   385.9  5684.5  384.81
#Mann= 3 , 1 , 0
 4065.10    0.13       0  4998.3   0.042       0  5001.7    0.13       0
Bank Sta=4998.30,5001.70
Exp/Cntr=0.3,0.1

Type RM Length L Ch R = 1 ,16921.2,557.2,557.2,557.2
XS GIS Cut Line= 3
      2166030.73       791349.28      2166001.93       790521.17
      2165562.67       789973.90
BEGIN DESCRIPTION:
Cedar Fork (B10, S15) 35.0
END DESCRIPTION:
#Sta/Elev= 30
  4163.6  383.07  4473.6  375.62  4513.6  373.04  4543.6   372.5  4613.6  369.06
  4623.6  369.43  4663.6  365.42  4733.6  362.18  4773.6  359.55  4783.6  359.89
  4873.6  354.88  4893.6  354.69  4953.6   351.5  4973.6  351.46  4998.3  348.67
  4999.8  345.67  5000.2  345.67  5001.7  348.67  5022.2   349.3  5032.2  350.63
  5062.2  350.86  5082.2  350.13  5112.2  351.99  5152.2  357.19  5272.2  364.69
  5442.2  380.87  5462.2  381.93  5512.2  382.84  5642.2  381.12    5694  381.58
#Mann= 3 , 1 , 0
 4163.60    0.13       0  4998.3   0.042       0  5001.7    0.13       0
Bank Sta=4998.30,5001.70
Exp/Cntr=0.3,0.1

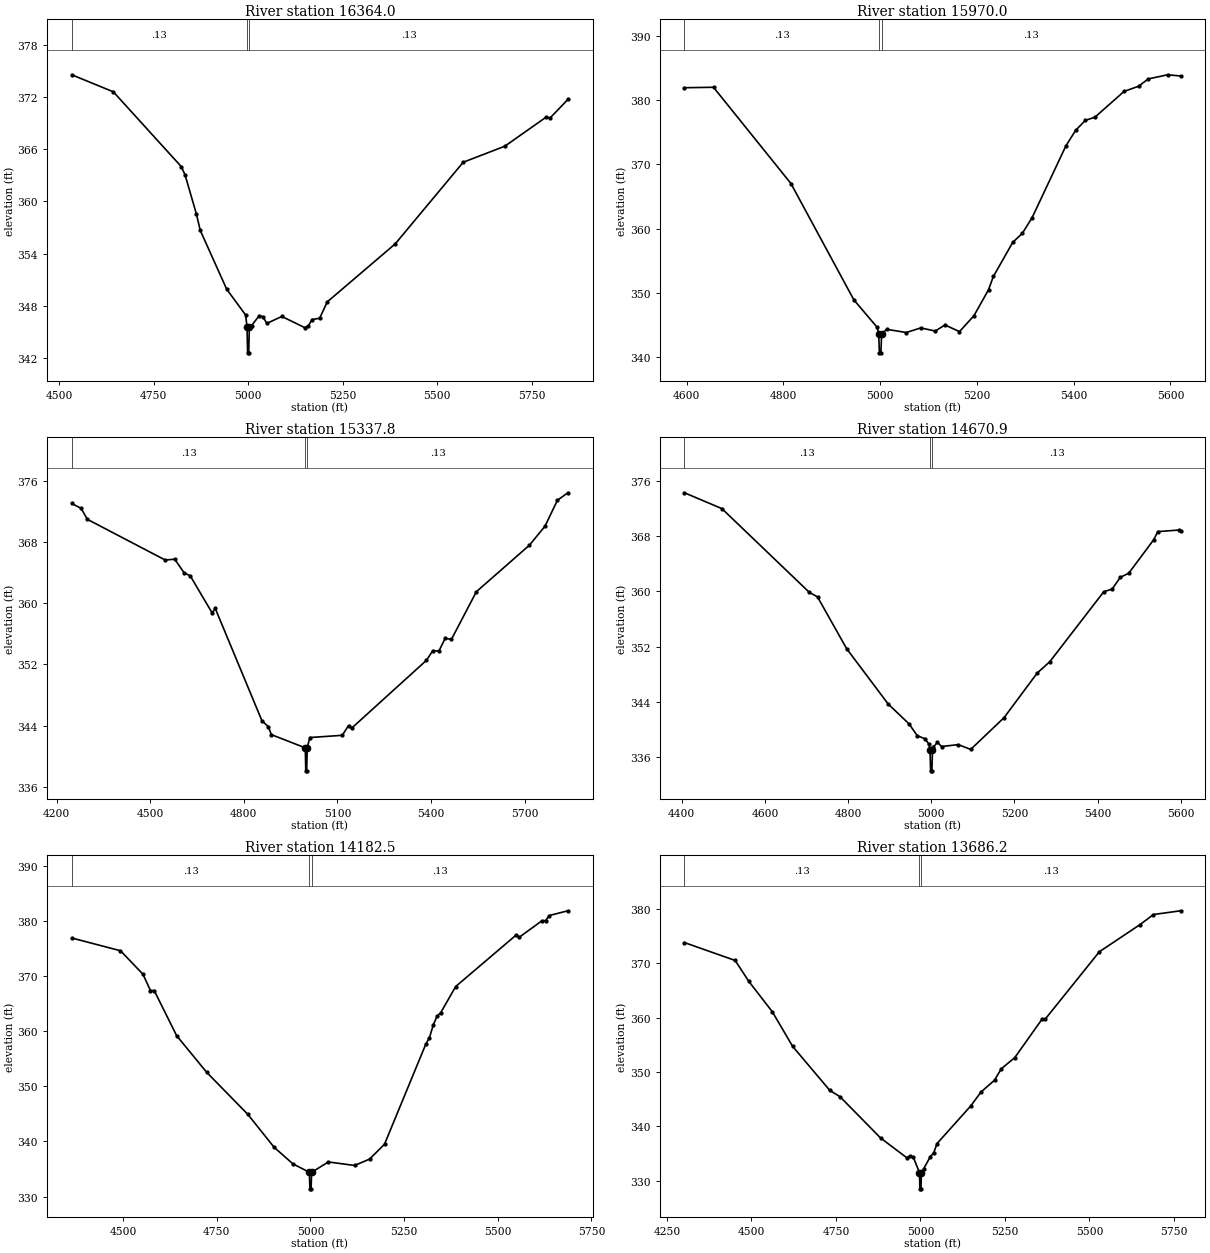
Type RM Length L Ch R = 1 ,16364.0,394,394,394
XS GIS Cut Line= 3
      2166686.01       790895.62      2166542.00       790441.96
      2166664.41       789613.86
BEGIN DESCRIPTION:
Cedar Fork (B10, S15) 34.0
END DESCRIPTION:
#Sta/Elev= 29
  4533.2  374.56  4643.2   372.6  4823.2     364  4833.2  363.03  4863.2  358.53
  4873.2  356.68  4943.2  349.92  4993.2  346.96    4997  345.61  4998.5  342.61
  5001.6  342.61  5003.1  345.61  5003.2  345.74  5009.2  345.75  5029.2  346.87
  5039.2  346.76  5049.2  345.99  5089.2  346.79  5149.2  345.52  5159.2  345.71
  5169.2  346.44  5189.2  346.58  5209.2  348.46  5389.2  355.13  5569.2  364.51
  5679.2  366.35  5789.2  369.71  5799.2   369.6  5846.3  371.73
#Mann= 3 , 1 , 0
 4533.20    0.13       0    4997   0.042       0  5003.1    0.13       0
Bank Sta=4997.00,5003.10
Exp/Cntr=0.3,0.1

Type RM Length L Ch R = 1 ,15970.0,632.2,632.2,632.2
XS GIS Cut Line= 3
      2166851.63       790845.21      2166938.04       790456.37
      2166916.44       789829.89
BEGIN DESCRIPTION:
Cedar Fork (B10, S15) 33.0
END DESCRIPTION:
#Sta/Elev= 30
  4595.7  381.97  4655.7  382.04  4815.7  367.02  4945.7  348.87    4994  344.57
    4997   343.6  4998.5   340.6  5001.6   340.6  5003.1   343.6    5014  344.27
    5054  343.77    5084  344.49    5114     344    5134  344.95    5164  343.91
    5194  346.41    5224  350.45    5234  352.52    5274  357.83    5294  359.27
    5314  361.69    5384  372.91    5404  375.32    5424  376.87    5444  377.38
    5504  381.39    5534   382.2    5554  383.34    5594  383.99  5620.9   383.8
#Mann= 3 , 1 , 0
 4595.70    0.13       0    4997   0.042       0  5003.1    0.13       0
Bank Sta=4997.00,5003.10
Exp/Cntr=0.3,0.1

Type RM Length L Ch R = 1 ,15337.8,666.9,666.9,666.9
XS GIS Cut Line= 4
      2167449.31       791205.26      2167564.52       790470.77
      2167571.72       790377.16      2167031.66       789851.49
BEGIN DESCRIPTION:
Cedar Fork (B10, S15) 32.0
END DESCRIPTION:
#Sta/Elev= 30
  4248.2     373  4278.2  372.36  4298.2  370.93  4548.2  365.61  4578.2  365.73
  4608.2  363.96  4628.2  363.54  4698.2  358.71  4708.2   359.3  4858.2   344.6
  4878.2  343.87  4888.2  342.81    4997  341.08  4998.5  338.08  5001.5  338.08
    5003  341.08  5011.7  342.43  5115.6  342.72  5135.6  343.99  5145.6  343.65
  5385.6  352.52  5405.6  353.77  5425.6  353.74  5445.6  355.39  5465.6  355.25
  5545.6  361.48  5715.6  367.55  5765.6  370.03  5805.6  373.43  5839.2   374.4
#Mann= 3 , 1 , 0
 4248.20    0.13       0    4997   0.042       0    5003    0.13       0
Bank Sta=4997.00,5003.00
Exp/Cntr=0.3,0.1

Type RM Length L Ch R = 1 ,14670.9,488.4,488.4,488.4
XS GIS Cut Line= 3
      2168320.62       791104.45      2168133.39       790557.18
      2167938.97       789973.90
BEGIN DESCRIPTION:
Cedar Fork (B10, S15) 31.0
END DESCRIPTION:
#Sta/Elev= 30
  4406.5  374.25  4496.5  371.96  4706.5  359.86  4726.5  359.19  4796.5   351.7
  4896.5  343.69  4946.5  340.83  4966.5  339.11  4984.9  338.67  4994.9  337.84
    4997  337.03  4998.5  334.03  5001.5  334.03    5003  337.03  5004.9  337.48
  5014.9  338.13  5024.9  337.55  5064.9  337.82  5094.9  337.13  5174.9  341.71
  5254.9  348.18  5284.9   349.8  5414.9  359.94  5434.9  360.32  5454.9  362.03
  5474.9  362.61  5534.9  367.45  5544.9  368.63  5594.9  368.86  5599.7  368.73
#Mann= 3 , 1 , 0
 4406.50    0.13       0    4997   0.042       0    5003    0.13       0
Bank Sta=4997.00,5003.00
Exp/Cntr=0.3,0.1

Type RM Length L Ch R = 1 ,14182.5,496.3,496.3,496.3
XS GIS Cut Line= 3
      2168407.03       791118.85      2168587.05       790499.57
      2168767.07       789844.29
BEGIN DESCRIPTION:
Cedar Fork (B10, S15) 30.0
END DESCRIPTION:
#Sta/Elev= 30
  4362.8  376.92  4492.8  374.61  4552.8  370.35  4572.8  367.39  4582.8  367.39
  4642.8  359.19  4722.8  352.56  4832.8  344.92  4902.8  338.96  4952.8  335.96
    4997  334.41  4998.5  331.41  5001.6  331.41  5003.1  334.41  5047.7  336.29
  5117.7  335.65  5157.7   336.8  5197.7  339.51  5307.7  357.63  5317.7  358.85
  5327.7  361.12  5337.7  362.72  5347.7  363.37  5387.7  368.12  5547.7  377.38
  5557.7  377.07  5617.7  380.04  5627.7  380.08  5637.7     381  5687.3  381.86
#Mann= 3 , 1 , 0
 4362.80    0.13       0    4997   0.042       0  5003.1    0.13       0
Bank Sta=4997.00,5003.10
Exp/Cntr=0.3,0.1

Type RM Length L Ch R = 1 ,13686.2,490.5,490.5,490.5
XS GIS Cut Line= 3
      2168579.85       791111.65      2169055.11       790657.99
      2168975.90       789851.49
BEGIN DESCRIPTION:
Cedar Fork (B10, S15) 29.0
END DESCRIPTION:
#Sta/Elev= 30
  4302.1  373.79  4452.1   370.5  4492.1  366.68  4562.1  361.05  4622.1  354.69
  4732.1  346.59  4762.1  345.44  4882.1  337.85  4959.1  334.23  4969.1  334.55
  4979.1  334.29    4997  331.49  4998.5  328.49  5001.5  328.49    5003  331.49
  5009.1  332.12  5029.1   334.4  5039.1  335.09  5049.1  336.82  5149.1  343.76
  5179.1   346.3  5219.1  348.47  5239.1  350.57  5279.1  352.64  5359.1  359.65
  5369.1  359.71  5529.1   372.1  5649.1  377.08  5689.1  378.95  5769.5  379.64
#Mann= 3 , 1 , 0
 4302.10    0.13       0    4997   0.042       0    5003    0.13       0
Bank Sta=4997.00,5003.00
Exp/Cntr=0.3,0.1

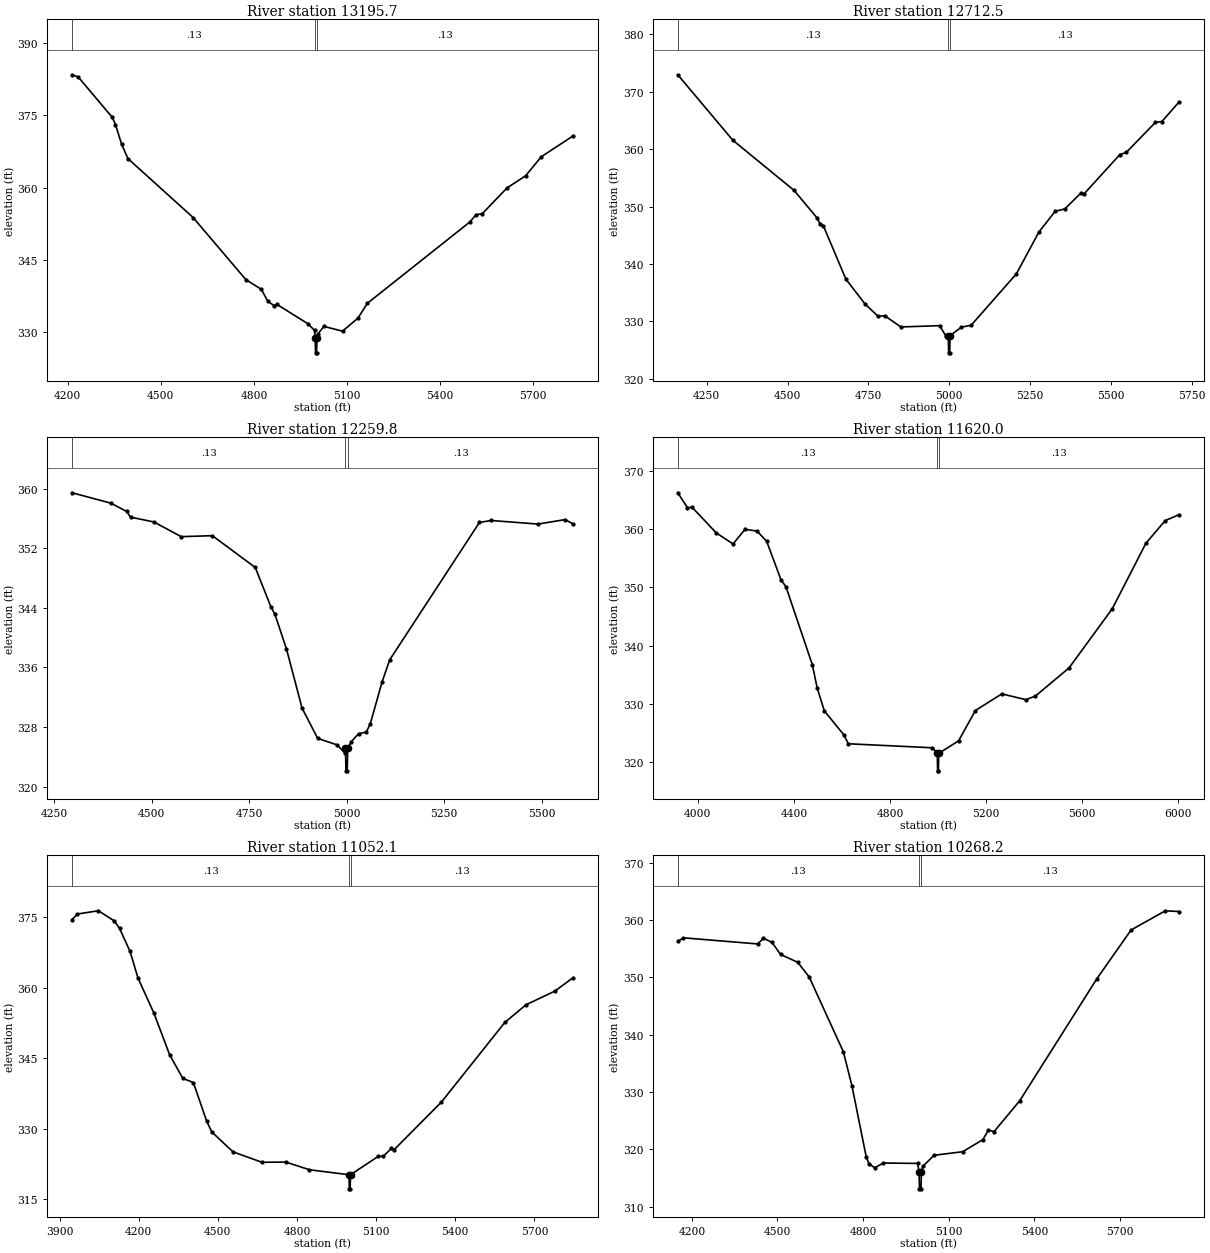
Type RM Length L Ch R = 1 ,13195.7,483.2,483.2,483.2
XS GIS Cut Line= 3
      2169616.78       791536.50      2169487.16       790766.00
      2169170.32       789995.51
BEGIN DESCRIPTION:
Cedar Fork (B10, S15) 28.0
END DESCRIPTION:
#Sta/Elev= 30
  4213.9  383.42  4233.9  382.96  4343.9  374.55  4353.9  373.06  4373.9  368.96
  4393.9  366.02  4603.9  353.78  4773.9  340.88  4823.9  338.86  4843.9  336.44
  4863.9  335.51  4873.9  335.74  4973.9  331.72  4995.2  330.32    4997  328.68
  4998.5  325.68  5001.5  325.68    5003  328.68  5005.2  329.52  5025.2  331.17
  5085.2  330.18  5135.2   332.9  5165.2  335.96  5495.2  352.84  5515.2  354.36
  5535.2  354.56  5615.2  359.93  5675.2  362.45  5725.2  366.38  5828.3  370.74
#Mann= 3 , 1 , 0
 4213.90    0.13       0    4997   0.042       0    5003    0.13       0
Bank Sta=4997.00,5003.00
Exp/Cntr=0.3,0.1

Type RM Length L Ch R = 1 ,12712.5,452.7,452.7,452.7
XS GIS Cut Line= 3
      2170099.24       791133.25      2169724.79       790384.36
      2169220.73       789880.29
BEGIN DESCRIPTION:
Cedar Fork (B10, S15) 27.0
END DESCRIPTION:
#Sta/Elev= 30
  4160.6  372.97  4330.6  361.58  4520.6  352.81  4590.6  348.08  4600.6  346.97
  4610.6   346.7  4680.6  337.36  4740.6  332.97  4780.6  330.87  4800.6  330.99
  4850.6  329.03  4970.6  329.26  4990.6  327.39    4997  327.52  4998.5  324.52
  5001.5  324.52    5003  327.52  5037.9     329  5067.9  329.32  5207.9  338.28
  5277.9   345.6  5327.9  349.18  5357.9   349.6  5407.9  352.39  5417.9  352.26
  5527.9  359.06  5547.9  359.45  5637.9  364.67  5657.9  364.82  5710.7  368.21
#Mann= 3 , 1 , 0
 4160.60    0.13       0    4997   0.042       0    5003    0.13       0
Bank Sta=4997.00,5003.00
Exp/Cntr=0.3,0.1

Type RM Length L Ch R = 1 ,12259.8,639.8,639.8,639.8
XS GIS Cut Line= 3
      2170185.65       790665.19      2169955.22       789988.31
      2169609.58       789534.65
BEGIN DESCRIPTION:
Cedar Fork (B10, S15) 26.0
END DESCRIPTION:
#Sta/Elev= 30
  4295.8  359.45  4395.8  358.05  4435.8  356.94  4445.8  356.18  4505.8  355.53
  4575.8  353.56  4655.8  353.69  4765.8  349.42  4805.8  344.15  4815.8  343.19
  4845.8  338.49  4885.8  330.54  4925.8  326.48  4975.8   325.6  4995.8   324.5
    4997  325.12  4998.5  322.12  5001.5  322.12    5003  325.12  5010.8  325.97
  5030.8   327.1  5050.8  327.33  5060.8  328.44  5090.8  334.02  5110.8  337.04
  5340.8  355.47  5370.8  355.73  5490.8  355.25  5560.8  355.85  5581.2  355.26
#Mann= 3 , 1 , 0
 4295.80    0.13       0    4997   0.042       0    5003    0.13       0
Bank Sta=4997.00,5003.00
Exp/Cntr=0.3,0.1

Type RM Length L Ch R = 1 ,11620.0,567.9,567.9,567.9
XS GIS Cut Line= 3
      2170142.45       791010.83      2170495.29       789981.11
      2170682.51       789001.78
BEGIN DESCRIPTION:
Cedar Fork (B10, S15) 25.0
END DESCRIPTION:
#Sta/Elev= 30
  3917.1  366.26  3957.1  363.71  3977.1  363.75  4077.1  359.37  4147.1  357.47
  4197.1  359.99  4247.1  359.67  4287.1  357.93  4347.1  351.25  4367.1  350.14
  4477.1  336.72  4497.1  332.75  4527.1  328.78  4607.1  324.73  4627.1  323.14
  4977.1  322.45    4997  321.49  4998.5  318.49  5001.5  318.49    5003  321.49
  5085.6  323.64  5155.6  328.85  5265.6  331.71  5365.6  330.72  5405.6  331.34
  5545.6  336.18  5725.6  346.36  5865.6  357.61  5945.6  361.48  6002.7  362.49
#Mann= 3 , 1 , 0
 3917.10    0.13       0    4997   0.042       0    5003    0.13       0
Bank Sta=4997.00,5003.00
Exp/Cntr=0.3,0.1

Type RM Length L Ch R = 1 ,11052.1,783.9,783.9,783.9
XS GIS Cut Line= 3
      2170912.94       790938.83      2170999.35       789901.90
      2170797.73       789066.59
BEGIN DESCRIPTION:
Cedar Fork (B10, S15) 24.0
END DESCRIPTION:
#Sta/Elev= 30
  3947.2  374.52  3967.2  375.71  4047.2   376.4  4107.2  374.25  4127.2  372.67
  4167.2  367.74  4197.2  362.09  4257.2  354.67  4317.2  345.76  4367.2  340.72
  4407.2  339.85  4457.2  331.69  4477.2  329.32  4557.2  325.11  4667.2  322.88
  4757.2  322.93  4847.2  321.29    4997  320.23  4998.5  317.23  5001.5  317.23
    5003  320.23  5107.7  324.13  5127.7  324.19  5157.7  325.82  5167.7  325.53
  5347.7  335.71  5587.7  352.63  5667.7  356.38  5777.7  359.31    5847  362.17
#Mann= 3 , 1 , 0
 3947.20    0.13       0    4997   0.042       0    5003    0.13       0
Bank Sta=4997.00,5003.00
Exp/Cntr=0.3,0.1

Type RM Length L Ch R = 1 ,10268.2,607.6,607.6,607.6
XS GIS Cut Line= 3
      2171971.47       790326.75      2171669.04       789534.65
      2170934.54       789001.78
BEGIN DESCRIPTION:
Cedar Fork (B10, S15) 23.0
END DESCRIPTION:
#Sta/Elev= 30
  4150.8  356.27  4170.8  356.91  4430.8  355.84  4450.8  356.83  4480.8  356.11
  4510.8     354  4570.8  352.64  4610.8   350.1  4730.8  337.01  4760.8  331.07
  4810.8  318.67  4820.8  317.43  4840.8  316.77  4870.8   317.6  4990.8  317.53
  4995.9  316.09  4997.4  313.09  5002.6  313.09  5004.1  316.09  5008.7  317.01
  5048.7  318.95  5148.7  319.57  5218.7  321.66  5238.7  323.31  5258.7  323.09
  5348.7  328.48  5618.7  349.77  5738.7  358.29  5858.7  361.63  5906.1   361.5
#Mann= 3 , 1 , 0
 4150.80    0.13       0  4995.9   0.042       0  5004.1    0.13       0
Bank Sta=4995.90,5004.10
Exp/Cntr=0.3,0.1

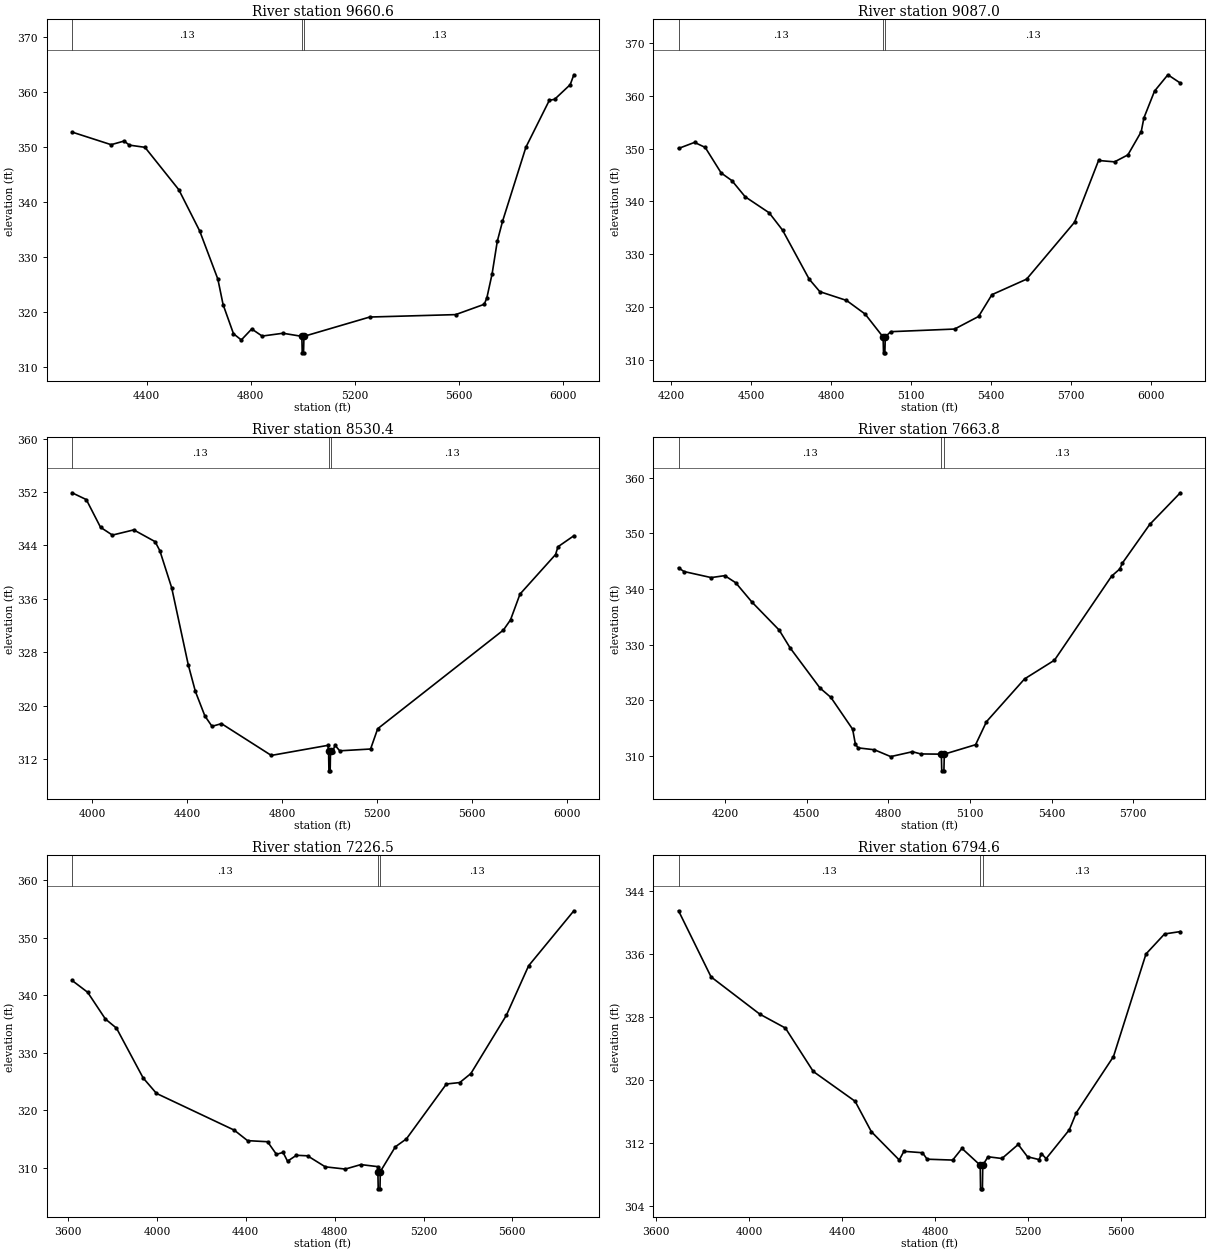
Type RM Length L Ch R = 1 ,9660.6,573.6,573.6,573.6
XS GIS Cut Line= 3
      2172345.92       790211.53      2172230.71       789325.82
      2172000.28       788317.70
BEGIN DESCRIPTION:
Cedar Fork (B10, S15) 22.0
END DESCRIPTION:
#Sta/Elev= 30
  4113.5   352.8  4263.5  350.51  4313.5  351.17  4333.5  350.43  4393.5  350.03
  4523.5  342.32  4603.5  334.84  4673.5  326.06  4693.5  321.44  4733.5  316.13
  4763.5     315  4803.5     317  4843.5  315.71  4923.5  316.22    4996  315.66
  4997.5  312.66  5002.6  312.66  5004.1  315.66  5256.7  319.17  5586.7  319.61
  5696.7  321.49  5706.7  322.67  5726.7     327  5746.7  332.94  5766.7  336.55
  5856.7  350.06  5946.7  358.59  5966.7  358.75  6026.7  361.42  6040.8  363.22
#Mann= 3 , 1 , 0
 4113.50    0.13       0    4996   0.042       0  5004.1    0.13       0
Bank Sta=4996.00,5004.10
Exp/Cntr=0.3,0.1

Type RM Length L Ch R = 1 ,9087.0,556.6,556.6,556.6
XS GIS Cut Line= 3
      2172958.00       789844.29      2172741.97       789109.80
      2172043.48       788238.49
BEGIN DESCRIPTION:
Cedar Fork (B10, S15) 21.0
END DESCRIPTION:
#Sta/Elev= 30
  4228.5  350.05  4288.5   351.2  4328.5  350.25  4388.5   345.4  4428.5  343.96
  4478.5  340.89  4568.5  337.85  4618.5  334.58  4718.5  325.28  4758.5   322.9
  4858.5  321.24  4928.5  318.65  4995.9   314.3  4997.4   311.3  5002.5   311.3
    5004   314.3  5024.1  315.31  5264.1  315.81  5354.1   318.2  5404.1  322.33
  5534.1  325.27  5714.1  336.07  5804.1  347.77  5864.1  347.51  5914.1  348.83
  5964.1  353.22  5974.1  355.83  6014.1  360.93  6064.1  364.02  6110.8  362.45
#Mann= 3 , 1 , 0
 4228.50    0.13       0  4995.9   0.042       0    5004    0.13       0
Bank Sta=4995.90,5004.00
Exp/Cntr=0.3,0.1

Type RM Length L Ch R = 1 ,8530.4,866.6,866.6,866.6
XS GIS Cut Line= 3
      2173001.42       789862.88      2173265.89       788951.92
      2172725.19       787917.54
BEGIN DESCRIPTION:
Cedar Fork (B10, S15) 20.0
END DESCRIPTION:
#Sta/Elev= 30
  3914.4  351.88  3974.4  350.86  4034.4  346.71  4084.4  345.54  4174.4  346.32
  4264.4  344.56  4284.4  343.21  4334.4  337.65  4404.4  326.09  4434.4  322.11
  4474.4  318.44  4504.4  316.89  4544.4  317.29  4754.4  312.53    4993  314.04
  4995.9  313.22  4997.4  310.22  5002.6  310.22  5004.1  313.22    5013   313.1
    5023  314.05    5043  313.22    5173  313.49    5203  316.53    5733  331.31
    5763  332.84    5803   336.7    5953  342.63    5963  343.79  6030.1  345.44
#Mann= 3 , 1 , 0
 3914.40    0.13       0  4995.9   0.042       0  5004.1    0.13       0
Bank Sta=4995.90,5004.10
Exp/Cntr=0.3,0.1

Type RM Length L Ch R = 1 ,7663.8,437.3,437.3,437.3
XS GIS Cut Line= 3
      2173600.89       790056.82      2173906.50       789134.11
      2174065.18       788276.05
BEGIN DESCRIPTION:
Cedar Fork (B10, S15) 19.0
END DESCRIPTION:
#Sta/Elev= 30
  4028.4  343.82  4048.4  343.15  4148.4  342.06  4198.4  342.41  4238.4  341.14
  4298.4  337.65  4398.4  332.62  4438.4  329.43  4548.4   322.2  4588.4  320.52
  4668.4  314.79  4678.4  312.13  4688.4  311.44  4748.4   311.1  4808.4  309.87
  4888.4  310.75  4918.4  310.35  4994.5  310.31    4996  307.31  5003.9  307.31
  5005.4  310.31  5120.4  312.01  5160.4  316.15  5300.4  323.84  5410.4  327.21
  5620.4  342.32  5650.4  343.61  5660.4  344.69  5760.4  351.61    5873  357.31
#Mann= 3 , 1 , 0
 4028.40    0.13       0  4994.5   0.042       0  5005.4    0.13       0
Bank Sta=4994.50,5005.40
Exp/Cntr=0.3,0.1

Type RM Length L Ch R = 1 ,7226.5,431.9,431.9,431.9
XS GIS Cut Line= 3
      2174382.55       790556.38      2174312.02       789192.88
      2174165.09       788311.31
BEGIN DESCRIPTION:
Cedar Fork (B10, S15) 18.0
END DESCRIPTION:
#Sta/Elev= 30
  3617.8  342.57  3687.8  340.52  3767.8  335.86  3817.8  334.27  3937.8   325.6
  3997.8  322.91  4347.8  316.52  4407.8  314.69  4497.8   314.5  4537.8  312.31
  4567.8  312.64  4587.8  311.11  4627.8  312.14  4677.8  312.05  4757.8  310.13
  4847.8  309.74  4917.8  310.52  4993.1  310.17  4994.6   309.3  4996.1   306.3
    5004   306.3  5005.5   309.3  5073.1  313.61  5123.1     315  5303.1  324.55
  5363.1   324.8  5413.1  326.36  5573.1  336.51  5673.1  345.12  5876.9   354.7
#Mann= 3 , 1 , 0
 3617.80    0.13       0  4994.6   0.042       0  5005.5    0.13       0
Bank Sta=4994.60,5005.50
Exp/Cntr=0.3,0.1

Type RM Length L Ch R = 1 ,6794.6,785.3,785.3,785.3
XS GIS Cut Line= 3
      2174505.97       790497.61      2174729.30       789204.64
      2174617.63       788364.20
BEGIN DESCRIPTION:
Cedar Fork (B10, S15) 17.0
END DESCRIPTION:
#Sta/Elev= 30
    3696  341.46    3836  333.07    4046  328.34    4156  326.58    4276  321.07
    4456  317.29    4526  313.43    4646  309.84    4666  310.94    4746  310.76
    4766  309.94    4876  309.83    4916  311.31  4994.5  309.18    4996  306.18
    5004  306.18  5005.5  309.18  5028.1  310.25  5088.1  310.03  5158.1  311.81
  5198.1  310.25  5248.1  309.89  5258.1  310.66  5278.1  310.01  5378.1  313.67
  5408.1  315.83  5568.1  322.96  5708.1  335.98  5788.1  338.52  5855.9  338.82
#Mann= 3 , 1 , 0
 3696.00    0.13       0  4994.5   0.042       0  5005.5    0.13       0
Bank Sta=4994.50,5005.50
Exp/Cntr=0.3,0.1

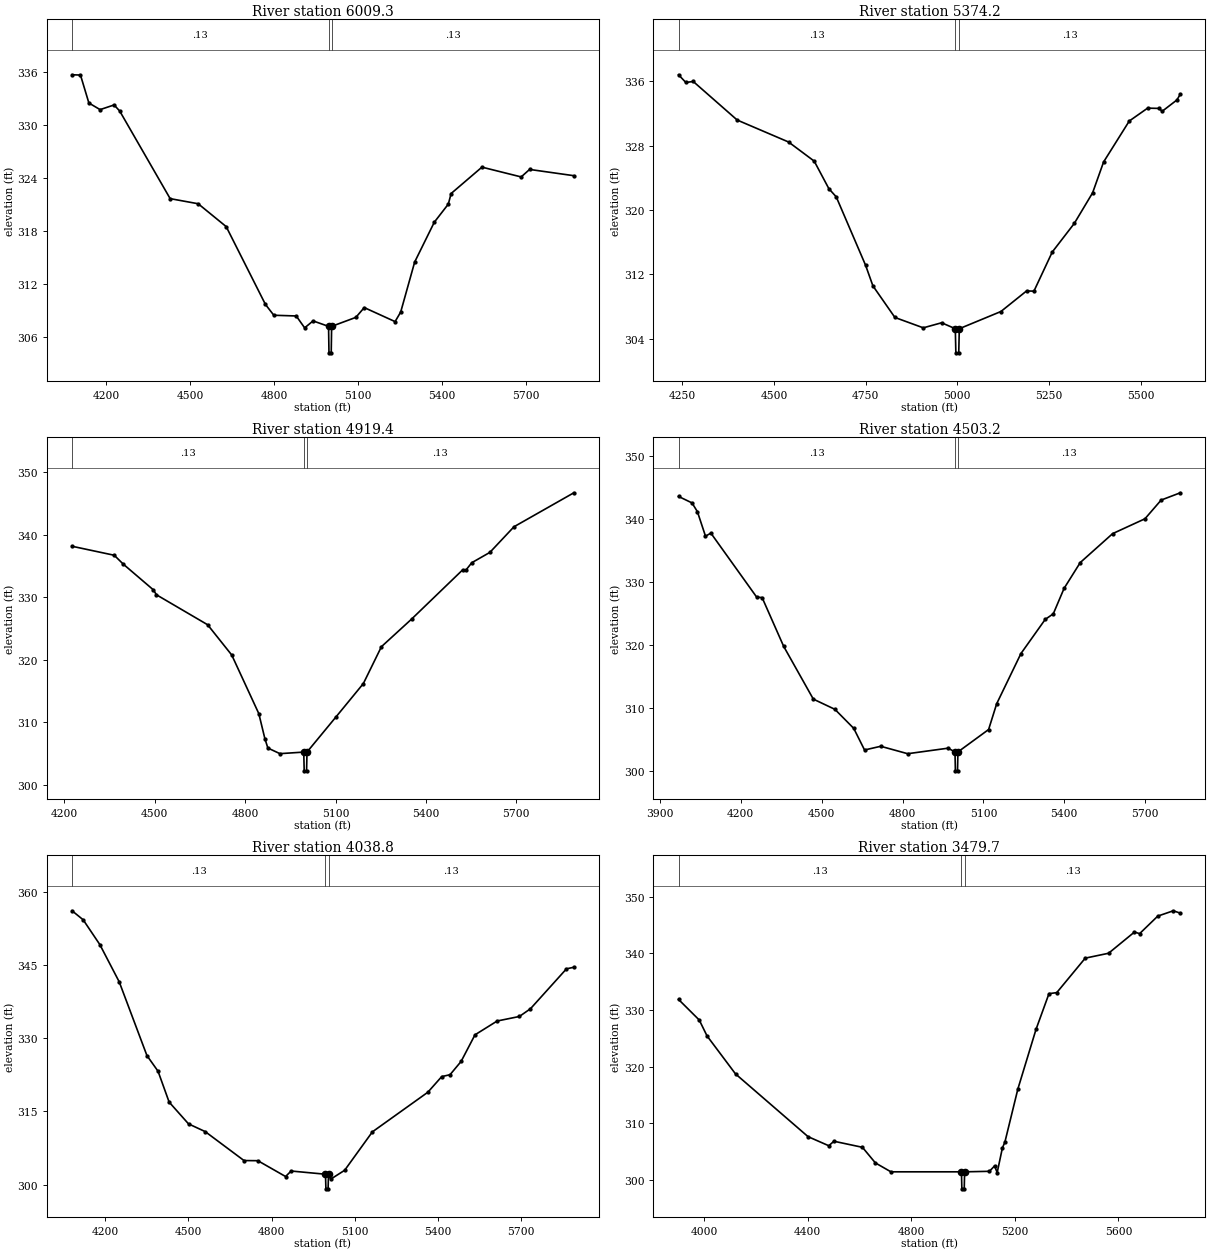
Type RM Length L Ch R = 1 ,6009.3,635.1,635.1,635.1
XS GIS Cut Line= 3
      2175258.24       790256.64      2175452.19       789375.07
      2175246.49       788511.13
BEGIN DESCRIPTION:
Cedar Fork (B10, S15) 16.0
END DESCRIPTION:
#Sta/Elev= 30
  4079.2  335.68  4109.2  335.65  4139.2  332.48  4179.2  331.73  4229.2  332.26
  4249.2  331.57  4429.2  321.64  4529.2  321.06  4629.2  318.47  4769.2  309.65
  4799.2  308.42  4879.2  308.34  4909.2  306.99  4939.2  307.78  4994.5  307.16
    4996  304.16    5004  304.16  5005.5  307.16  5091.9  308.18  5121.9  309.29
  5231.9   307.7  5251.9  308.78  5301.9  314.46  5371.9  318.97  5421.9  321.02
  5431.9  322.22  5541.9  325.21  5681.9   324.1  5711.9  324.95  5869.9  324.24
#Mann= 3 , 1 , 0
 4079.20    0.13       0  4994.5   0.042       0  5005.5    0.13       0
Bank Sta=4994.50,5005.50
Exp/Cntr=0.3,0.1

Type RM Length L Ch R = 1 ,5374.2,454.8,454.8,454.8
XS GIS Cut Line= 4
      2176098.67       790391.82      2175957.62       789739.46
      2175963.50       789527.88      2176245.60       789128.23
BEGIN DESCRIPTION:
Cedar Fork (B10, S15) 14.0
END DESCRIPTION:
#Sta/Elev= 30
  4239.8  336.81  4259.8  335.85  4279.8  335.98  4399.8  331.18  4539.8  328.45
  4609.8  326.07  4649.8  322.64  4669.8  321.63  4749.8  313.13  4769.8  310.56
  4829.8  306.63  4907.2  305.34  4957.2  305.97  4994.5  305.23    4996  302.23
  5003.9  302.23  5005.4  305.23  5118.9  307.37  5188.9  309.93  5208.9   309.9
  5258.9  314.77  5318.9  318.32  5368.9  322.13  5398.9  325.97  5468.9  331.06
  5518.9  332.66  5548.9  332.63  5558.9  332.28  5598.9  333.68  5608.1  334.41
#Mann= 3 , 1 , 0
 4239.80    0.13       0  4994.5   0.042       0  5005.4    0.13       0
Bank Sta=4994.50,5005.40
Exp/Cntr=0.3,0.1

Type RM Length L Ch R = 1 ,4919.4,416.2,416.2,416.2
XS GIS Cut Line= 3
      2176204.46       790479.98      2176380.78       789692.44
      2176416.04       788834.38
BEGIN DESCRIPTION:
Cedar Fork (B10, S15) 13.0
END DESCRIPTION:
#Sta/Elev= 26
  4225.4  338.17  4365.4  336.73  4395.4  335.31  4495.4  331.19  4505.4  330.41
  4675.4  325.61  4755.4  320.77  4845.4  311.38  4865.4  307.39  4875.4  305.88
  4915.4  304.98  4994.5  305.23    4996  302.23  5003.9  302.23  5005.3  305.23
  5005.4  305.24  5102.4  310.91  5192.4   316.2  5252.4   322.1  5352.4  326.51
  5522.4  334.41  5532.4  334.33  5552.4  335.54  5612.4  337.19  5692.4  341.29
  5891.2  346.73
#Mann= 3 , 1 , 0
 4225.40    0.13       0  4994.5   0.042       0  5005.3    0.13       0
Bank Sta=4994.50,5005.30
Exp/Cntr=0.3,0.1

Type RM Length L Ch R = 1 ,4503.2,464.4,464.4,464.4
XS GIS Cut Line= 3
      2177121.30       790597.52      2176780.42       789657.18
      2176474.81       788852.01
BEGIN DESCRIPTION:
Cedar Fork (B10, S15) 12.0
END DESCRIPTION:
#Sta/Elev= 30
    3969  343.59    4019  342.56    4039  341.17    4069  337.28    4089  337.76
    4259  327.59    4279  327.53    4359  319.78    4469   311.4    4549  309.78
    4619  306.75    4659  303.32    4719  303.91    4819  302.73    4969  303.61
  4994.5  303.01    4996  300.01  5003.9  300.01  5005.4  303.01  5119.2  306.57
  5149.2  310.67  5239.2  318.64  5329.2  324.06  5359.2  324.95  5399.2  328.99
  5459.2  333.09  5579.2  337.68  5699.2  340.04  5759.2  343.01  5830.4  344.17
#Mann= 3 , 1 , 0
 3969.00    0.13       0  4994.5   0.042       0  5005.4    0.13       0
Bank Sta=4994.50,5005.40
Exp/Cntr=0.3,0.1

Type RM Length L Ch R = 1 ,4038.8,559.1,559.1,559.1
XS GIS Cut Line= 3
      2177327.00       790556.38      2177227.08       789739.46
      2177080.14       788763.85
BEGIN DESCRIPTION:
Cedar Fork (B10, S15) 11.0
END DESCRIPTION:
#Sta/Elev= 30
  4080.7  356.22  4120.7  354.37  4180.7  349.29  4250.7  341.63  4350.7  326.48
  4390.7  323.27  4430.7  316.93  4500.7  312.45  4560.7  310.87  4700.7  304.92
  4750.7  304.89  4850.7  301.64  4870.7  302.77  4994.6  302.11  4996.1  299.11
    5004  299.11  5005.5  302.11  5013.7  301.11  5063.7  302.92  5163.7  310.81
  5363.7  318.95  5413.7  322.16  5443.7  322.55  5483.7  325.28  5533.7  330.74
  5613.7  333.58  5693.7  334.51  5733.7  336.09  5863.7   344.3  5890.3  344.62
#Mann= 3 , 1 , 0
 4080.70    0.13       0  4994.6   0.042       0  5005.5    0.13       0
Bank Sta=4994.60,5005.50
Exp/Cntr=0.3,0.1

Type RM Length L Ch R = 1 ,3479.7,435.6,435.6,435.6
XS GIS Cut Line= 3
      2178061.64       790362.43      2177591.47       789345.69
      2177115.42       788681.57
BEGIN DESCRIPTION:
Cedar Fork (B10, S15) 10.0
END DESCRIPTION:
#Sta/Elev= 30
  3901.6  331.86  3981.6  328.23  4011.6  325.43  4121.6  318.73  4401.6  307.67
  4481.6  306.07  4501.6  306.86  4611.6  305.79  4661.6  303.04  4721.6  301.47
  4993.9  301.47  4995.4  298.47  5004.6  298.47  5006.1  301.47  5101.8  301.56
  5121.8  302.51  5131.8  301.33  5151.8  305.65  5161.8  306.75  5211.8  316.09
  5281.8  326.59  5331.8  332.88  5361.8  333.06  5471.8  339.14  5561.8     340
  5661.8  343.74  5681.8  343.46  5751.8  346.55  5811.8  347.49  5838.9  347.07
#Mann= 3 , 1 , 0
 3901.60    0.13       0  4993.9   0.042       0  5006.1    0.13       0
Bank Sta=4993.90,5006.10
Exp/Cntr=0.3,0.1