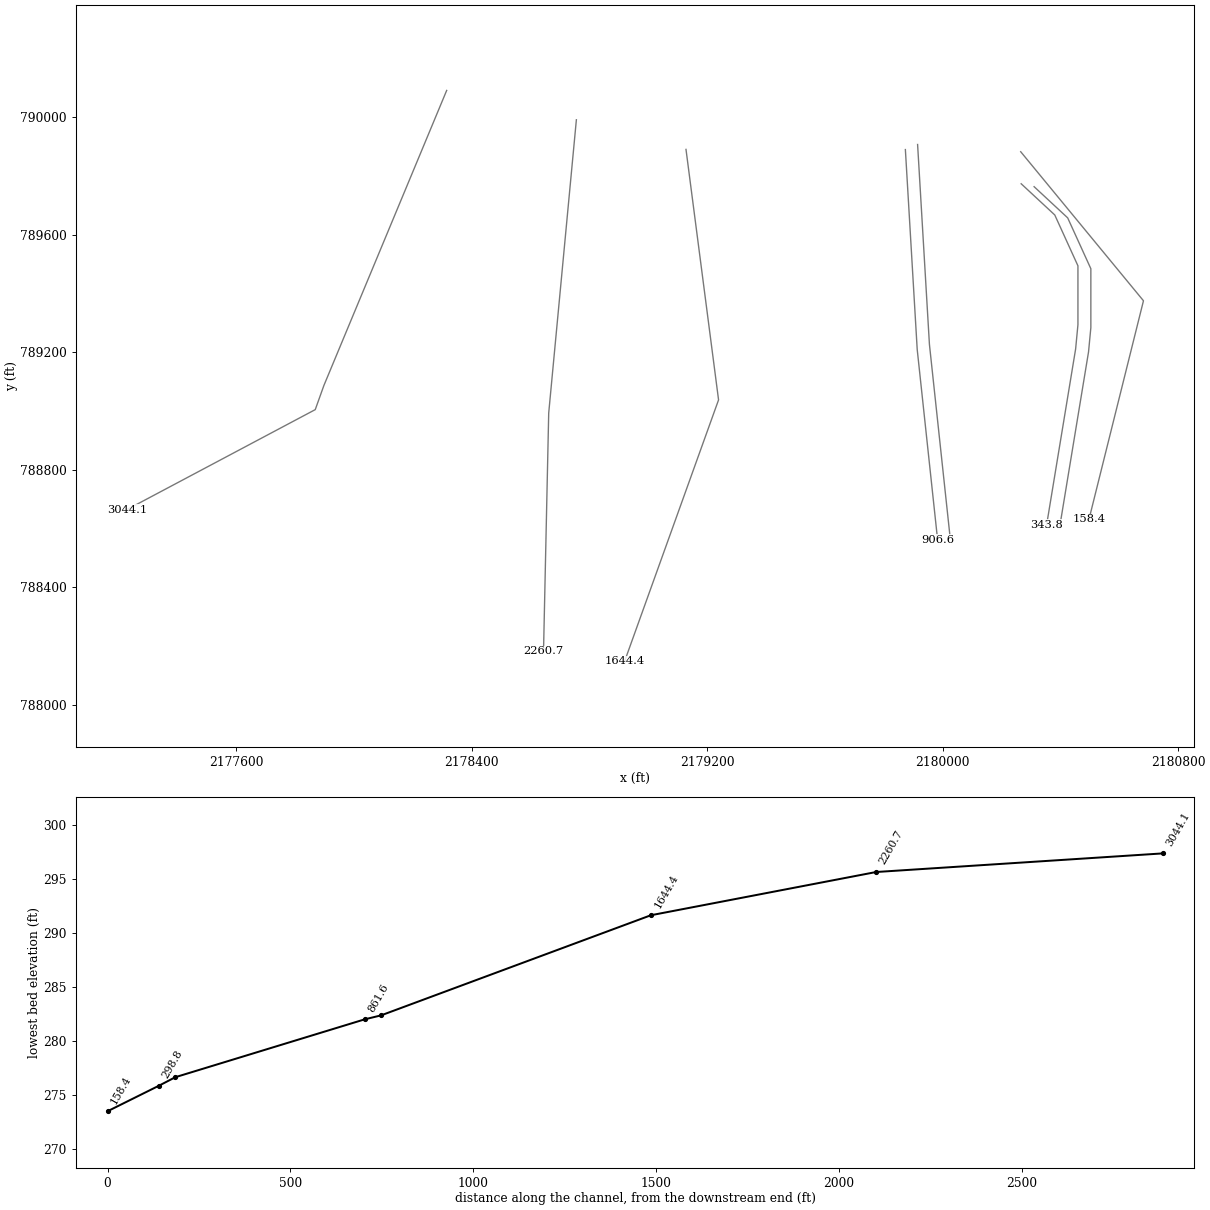
HEC-RAS study Cedar_Fork_fut.prj: Cedar Fork (B10, S15)

--- Cedar_Fork_fut.g01 (geometry) --- (continued)

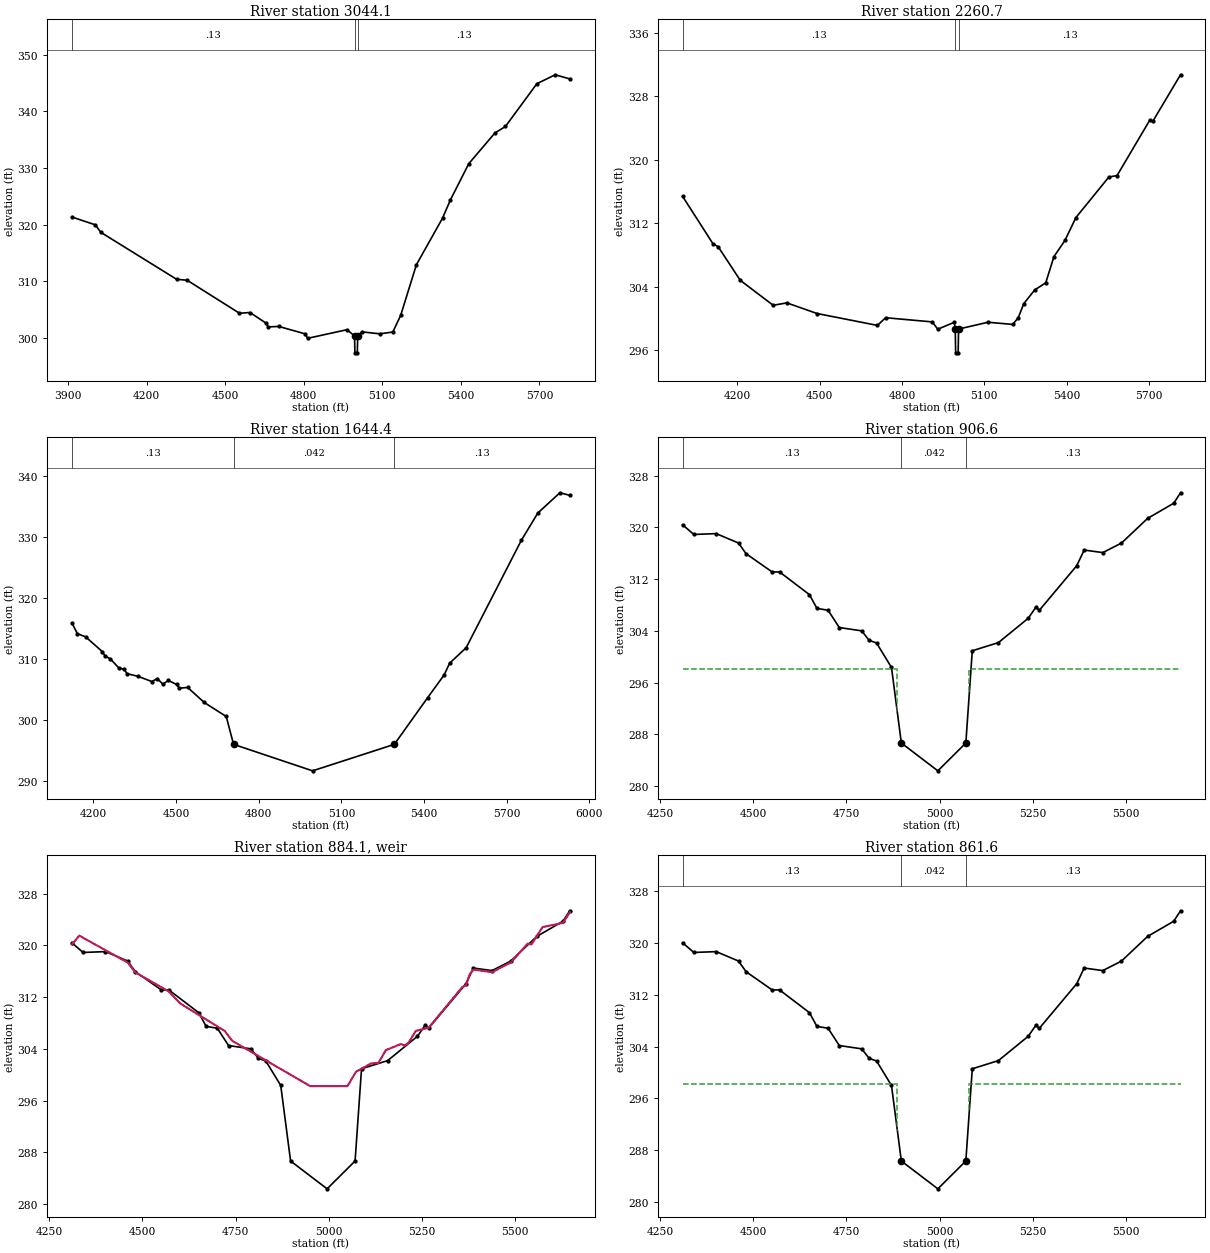
Type RM Length L Ch R = 1 ,3044.1,783.4,783.4,783.4
XS GIS Cut Line= 4
      2178314.36       790092.08      2177897.08       789087.09
      2177867.69       789004.81      2177227.08       788663.94
BEGIN DESCRIPTION:
Cedar Fork (B10, S15) 9.0
END DESCRIPTION:
#Sta/Elev= 30
  3914.6  321.34  4004.6  319.95  4024.6  318.65  4314.6  310.34  4354.6  310.18
  4554.6  304.35  4594.6  304.48  4654.6  302.65  4664.6  301.94  4704.6  302.02
  4804.6  300.72  4814.6  299.92  4964.6  301.44  4993.9  300.36  4995.4  297.36
  5004.5  297.36    5006  300.36  5022.8  301.06  5090.1  300.72  5140.1  301.03
  5170.1  303.96  5230.1  312.91  5330.1  321.15  5360.1  324.37  5430.1  330.75
  5530.1  336.18  5570.1  337.32  5690.1  344.87  5760.1  346.45  5815.8  345.72
#Mann= 3 , 1 , 0
 3914.60    0.13       0  4993.9   0.042       0    5006    0.13       0
Bank Sta=4993.90,5006.00
Exp/Cntr=0.3,0.1

Type RM Length L Ch R = 1 ,2260.7,616.3,616.3,616.3
XS GIS Cut Line= 3
      2178755.14       789992.17      2178661.11       788993.06
      2178643.48       788182.01
BEGIN DESCRIPTION:
Cedar Fork (B10, S15) 8.0
END DESCRIPTION:
#Sta/Elev= 30
  4000.3  315.37  4110.3  309.43  4130.3     309  4210.3  304.79  4330.3  301.64
  4380.3  301.94  4490.3   300.6  4710.3   299.1  4740.3  300.07  4910.3  299.54
  4930.3  298.62  4990.3  299.49    4994  298.64  4995.5  295.64  5004.6  295.64
  5006.1  298.64  5113.8   299.5  5203.8  299.22  5223.8  300.08  5243.8  301.85
  5283.8  303.58  5323.8  304.47  5353.8  307.78  5393.8  309.82  5433.8   312.7
  5553.8  317.81  5583.8     318  5703.8  325.03  5713.8  324.83  5815.1  330.71
#Mann= 3 , 1 , 0
 4000.30    0.13       0    4994   0.042       0  5006.1    0.13       0
Bank Sta=4994.00,5006.10
Exp/Cntr=0.3,0.1

Type RM Length L Ch R = 1 ,1644.4,737.8,737.8,737.8
XS GIS Cut Line= 3
      2179127.69       789891.22      2179238.36       789037.96
      2178919.09       788147.60
BEGIN DESCRIPTION:
Cedar Fork (B10, S15) 6.0
END DESCRIPTION:
#Sta/Elev= 30
  4122.2  315.89  4142.2  314.13  4172.2   313.6  4232.2   311.2  4242.2  310.49
  4262.2  309.97  4292.2  308.52  4312.2  308.27  4322.2  307.57  4362.2  307.13
  4412.2  306.28  4432.2  306.76  4452.2  305.85  4472.2  306.45  4502.2   305.8
  4512.2  305.18  4542.2  305.31  4602.2  302.85  4682.2  300.55 4708.79  295.98
  4995.4  291.64 5292.02  295.98  5412.6  303.62  5472.6  307.35  5492.6  309.28
  5552.6  311.82  5752.6  329.41  5812.6   333.9  5892.6  337.22  5928.5   336.8
#Mann= 3 , 1 , 0
 4122.20    0.13       0 4708.79   0.042       0 5292.02    0.13       0
Bank Sta=4708.79,5292.02
Exp/Cntr=0.5,0.3

Type RM Length L Ch R = 1 ,906.6,45,45,45
XS GIS Cut Line= 3
      2179873.26       789890.66      2179913.45       789209.85
      2179982.86       788560.64
BEGIN DESCRIPTION:
Upstream Section of Bridge/Culvert/Weir
END DESCRIPTION:
#Sta/Elev= 30
  4311.1  320.39  4341.1   318.9  4401.1  319.03  4461.1  317.57  4481.1  315.93
  4551.1  313.11  4571.1  313.11  4651.1   309.6  4671.1  307.48  4701.1  307.19
  4731.1  304.52  4791.1  304.01  4811.1  302.55  4831.1  302.13  4871.1  298.35
 4897.48  286.68  4995.4  282.38  5070.4  286.68  5087.7  300.93  5157.7  302.19
  5237.7  305.95  5257.7  307.62  5267.7   307.2  5367.7  314.07  5387.7  316.49
  5437.7   316.1  5487.7  317.57  5557.7  321.38  5627.7  323.72    5646  325.34
#Mann= 3 , 1 , 0
 4311.10    0.13       0 4897.48   0.042       0  5070.4    0.13       0
#XS Ineff= 2 , 0
       0    4887  298.15    5080       0  298.15
Bank Sta=4897.48,5070.40
Exp/Cntr=0.5,0.3

Type RM Length L Ch R = 5 ,884.1,,,
BEGIN DESCRIPTION:
Dam_1-TOR
Structure ID: Dam_1
Approximate Survey Structure
END DESCRIPTION:
#Inline Weir SE= 30
  4311.1  320.14    4331   321.5  4461.1  317.33  4481.1  315.82  4571.1  312.87
  4601.1  311.04    4721  306.77    4741  305.25    4950  298.25    5050  298.25
  5073.1  300.48  5113.1  301.74  5133.1  301.85  5153.1  303.82  5193.1  304.75
  5203.1  304.52  5213.1  304.91  5233.1  306.77  5267.7  307.28  5357.7  313.54
  5367.7  313.83  5377.7  315.53  5387.7  316.25  5437.7  315.86  5487.7  317.33
  5533.1  320.27  5543.1  320.13  5573.1  322.82  5627.7  323.47    5646  325.09
IW Dist,WD,Coef,Skew,MaxSub,Min_El,Is_Ogee,SpillHt,DesHd
10.0,25.0,3.0,,0.95,, 0 ,,,1.0,1.0,

Type RM Length L Ch R = 1 ,861.6,517.8,517.8,517.8
XS GIS Cut Line= 3
      2179914.79       789907.96      2179954.98       789227.16
      2180024.40       788577.95
BEGIN DESCRIPTION:
Downstream Section of Bridge/Culvert/Weir
END DESCRIPTION:
#Sta/Elev= 30
  4311.1  320.02  4341.1  318.53  4401.1  318.66  4461.1   317.2  4481.1  315.56
  4551.1  312.74  4571.1  312.74  4651.1  309.23  4671.1  307.11  4701.1  306.82
  4731.1  304.15  4791.1  303.64  4811.1  302.18  4831.1  301.76  4871.1  297.98
 4897.48  286.31  4995.4  282.01  5070.4  286.31  5087.7  300.56  5157.7  301.82
  5237.7  305.58  5257.7  307.25  5267.7  306.83  5367.7   313.7  5387.7  316.12
  5437.7  315.73  5487.7   317.2  5557.7  321.01  5627.7  323.35    5646  324.97
#Mann= 3 , 1 , 0
 4311.10    0.13       0 4897.48   0.042       0  5070.4    0.13       0
#XS Ineff= 2 , 0
       0    4887  298.15    5080       0  298.15
Bank Sta=4897.48,5070.40
Exp/Cntr=0.5,0.3

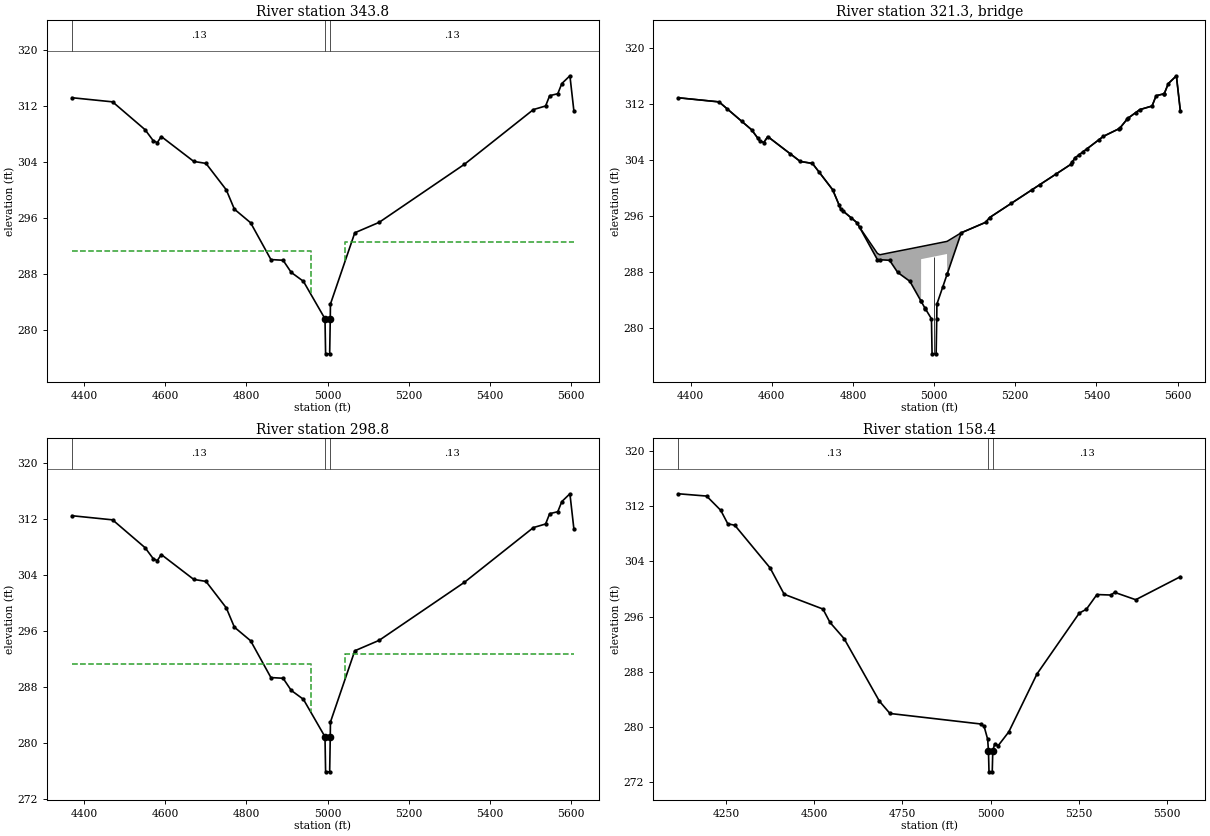
Type RM Length L Ch R = 1 ,343.8,45,45,45
XS GIS Cut Line= 6
      2180266.85       789774.16      2180380.99       789667.89
      2180459.71       789494.71      2180459.71       789293.98
      2180451.84       789211.32      2180353.44       788613.06
BEGIN DESCRIPTION:
Upstream Section of Bridge/Culvert/Weir
END DESCRIPTION:
#Sta/Elev= 30
  4370.2   313.2  4470.3  312.61  4550.3  308.64  4570.3  307.08  4580.3  306.79
  4590.3  307.66  4670.3  304.11  4700.3  303.83  4750.3  300.06  4770.3   297.3
  4810.3  295.36  4860.3  290.11  4890.3  290.01  4910.3  288.28  4940.3  287.01
  4993.5  281.66    4995  276.66    5005  276.66  5006.5  281.66  5006.9  283.76
  5066.9  293.93  5126.9  295.42  5336.9   303.7  5506.9  311.51  5536.9  312.02
  5546.9  313.49  5566.9  313.77  5576.9  315.22  5596.8  316.33  5606.5  311.36
#Mann= 3 , 1 , 0
 4370.20    0.13       0  4993.5   0.042       0  5006.5    0.13       0
#XS Ineff= 2 , 0
       0    4958   291.3    5043       0  292.65
Bank Sta=4993.50,5006.50
Exp/Cntr=0.5,0.3

Type RM Length L Ch R = 3 ,321.3,,,
BEGIN DESCRIPTION:
Pulley Town Road-TOR
Structure ID: Pulley Town Road
Approximate Survey Structure
END DESCRIPTION:
Bridge Culvert--1,0,-1,-1, 0
Deck Dist Width WeirC Skew NumUp NumDn MinLoCord MaxHiCord MaxSubmerge Is_Ogee
10,25,2.6,, 36, 36,,,0.95,0,1,1,,
  4370.2  4470.3  4550.3  4570.3  4580.3  4590.3  4670.3  4700.3  4750.3  4770.3
  4810.3  4816.4  4860.3  4866.4  4890.3  4910.3  4940.3 4967.91    4968 5031.89
    5032  5066.9  5126.9  5136.9  5336.9  5346.9  5416.9  5456.9  5476.9  5506.9
  5536.9  5546.9  5566.9  5576.9  5596.8  5606.5
  312.84  312.26  308.29  306.73  306.44  307.31  303.76  303.48  299.71  296.95
  295.01  294.37  290.64  290.44  290.72  290.95  291.29  291.61  291.61  292.35
  292.35  293.58  295.07  295.76  303.35  304.25  307.34  308.47   309.9  311.16
  311.67  313.14  313.42  314.87  315.98     311
  312.84  312.25  308.28  306.72  306.43   307.3  303.75  303.47   299.7  296.94
     295  294.36  289.75  289.73  289.65  287.92  286.65  283.81  289.81  290.55
  287.65  293.57  295.06  295.75  303.34  304.24  307.33  308.46  309.89  311.15
  311.66  313.13  313.41  314.86  315.97     311
  4370.2  4470.3  4550.3  4570.3  4580.3  4590.3  4670.3  4700.3  4750.3  4770.3
  4810.3  4816.4  4860.3  4866.4  4890.3  4910.3  4940.3 4967.91    4968 5031.89
    5032  5066.9  5126.9  5136.9  5336.9  5346.9  5416.9  5456.9  5476.9  5506.9
  5536.9  5546.9  5566.9  5576.9  5596.8  5606.5
  312.84  312.26  308.29  306.73  306.44  307.31  303.76  303.48  299.71  296.95
  295.01  294.37  290.64  290.44  290.72  290.95  291.29  291.61  291.61  292.35
  292.35  293.58  295.07  295.76  303.35  304.25  307.34  308.47   309.9  311.16
  311.67  313.14  313.42  314.87  315.98     311
  312.59     312  308.03  306.47  306.18  307.05   303.5  303.22  299.45  296.69
  294.75  294.11   289.5  289.48   289.4  287.67   286.4  283.56  289.56   290.3
   287.4  293.32  294.81   295.5  303.09  303.99  307.08  308.21  309.64   310.9
  311.41  312.88  313.16  314.61  315.72  310.75
Pier Skew, UpSta & Num, DnSta & Num=,5000.0, 2 ,5000.0, 2 , 0 , 0 , 0 ,,
       1       1
   275.3  291.19
       1       1
  275.05  290.94
Abutment Skew #Up #Dn=, 2 , 2
 4967.80 4978.50
  289.81  282.73
 4967.80 4978.50
  289.56  282.48
Abutment Skew #Up #Dn=, 2 , 2
 5021.50 5032.09
  285.87  290.55
 5021.50 5032.09
  285.62  290.30
BR Coef= 1 , 1 , 0 ,1.25, 0 ,,,0.8,0,2,0,
Wspro=,,,, 1 ,,,, 0 ,,,, 0 ,,,,-1 ,-1 ,-1 , 0 , 0 , 0 , 0 , 0
BC Design=,, 0 ,, 0 ,,,,,,
BR U #Sta/Elev= 65
  4370.2  312.84  4470.3  312.25  4490.2  311.26  4526.2  309.48  4550.3  308.28
  4566.2  307.04  4570.3  306.72  4580.3  306.43  4590.3   307.3  4646.2  304.82
  4670.3  303.75  4700.3  303.47  4716.4  302.26  4750.3   299.7  4766.4  297.48
  4770.3  296.94  4776.4  296.64  4796.4  295.67  4810.3     295  4816.4  294.36
  4860.3  289.75  4866.4  289.73  4890.3  289.65  4910.3  287.92  4940.3  286.65
 4967.91  283.81    4968   283.8  4976.9  282.88  4978.5  282.73  4993.5   281.3
    4995   276.3    5005   276.3  5006.5   281.3  5006.9   283.4  5021.5  285.87
 5031.89  287.64    5032  287.65  5066.9  293.57  5126.9  295.06  5136.9  295.75
  5190.1  297.77  5240.1  299.67  5260.1  300.43  5300.1  301.94  5336.9  303.34
  5340.1  303.63  5346.9  304.24  5356.1  304.65  5366.1  305.09  5376.1  305.53
  5406.1  306.85  5416.9  307.33  5456.1  308.44  5456.9  308.46  5476.1  309.83
  5476.9  309.89  5496.1   310.7  5506.9  311.15  5536.9  311.66  5546.9  313.13
  5566.1   313.4  5566.9  313.41  5576.9  314.86  5596.8  315.97  5606.5     311
BR U #Mann= 3
 4370.20    0.13  4993.5   0.042  5006.5    0.13
BR U Banks=4993.50,5006.50
BR D #Sta/Elev= 65
  4370.2  312.59  4470.3     312  4490.2  311.01  4526.2  309.23  4550.3  308.03
  4566.2  306.79  4570.3  306.47  4580.3  306.18  4590.3  307.05  4646.2  304.57
  4670.3   303.5  4700.3  303.22  4716.4  302.01  4750.3  299.45  4766.4  297.23
  4770.3  296.69  4776.4  296.39  4796.4  295.42  4810.3  294.75  4816.4  294.11
  4860.3   289.5  4866.4  289.48  4890.3   289.4  4910.3  287.67  4940.3   286.4
 4967.91  283.56    4968  283.55  4976.9  282.63  4978.5  282.48  4993.5  281.05
    4995  276.05    5005  276.05  5006.5  281.05  5006.9  283.15  5021.5  285.62
 5031.89  287.39    5032   287.4  5066.9  293.32  5126.9  294.81  5136.9   295.5
  5190.1  297.52  5240.1  299.42  5260.1  300.18  5300.1  301.69  5336.9  303.09
  5340.1  303.38  5346.9  303.99  5356.1   304.4  5366.1  304.84  5376.1  305.28
  5406.1   306.6  5416.9  307.08  5456.1  308.19  5456.9  308.21  5476.1  309.58
  5476.9  309.64  5496.1  310.45  5506.9   310.9  5536.9  311.41  5546.9  312.88
  5566.1  313.15  5566.9  313.16  5576.9  314.61  5596.8  315.72  5606.5  310.75
BR D #Mann= 3
 4370.20    0.13  4993.5   0.042  5006.5    0.13
BR D Banks=4993.50,5006.50

Type RM Length L Ch R = 1 ,298.8,140.4,140.4,140.4
XS GIS Cut Line= 6
      2180310.74       789764.25      2180424.88       789657.98
      2180503.60       789484.80      2180503.60       789284.07
      2180495.73       789201.41      2180397.33       788603.15
BEGIN DESCRIPTION:
Downstream Section of Bridge/Culvert/Weir
END DESCRIPTION:
#Sta/Elev= 30
  4370.2  312.41  4470.3  311.82  4550.3  307.85  4570.3  306.29  4580.3     306
  4590.3  306.87  4670.3  303.32  4700.3  303.04  4750.3  299.27  4770.3  296.51
  4810.3  294.57  4860.3  289.32  4890.3  289.22  4910.3  287.49  4940.3  286.22
  4993.5  280.87    4995  275.87    5005  275.87  5006.5  280.87  5006.9  282.97
  5066.9  293.14  5126.9  294.63  5336.9  302.91  5506.9  310.72  5536.9  311.23
  5546.9   312.7  5566.9  312.98  5576.9  314.43  5596.8  315.54  5606.5  310.57
#Mann= 3 , 1 , 0
 4370.20    0.13       0  4993.5   0.042       0  5006.5    0.13       0
#XS Ineff= 2 , 0
       0    4958   291.3    5043       0  292.65
Bank Sta=4993.50,5006.50
Exp/Cntr=0.5,0.3

Type RM Length L Ch R = 1 ,158.4,0,0,0
XS GIS Cut Line= 3
      2180265.18       789883.35      2180682.39       789375.61
      2180497.40       788631.72
BEGIN DESCRIPTION:
Cedar Fork (B10, S15) 1.0
END DESCRIPTION:
#Sta/Elev= 30
  4114.4  313.77  4194.4  313.44  4234.4  311.38  4254.4  309.43  4274.4  309.21
  4374.4  303.04  4414.4  299.22  4524.4  297.08  4544.4  295.14  4584.4   292.8
  4684.4  283.75  4714.4  281.96  4971.6  280.44  4981.6  280.08  4991.6  278.23
  4993.9  276.51  4995.4  273.51  5004.6  273.51  5006.1  276.51  5011.6  277.57
  5021.6  277.31  5051.6   279.3  5131.6  287.69  5251.6   296.5  5271.6  297.05
  5301.6  299.18  5341.6  299.11  5351.6   299.5  5411.6  298.43  5538.1  301.76
#Mann= 3 , 1 , 0
 4114.40    0.13       0  4993.9   0.042       0  5006.1    0.13       0
Bank Sta=4993.90,5006.10
Exp/Cntr=0.3,0.1

Chan Stop Cuts=-1