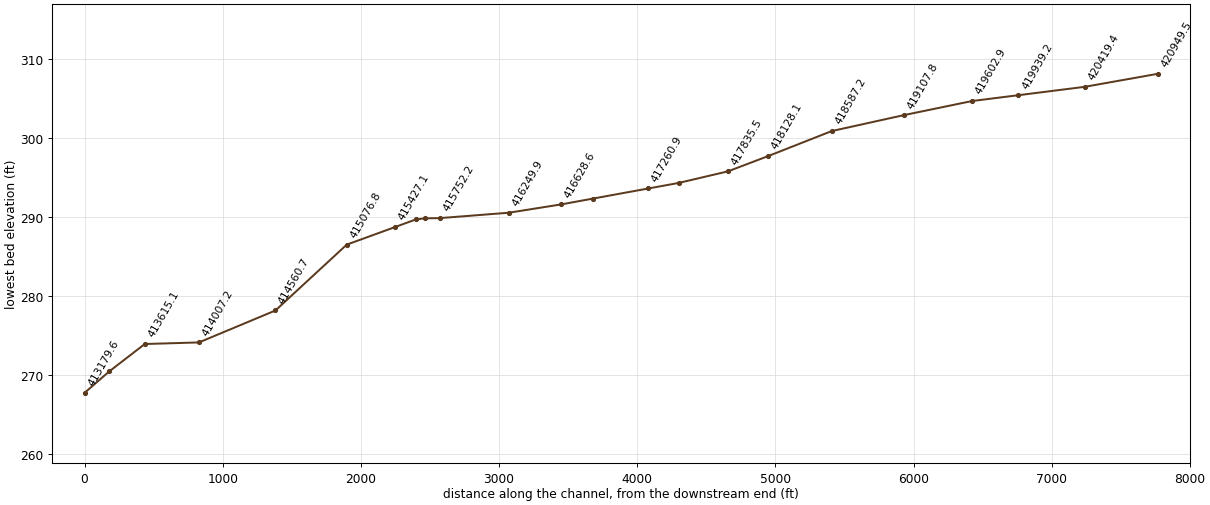
--- Little_River_FINAL.prj (project) ---

Proj Title=Little River Detail Study
Current Plan=p02
Default Exp/Contr=.3,.1
English Units
Geom File=g01
Flow File=f01
Flow File=f02
Plan File=p01
Plan File=p02
Y Axis Title=Elevation
X Axis Title(PF)=Main Channel Distance
X Axis Title(XS)=Station
BEGIN DESCRIPTION:
Wake County - NCFPM
END DESCRIPTION:
DSS Export Rating Curves= 0
DSS Export Rating Curve Sorted= 0
DSS Export Volume Flow Curves= 0
DXF OffsetX= 0
DXF OffsetY= 0
DXF ScaleX= 1
DXF ScaleY= 10

--- Little_River_FINAL.p02 (plan) ---

Plan Title=Floodway
Version=Version 3.0.1  Mar 2001
Short Identifier=Floodway
Geom File=g01
Flow File=f02
Subcritical Flow
K Sum by GR= 0
Std Step Tol= 0.01
Critical Tol= 0.01
Num of Std Step Trials= 20
Max Error Tol= 0.3
Flow Tol Ratio= 0.001
Split Flow NTrial= 30
Split Flow Tol= 0.02
Split Flow Ratio= 0.02
Log Output Level= 0
Friction Slope Method= 1
Unsteady Friction Slope Method= 2
Parabolic Critical Depth
Global Vel Dist= 0 , 0 , 0
Global Log Level= 0
CheckData=True
Encroach Param=-1 ,5,5, 2
Encroach River=Little River
Encroach Reach=Reach - 1
Encroach Node=420949.5
       1    4950    5075
Encroach Node=420419.4
       1    4870    5050
Encroach Node=419939.2
       1    4890    5070
Encroach Node=419602.9
       1    4960    5100
Encroach Node=419107.8
       1    4960    5110
Encroach Node=418587.2
       1    4900    5035
Encroach Node=418128.1
       1    4900    5040
Encroach Node=417835.5
       1    4925    5065
Encroach Node=417480.2
       1    4955    5090
Encroach Node=417260.9
       1    4930    5100
Encroach Node=416859.9
       1    4850    5100
Encroach Node=416628.6
       1    4790    5110
Encroach Node=416249.9
       1    4860    5100
Encroach Node=415752.2
       1    4900    5060
Encroach Node=415644.2
       1    4945    5045
Encroach Node=415611.2
       1    4945    5045
Encroach Node=415578.2
       1    4945    5045
Encroach Node=415427.1
       1    4930    5080
Encroach Node=415076.8
       1    4940    5070
Encroach Node=414560.7
       1    4945    5125
Encroach Node=414007.2
       1    4900    5100
Encroach Node=413615.1
       1    4870    5090
Encroach Node=413358.4
       1    4735    5030
Encroach Node=413179.6
       1    4870    5120
Encroach Node=413164.6
       1    4870    5120
Encroach Node=413149.6
       1    4825    5041
Encroach Node=412866.1
       1    4885    5160
Encroach Node=412648.9
       1  4949.7  5057.6
Encroach Node=412625.9
       1  4949.7  5057.6
Encroach Node=412602.9
       1  4949.7  5057.6
Encroach Node=412531.2
       1    4920    5030
Encroach Node=412310.4
       1    4930    5075
Encroach Node=412021.4
       1    4920    5050
Encroach Node=411600.7
       1    4920    5050
Encroach Node=411298.2
       1    4870    5055
Encroach Node=410894.1
       1    4965    5135
Encroach Node=410613.4
       1    4945    5135
Encroach Node=410238.2
       1    4910    5200
Encroach Node=409673.7
       1    4780    5150
Encroach Node=409414.8
       1    4690    5110
Encroach Node=408865.3
       1    4640    5190
Encroach Node=408572.7
       1    4725    5225
Encroach Node=408238.6
       1    4760    5250
Encroach Node=407703.8
       1    4810    5190
Encroach Node=407195.8
       1    4915    5085
Encroach Node=406640.6
       1    4920    5190
Encroach Node=405975.3
       1    4930    5260
Encroach Node=405387.0
       1    4920    5330
Encroach Node=403813.0
       1    4870    5160
Encroach Node=402850.1
       1    4810    5070
Encroach Node=402173.5
       1    4900    5160
Encroach Node=401591.0
       1    4910    5300
Encroach Node=400905.2
       1    4710    5370
Encroach Node=400237.3
       1    4750    5435
Encroach Node=399407.5
       1    4760    5225
Encroach Node=398858.3
       1    4735    5085
Encroach Node=397971.1
       1    4860    5065
Encroach Node=397670.2
       1    4926    5090
Encroach Node=397643.7
       1    4926    5090
Encroach Node=397617.2
       1    4926    5090
Encroach Node=397495.1
       1    4900    5150
Encroach Node=397132.1
       1    4820    5160
Encroach Node=396548.6
       1    4725    5140
Encroach Node=395598.3
       1    4725    5140
Encroach Node=394729.3
       1    4660    5045
Encroach Node=393983.7
       1    4770    5110
Encroach Node=393237.3
       1    4750    5250
Encroach Node=392678.1
       1    4810    5170
Encroach Node=392207.7
       1    4840    5220
Encroach Node=391795.8
       1    4750    5250
Encroach Node=390965.5
       1    4600    5550
Encroach Node=390210.1
       1    4750    5650
Encroach Node=389547.4
       1    4640    5910
Encroach Node=389106.4
       1    4500    5925
Encroach Node=388636.1
       1    4320    5870
Encroach Node=388242.6
       1    4380    5870
Encroach Node=387772.3
       1    4450    5680
Encroach Node=387339.5
       1    4550    5490
Encroach Node=387108.0
       1    4500    5250
Encroach Node=387087.5
       1    4500    5250
Encroach Node=387067.0
       1    4500    5250
Encroach Node=386844.9
       1    4760    5280
Encroach Node=386349.9
       1    4750    5290
Encroach Node=385817.2
       1    4750    5450
Encroach Node=385373.7
       1    4800    5550
Encroach Node=384677.9
       1    4785    5400
Encroach Node=383954.3
       1    4780    5330
Encroach Node=383632.7
       1    4760    5250
Encroach Node=383158.3
       1    4725    5145
Encroach Node=382620.1
       1    4575    5030
Encroach Node=382035.1
       1    4635    5085
Encroach Node=381278.6
       1    4700    5110
Encroach Node=380859.2
       1    4815    5215
Encroach Node=380552.1
       1    4765    5220
Encroach Node=379967.8
       1    4555    5235
Encroach Node=379614.7
       1    4780    5430
Encroach Node=379021.3
       1    4770    5270
Encroach Node=378674.7
       1    4710    5190
Encroach Node=378441.8
       1    4700    5160
Encroach Node=378416.3
       1    4700    5160
Encroach Node=378390.8
       1    4700    5160
Encroach Node=378225.5
       1    4730    5195
Encroach Node=377833.8
       1    4700    5200
Encroach Node=377156.5
       1    4820    5600
Encroach Node=376750.3
       1    4740    5550
Encroach Node=376220.1
       1    4630    5360
Encroach Node=375402.9
       1    4720    5180
Encroach Node=375172.8
       1    4907    5095
Encroach Node=375092.8
       1    4907    5095
Encroach Node=375012.8
       1    4907    5095
Encroach Node=374957.4
       1    4950    5200
Encroach Node=374177.6
       1    4770    5140
Encroach Node=374066.0
       1    4840    5070
Encroach Node=374043.0
       1    4840    5070
Encroach Node=374020.0
       1    4840    5070
Encroach Node=373894.4
       1    4825    5165
Encroach Node=373200.3
       1    4860    5170
Encroach Node=372586.0
       1    4880    5270
Encroach Node=372040.9
       1    4930    5290
Encroach Node=371755.3
       1    4780    5210
Encroach Node=371743.8
       1    4780    5210
Encroach Node=371732.3
       1    4886    5210
Encroach Node=371646.0
       1    4840    5220
Encroach Node=371560.3
       1    4810    5245
Encroach Node=371533.8
       1    4810    5245
Encroach Node=371507.3
       1    4810    5245
Encroach Node=371355.8
       1    4830    5300
Encroach Node=370910.5
       1    4950    5520
Encroach Node=370259.6
       1    4820    5285
Encroach Node=369753.1
       1    4640    5170
Encroach Node=369242.0
       1    4720    5400
Encroach Node=368640.3
       1    4950    5620
Encroach Node=367746.3
       1    4885    5120
Encroach Node=367214.3
       1    4840    5080
Encroach Node=366844.2
       1    4800    5120
Encroach Node=366524.1
       1    4810    5135
Encroach Node=365853.7
       1    4440    5430
Encroach Node=365040.9
       1    4440    5390
Encroach Node=364566.5
       1    4450    5280
Encroach Node=364135.0
       1    4650    5240
Encroach Node=363602.1
       1    4685    5190
Encroach Node=363194.6
       1    4765    5125
Encroach Node=362700.6
       1    4860    5240
Encroach Node=362215.0
       1    4750    5130
Encroach Node=361990.4
       1    4670    5085
Encroach Node=361554.1
       1    4910    5400
Encroach Node=360683.1
       1    4625    5270
Encroach Node=360402.8
       1    4750    5450
Encroach Node=359551.4
       1    4925    5525
Encroach Node=358802.6
       1    4900    5100
Encroach Node=358635.4
       1    4920    5080
Encroach Node=358608.9
       1    4920    5080
Encroach Node=358582.4
       1    4920    5080
Encroach Node=358461.3
       1    4880    5130
Encroach Node=358450.3
       1    4880    5130
Encroach Node=358439.3
       1    4880    5130
Encroach Node=358310.4
       1    4880    5145
Encroach Node=357854.4
       1    4875    5125
Encroach Node=357494.3
       1    4880    5100
Encroach Node=357317.2
       1    4830    5075
Encroach Node=356800.3
       1    4940    5220
Encroach Node=356217.7
       1    4800    5150
Encroach Node=355901.0
       1    4943    5065
Encroach Node=355885.0
       1    4943    5065
Encroach Node=355869.0
       1    4943    5065
Encroach Node=355701.4
       1    4640    5400
Encroach Node=355209.8
       1    4530    5420
Encroach Node=354442.9
       1    4720    5600
Encroach Node=353927.5
       1    4765    5320
Encroach Node=353442.9
       1    4755    5300
Encroach Node=352707.7
       1    4880    5180
Encroach Node=352179.5
       1    4915    5335
Encroach Node=351644.7
       1    4850    5510
Encroach Node=350434.0
       1    4650    5640
Encroach Node=349681.7
       1    4780    5720
Encroach Node=348904.3
       1    4810    5260
Encroach Node=348267.9
       1    4850    5060
Encroach Node=348136.7
       1    4859    5072
Encroach Node=348110.2
       1    4859    5072
Encroach Node=348083.7
       1    4859    5072
Encroach Node=347953.0
       1    4770    5100
Encroach Node=346975.1
       1    4850    5260
Encroach Node=346136.4
       1    4570    5200
Encroach Node=345141.0
       1    4930    5600
Encroach Node=344836.4
       1    4446    5520
Computation Interval=1HOUR
Output Interval=1HOUR
Run HTab= 0
Run UNet= 0
Run PostProcess= 0
UNET Theta= 1
UNET ZTol= 0.02
UNET ZSATol= 0.1
UNET MxIter= 20
UNET MaxInSteps= 20
UNET DtIC= 0
UNET DtMin= 0
UNET MaxCRTS= 20
UNET WFStab= 2
UNET SFStab= 1
UNET WFX= 1
UNET SFX= 1
UNET Convert EG Bridges=-1
UNET Use Existing IB Tables=-1
Instantaneous Interval=1HOUR
DSS File=dss
Write IC File= 0
IC Time=0
Write Velocity= 0
Write Detailed= 0

--- Little_River_FINAL.p01 (plan) ---

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Plan Title=Multiple
Short Identifier=MULTIPLE
Geom File=g01
Flow File=f01
Interactive Comp Mode
Encroach Param= -1, 0, 0, 0

--- Little_River_FINAL.f02 (steady flow) ---

Flow Title=Floodway
Program Version=3.10
Number of Profiles= 2
Profile Names=100-year,Floodway
River Rch & RM=Little River,Reach - 1       ,420949.5
    4620    4620
River Rch & RM=Little River,Reach - 1       ,420419.4
    7040    7040
River Rch & RM=Little River,Reach - 1       ,414560.7
    7940    7940
River Rch & RM=Little River,Reach - 1       ,407703.8
    8660    8660
River Rch & RM=Little River,Reach - 1       ,406640.6
    9080    9080
River Rch & RM=Little River,Reach - 1       ,400905.2
    9130    9130
River Rch & RM=Little River,Reach - 1       ,397132.1
    9300    9300
River Rch & RM=Little River,Reach - 1       ,391795.8
    9360    9360
River Rch & RM=Little River,Reach - 1       ,390210.1
    9490    9490
River Rch & RM=Little River,Reach - 1       ,385373.7
    9490    9490
River Rch & RM=Little River,Reach - 1       ,383954.3
    9750    9750
River Rch & RM=Little River,Reach - 1       ,383158.3
    9930    9930
River Rch & RM=Little River,Reach - 1       ,376220.1
   10000   10000
River Rch & RM=Little River,Reach - 1       ,374066
   10100   10100
River Rch & RM=Little River,Reach - 1       ,367214.3
   10200   10200
River Rch & RM=Little River,Reach - 1       ,363194.6
   10300   10300
River Rch & RM=Little River,Reach - 1       ,362215
   10400   10400
River Rch & RM=Little River,Reach - 1       ,355901
   10400   10400
River Rch & RM=Little River,Reach - 1       ,353442.9
   10400   10400
River Rch & RM=Little River,Reach - 1       ,350434
   10400   10400
River Rch & RM=Little River,Reach - 1       ,348267.9
   10400   10400
Boundary for River Rch & Prof#=Little River,Reach - 1       , 1
Up Type= 0
Dn Type= 1
Dn Known WS=216.14
Boundary for River Rch & Prof#=Little River,Reach - 1       , 2
Up Type= 0
Dn Type= 1
Dn Known WS=217.04
DSS Import GetInterval= 0
DSS Import GetPeak= 0
DSS Import FillOption= 0

--- Little_River_FINAL.f01 (steady flow) ---

Flow Title= Multiple
Program Version=3.10
Number of Profiles= 5
Profile Names=10-year,50-year,100-year,500-year,100yr future
River Rch & RM=Little River,Reach - 1       ,420949.5
    1790    3620    4620    7670    4820
River Rch & RM=Little River,Reach - 1       ,420419.4
    2680    5550    7040   11600    7730
River Rch & RM=Little River,Reach - 1       ,414560.7
    2940    6230    7940   13200    8730
River Rch & RM=Little River,Reach - 1       ,407703.8
    3200    6800    8660   14900    9760
River Rch & RM=Little River,Reach - 1       ,406640.6
    3350    7090    9080   15400   10300
River Rch & RM=Little River,Reach - 1       ,400905.2
    3350    7110    9130   15300   10300
River Rch & RM=Little River,Reach - 1       ,397132.1
    3400    7240    9300   15500   10500
River Rch & RM=Little River,Reach - 1       ,391795.8
    3420    7280    9360   15600   10500
River Rch & RM=Little River,Reach - 1       ,390210.1
    3450    7390    9490   15700   10700
River Rch & RM=Little River,Reach - 1       ,385373.7
    3450    7390    9490   15700   10700
River Rch & RM=Little River,Reach - 1       ,383954.3
    3550    7600    9750   16100   11000
River Rch & RM=Little River,Reach - 1       ,383158.3
    3600    7780    9930   16400   11200
River Rch & RM=Little River,Reach - 1       ,376220.1
    3610    7860   10000   16500   11300
River Rch & RM=Little River,Reach - 1       ,374066
    3660    7990   10100   16700   11400
River Rch & RM=Little River,Reach - 1       ,367214.3
    3680    8080   10200   16800   11500
River Rch & RM=Little River,Reach - 1       ,363194.6
    3680    8120   10300   16800   11500
River Rch & RM=Little River,Reach - 1       ,362215
    3700    8240   10400   17000   11600
River Rch & RM=Little River,Reach - 1       ,355901
    3700    8290   10400   17100   11700
River Rch & RM=Little River,Reach - 1       ,353442.9
    3700    8290   10400   17200   11700
River Rch & RM=Little River,Reach - 1       ,350434
    3690    8290   10400   17200   11700
River Rch & RM=Little River,Reach - 1       ,348267.9
    3690    8290   10400   17300   11700
Boundary for River Rch & Prof#=Little River,Reach - 1       , 1
Up Type= 0
Dn Type= 3
Dn Slope=0.00016
Boundary for River Rch & Prof#=Little River,Reach - 1       , 2
Up Type= 0
Dn Type= 3
Dn Slope=0.00016
Boundary for River Rch & Prof#=Little River,Reach - 1       , 3
Up Type= 0
Dn Type= 1
Dn Known WS=216.14
Boundary for River Rch & Prof#=Little River,Reach - 1       , 4
Up Type= 0
Dn Type= 3
Dn Slope=0.00016
Boundary for River Rch & Prof#=Little River,Reach - 1       , 5
Up Type= 0
Dn Type= 3
Dn Slope=0.00016
DSS Import GetInterval= 0
DSS Import GetPeak= 0
DSS Import FillOption= 0

--- Little_River_FINAL.g01 (geometry) ---

Geom Title=Geom 01 by CodeH2 for Windows

River Reach=Little River,Reach - 1
Reach XY= 2
              .5             .95              .5             .05

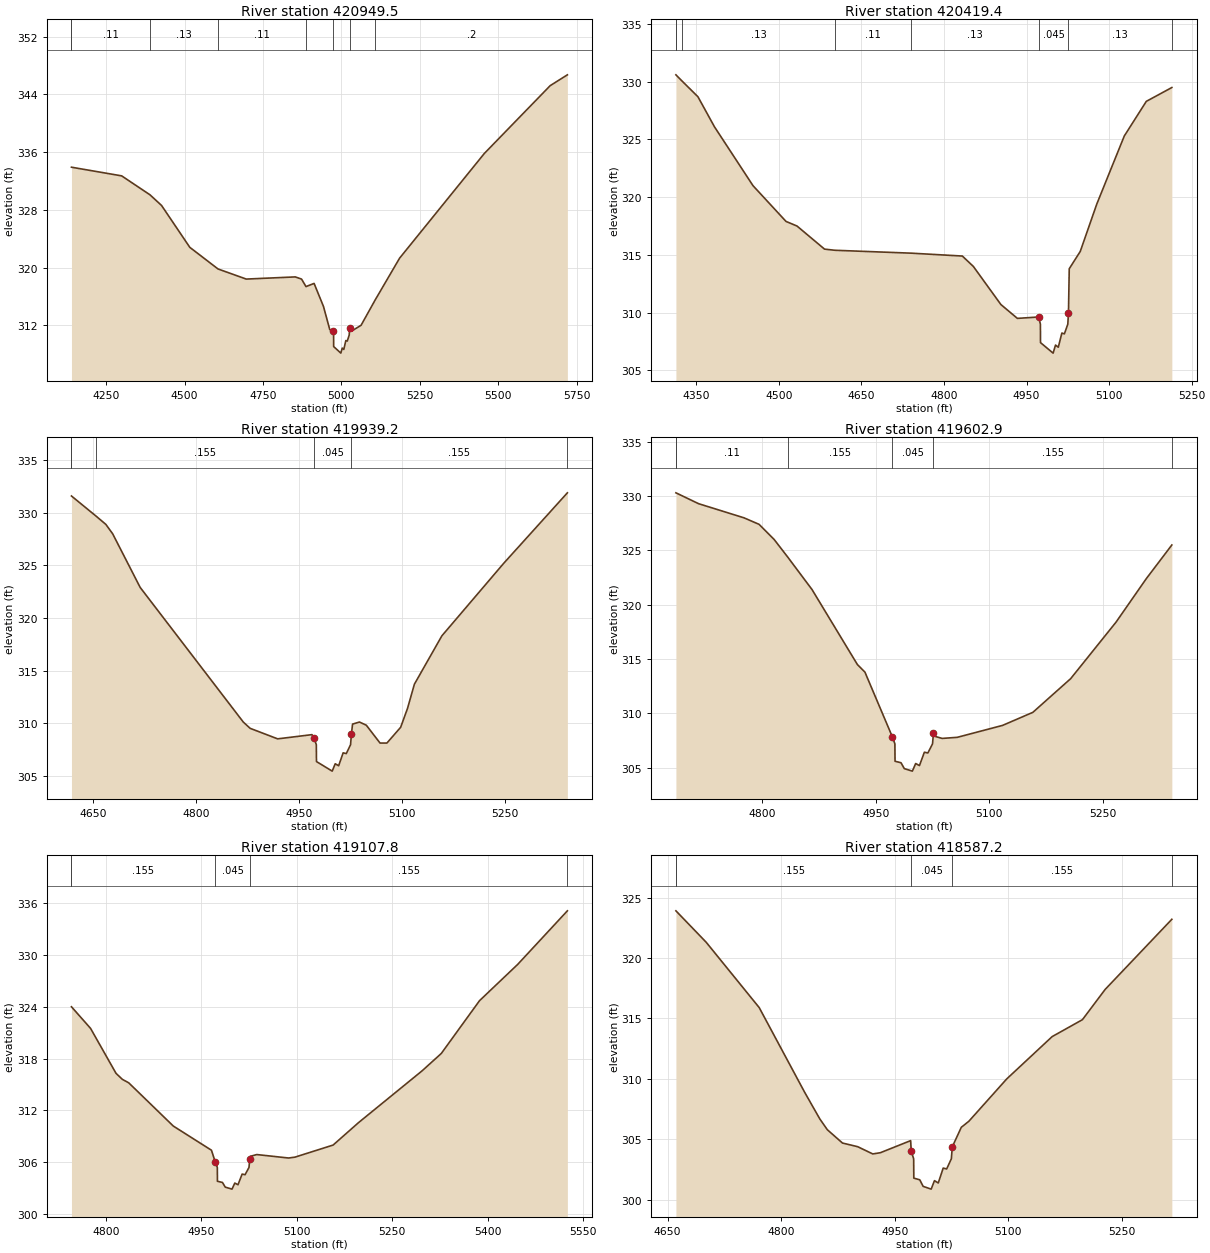
Type RM Length L Ch R = 1 ,420949.5,530.1,530.1,530.1
BEGIN DESCRIPTION:
Cross Section Little River 151.0 - LDS
END DESCRIPTION:
#Sta/Elev= 30
  4139.5   333.9  4299.5   332.7  4389.7  330.08  4426.7   328.6  4516.7   322.8
  4606.7   319.8  4696.7   318.4  4852.9   318.7  4872.9   318.4  4887.1  317.36
  4912.9   317.8  4942.9   314.6  4962.9   311.4  4971.9  311.27  4975.1  310.65
  4975.3  309.05  4998.2  308.14  5002.6  308.84  5007.6  308.65  5014.1  309.88
  5018.7  309.81  5024.9  310.65  5026.1  311.63  5032.7   311.2  5062.7     312
  5107.4  315.49  5185.5   321.3  5455.5   335.8  5665.5   345.2  5720.3   346.7
#Mann= 8 , 1 , 0
 4139.50     0.2       0  4139.5    0.11       0  4389.7    0.13       0
  4606.7    0.11       0  4887.1    0.13       0  4971.9   0.042       0
  5026.1   0.155       0  5107.4     0.2       0
Bank Sta=4971.90,5026.10
Exp/Cntr=0.3,0.1

Type RM Length L Ch R = 1 ,420419.4,480.2,480.2,480.2
BEGIN DESCRIPTION:
Cross Section Little River 110.0
END DESCRIPTION:
#Sta/Elev= 30
  4312.9   330.6  4324.5  330.04  4352.9   328.7  4382.9   326.1  4452.9     321
  4512.9   317.9  4532.9   317.5  4582.9   315.5  4601.8   315.4  4740.4  315.15
  4833.3   314.9  4853.3     314  4903.3   310.7  4933.3   309.5  4971.9  309.62
  4975.1     309  4975.3   307.4  4998.2  306.49  5002.6  307.19  5007.6     307
  5014.1  308.23  5018.7  308.16  5024.9     309  5026.1  309.98  5027.5   313.8
  5047.5   315.3  5077.5   319.4  5127.5   325.3  5167.5   328.3  5213.9   329.5
#Mann= 8 , 1 , 0
 4312.90     0.2       0  4312.9    0.11       0  4324.5    0.13       0
  4601.8    0.11       0  4740.4    0.13       0  4971.9   0.045       0
  5026.1    0.13       0  5213.9     0.2       0
Bank Sta=4971.90,5026.10
Exp/Cntr=0.3,0.1

Type RM Length L Ch R = 1 ,419939.2,336.3,336.3,336.3
BEGIN DESCRIPTION:
Cross Section Little River 109.0
END DESCRIPTION:
#Sta/Elev= 30
  4618.8   331.6  4654.5  329.69  4668.8   328.9  4678.8     328  4718.8   322.9
  4868.8   310.1  4878.8   309.5  4918.8   308.5  4968.8   308.9  4971.9  308.56
  4975.1  307.94  4975.3  306.34  4998.2  305.43  5002.6  306.13  5007.6  305.94
  5014.1  307.17  5018.7   307.1  5024.9  307.94  5026.1  308.92  5027.8   309.9
  5037.8   310.1  5047.8   309.8  5067.8   308.1  5077.8   308.1  5097.8   309.6
  5107.8   311.4  5117.8   313.7  5157.8   318.3  5247.8   325.2  5340.4   331.9
#Mann= 6 , 1 , 0
 4618.80     0.2       0  4618.8    0.11       0  4654.5   0.155       0
  4971.9   0.045       0  5026.1   0.155       0  5340.4     0.2       0
Bank Sta=4971.90,5026.10
Exp/Cntr=0.3,0.1

Type RM Length L Ch R = 1 ,419602.9,495.1,495.1,495.1
BEGIN DESCRIPTION:
Cross Section Little River 108.0
END DESCRIPTION:
#Sta/Elev= 30
  4685.5   330.3  4715.5   329.3  4775.5     328  4795.5   327.4  4815.5     326
  4833.9  324.34  4865.5   321.4  4925.5   314.5  4935.5   313.8  4971.9  307.82
  4975.1   307.2  4975.3   305.6  4983.2  305.46  4987.6  304.92  4998.2  304.69
  5002.6  305.39  5007.6   305.2  5014.1  306.43  5018.7  306.36  5024.9   307.2
  5026.1  308.18  5027.6   307.9  5037.6   307.7  5057.6   307.8  5117.6   308.9
  5157.6   310.1  5207.6   313.2  5267.6   318.4  5307.6   322.4  5341.4   325.5
#Mann= 6 , 1 , 0
 4685.50     0.2       0  4685.5    0.11       0  4833.9   0.155       0
  4971.9   0.045       0  5026.1   0.155       0  5341.4     0.2       0
Bank Sta=4971.90,5026.10
Exp/Cntr=0.3,0.1

Type RM Length L Ch R = 1 ,419107.8,520.6,520.6,520.6
BEGIN DESCRIPTION:
Cross Section Little River 107.0
END DESCRIPTION:
#Sta/Elev= 30
  4745.9     324  4775.9   321.5  4815.9   316.3  4825.9   315.6  4835.9   315.2
  4905.9   310.2  4965.9   307.4  4971.9  306.03  4975.1  305.41  4975.3  303.81
  4983.2  303.67  4987.6  303.13  4998.2   302.9  5002.6   303.6  5007.6  303.41
  5014.1  304.64  5018.7  304.57  5024.9  305.41  5026.1  306.39  5027.1   306.7
  5037.1   306.9  5087.1   306.5  5097.1   306.6  5157.1     308  5197.1   310.6
  5297.1   316.6  5327.1   318.6  5387.1   324.7  5447.1   328.9  5525.2   335.1
#Mann= 5 , 1 , 0
 4745.90     0.2       0  4745.9   0.155       0  4971.9   0.045       0
  5026.1   0.155       0  5525.2     0.2       0
Bank Sta=4971.90,5026.10
Exp/Cntr=0.3,0.1

Type RM Length L Ch R = 1 ,418587.2,459.1,459.1,459.1
BEGIN DESCRIPTION:
Cross Section Little River 106.0
END DESCRIPTION:
#Sta/Elev= 30
  4661.1   323.9  4701.1   321.3  4771.1   315.9  4831.1   308.9  4851.1   306.7
  4861.1   305.8  4881.1   304.7  4901.1   304.4  4921.1   303.8  4931.1   303.9
  4971.1   304.9  4971.9  304.02  4975.1   303.4  4975.3   301.8  4983.2  301.66
  4987.6  301.12  4998.2  300.89  5002.6  301.59  5007.6   301.4  5014.1  302.63
  5018.7  302.56  5024.9   303.4  5026.1  304.38    5038     306    5048   306.5
    5098     310    5158   313.5    5198   314.9    5228   317.4  5316.1   323.2
#Mann= 5 , 1 , 0
 4661.10     0.2       0  4661.1   0.155       0  4971.9   0.045       0
  5026.1   0.155       0  5316.1     0.2       0
Bank Sta=4971.90,5026.10
Exp/Cntr=0.3,0.1

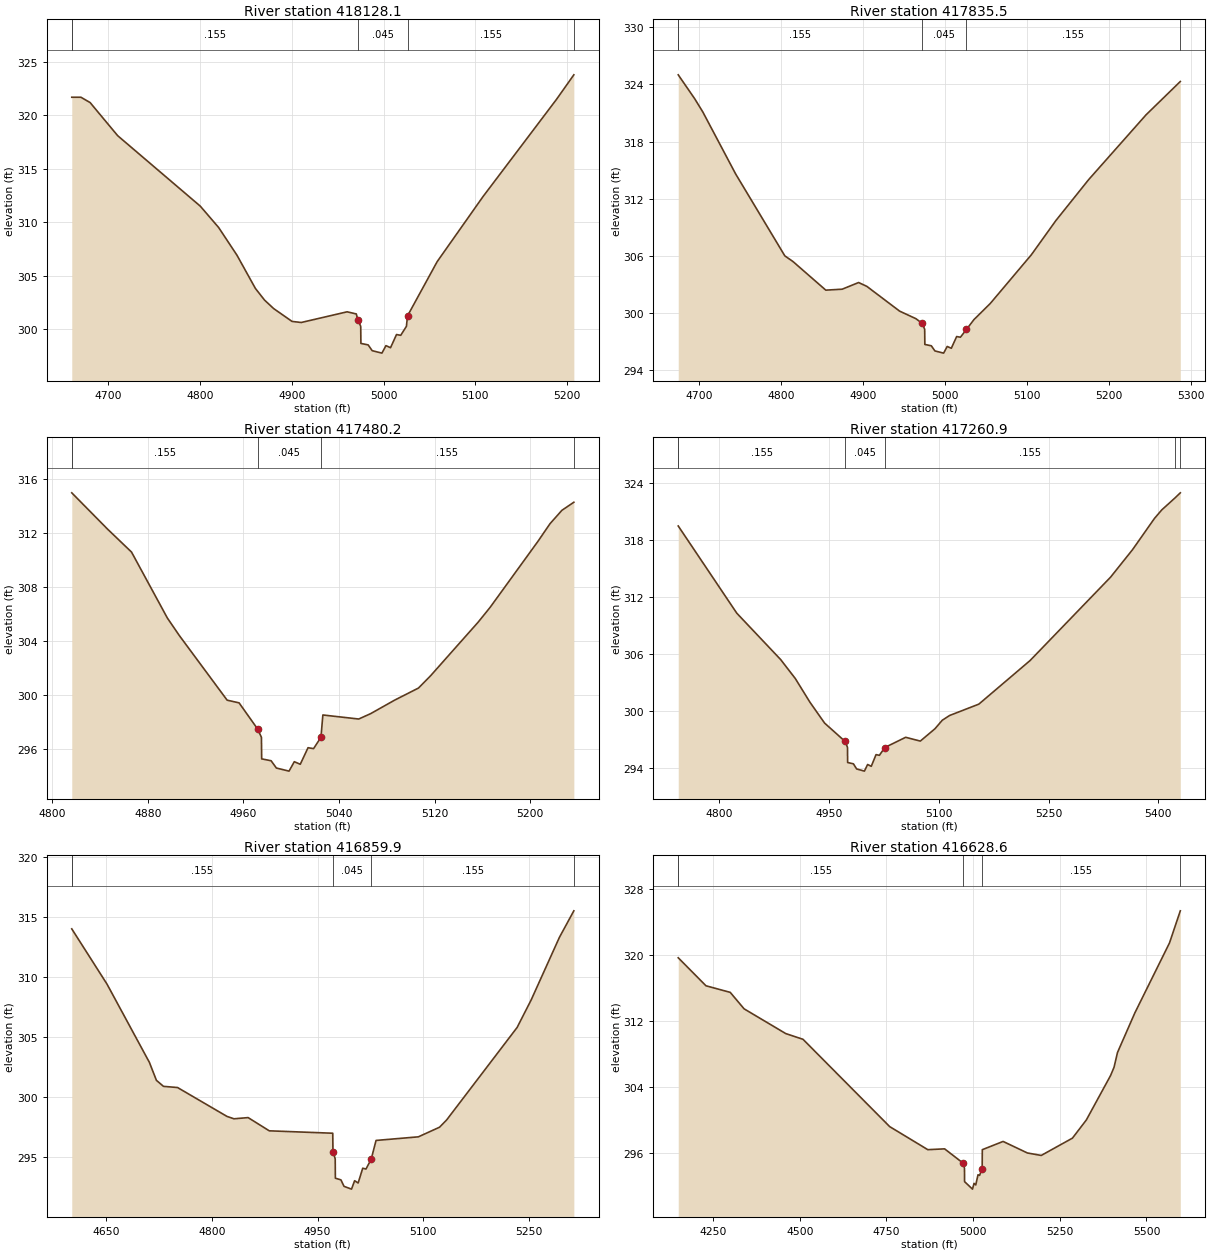
Type RM Length L Ch R = 1 ,418128.1,292.6,292.6,292.6
BEGIN DESCRIPTION:
Cross Section Little River 105.0
END DESCRIPTION:
#Sta/Elev= 30
  4660.3   321.7  4670.3   321.7  4680.3   321.2  4710.3   318.1  4800.3   311.5
  4820.3   309.5  4840.3   306.9  4860.3   303.8  4870.3   302.7  4880.3   301.9
  4900.3   300.7  4910.3   300.6  4960.3   301.6  4970.3   301.4  4971.9  300.86
  4975.1  300.24  4975.3  298.64  4983.2   298.5  4987.6  297.96  4998.2  297.73
  5002.6  298.43  5007.6  298.24  5014.1  299.47  5018.7   299.4  5024.9  300.24
  5026.1  301.22  5058.4   306.3  5108.4   312.4  5188.4   321.5  5207.3   323.8
#Mann= 5 , 1 , 0
 4660.30     0.2       0  4660.3   0.155       0  4971.9   0.045       0
  5026.1   0.155       0  5207.3     0.2       0
Bank Sta=4971.90,5026.10
Exp/Cntr=0.3,0.1

Type RM Length L Ch R = 1 ,417835.5,355.3,355.3,355.3
BEGIN DESCRIPTION:
Cross Section Little River 105.5
END DESCRIPTION:
#Sta/Elev= 30
  4674.5     325  4694.5   322.5  4704.5   321.1  4744.5   314.6  4804.5     306
  4814.5   305.4  4854.5   302.4  4874.5   302.5  4894.5   303.2  4904.5   302.8
  4944.5   300.2  4964.5   299.4  4971.9  298.92  4975.1   298.3  4975.3   296.7
  4983.2  296.56  4987.6  296.02  4998.2  295.79  5002.6  296.49  5007.6   296.3
  5014.1  297.53  5018.7  297.46  5026.1  298.28  5035.1   299.3  5055.1     301
  5105.1   306.1  5135.1   309.7  5175.1     314  5245.1   320.8  5286.9   324.3
#Mann= 5 , 1 , 0
 4674.50     0.2       0  4674.5   0.155       0  4971.9   0.045       0
  5026.1   0.155       0  5286.9     0.2       0
Bank Sta=4971.90,5026.10
Exp/Cntr=0.3,0.1

Type RM Length L Ch R = 1 ,417480.2,219.3,219.3,219.3
BEGIN DESCRIPTION:
Cross Section Little River 104.0
END DESCRIPTION:
#Sta/Elev= 30
  4816.4     315  4846.4   312.3  4866.4   310.6  4896.4   305.7  4906.4   304.4
  4946.4   299.6  4956.4   299.4  4971.9  297.46  4975.1  296.84  4975.3  295.24
  4983.2   295.1  4987.6  294.56  4998.2  294.33  5002.6  295.03  5007.6  294.84
  5014.1  296.07  5018.7     296  5024.9  296.84  5026.5   298.5  5056.5   298.2
  5066.5   298.6  5086.5   299.6  5106.5   300.5  5116.5   301.4  5156.5   305.4
  5166.5   306.5  5206.5   311.4  5216.5   312.7  5226.5   313.7  5236.5   314.3
#Mann= 5 , 1 , 0
 4816.40     0.2       0  4816.4   0.155       0  4971.9   0.045       0
  5024.9   0.155       0  5236.5     0.2       0
Bank Sta=4971.90,5024.90
Exp/Cntr=0.3,0.1

Type RM Length L Ch R = 1 ,417260.9,401,401,401
BEGIN DESCRIPTION:
Cross Section Little River 103.5
END DESCRIPTION:
#Sta/Elev= 30
  4743.8   319.5  4823.8   310.3  4883.8   305.4  4903.8   303.4  4923.8   300.9
  4943.8   298.7  4971.9  296.76  4975.1  296.14  4975.3  294.54  4983.2   294.4
  4987.6  293.86  4998.2  293.63  5002.6  294.33  5007.6  294.14  5014.1  295.37
  5018.7   295.3  5026.1  296.12  5054.6   297.2  5074.6   296.8  5094.6   298.1
  5104.6     299  5114.6   299.5  5154.6   300.7  5224.6   305.3  5334.6   314.1
  5364.6     317  5394.6   320.3  5404.6   321.2  5422.9  322.48  5429.9     323
#Mann= 6 , 1 , 0
 4743.80     0.2       0  4743.8   0.155       0  4971.9   0.045       0
  5026.1   0.155       0  5422.9    0.11       0  5429.9     0.2       0
Bank Sta=4971.90,5026.10
Exp/Cntr=0.3,0.1

Type RM Length L Ch R = 1 ,416859.9,231.3,231.3,231.3
BEGIN DESCRIPTION:
Cross Section Little River 103.0
END DESCRIPTION:
#Sta/Elev= 30
  4601.6     314  4651.6   309.4  4711.6   302.9  4721.6   301.4  4731.6   300.9
  4751.6   300.8  4821.6   298.4  4831.6   298.2  4851.6   298.3  4881.6   297.2
  4971.6     297  4971.9  295.48  4975.1  294.86  4975.3  293.26  4983.2  293.12
  4987.6  292.58  4998.2  292.35  5002.6  293.05  5007.6  292.86  5014.1  294.09
  5018.7  294.02  5026.1  294.84    5033   296.4    5093   296.7    5123   297.5
    5133   298.1    5233   305.8    5253   308.1    5293   313.3  5313.4   315.5
#Mann= 5 , 1 , 0
 4601.60     0.2       0  4601.6   0.155       0  4971.9   0.045       0
  5026.1   0.155       0  5313.4     0.2       0
Bank Sta=4971.90,5026.10
Exp/Cntr=0.3,0.1

Type RM Length L Ch R = 1 ,416628.6,378.7,378.7,378.7
BEGIN DESCRIPTION:
Cross Section Little River 102.5
END DESCRIPTION:
#Sta/Elev= 30
  4149.3   319.7  4229.3   316.3  4299.3   315.5  4339.3   313.5  4459.3   310.5
  4509.3   309.8  4759.3   299.2  4869.3   296.4  4917.7   296.5  4971.9  294.74
  4975.1  294.12  4975.3  292.52  4998.2  291.61  5002.6  292.31  5007.6  292.12
  5014.1  293.35  5018.7  293.28  5026.1   294.1  5026.5   296.4  5086.5   297.4
  5156.5     296  5196.5   295.7  5286.5   297.8  5326.5     300  5396.5   305.4
  5406.5   306.4  5416.5   308.2  5466.5     313  5566.5   321.5  5597.7   325.4
#Mann= 5 , 1 , 0
 4149.30     0.2       0  4149.3   0.155       0  4971.9   0.045       0
  5026.1   0.155       0  5597.7     0.2       0
Bank Sta=4971.90,5026.10
Exp/Cntr=0.3,0.1

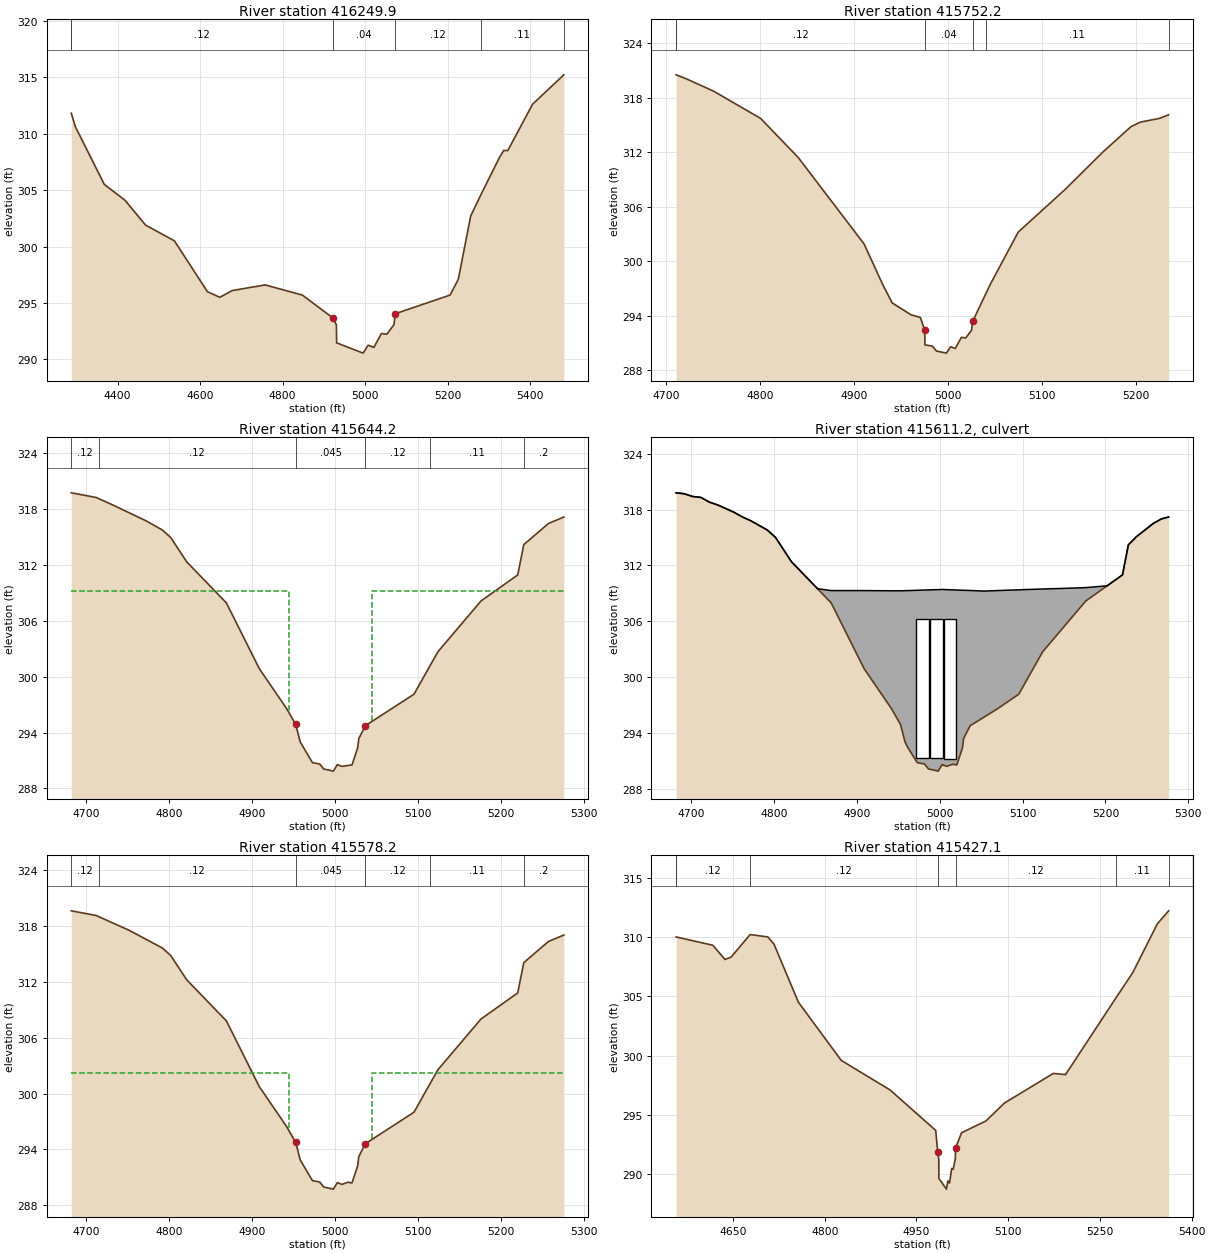
Type RM Length L Ch R = 1 ,416249.9,497.7,497.7,497.7
BEGIN DESCRIPTION:
Cross Section Little River 102.0
END DESCRIPTION:
#Sta/Elev= 30
  4287.7   311.8  4297.7   310.6  4367.7   305.5  4417.7   304.1  4467.7   301.9
  4537.7   300.5  4617.7     296  4647.7   295.5  4677.7   296.1  4757.7   296.6
  4847.7   295.7 4921.32  293.69 4930.28  293.07 4930.84  291.47 4994.96  290.56
 5007.28  291.26 5021.28  291.07 5039.48   292.3 5052.36  292.23 5069.72  293.07
 5073.08  294.05  5205.8   295.7  5225.8   297.1  5255.8   302.7  5280.6  304.59
  5325.8   307.9  5335.8   308.5  5345.8   308.5  5405.8   312.6  5481.5   315.2
#Mann= 6 , 1 , 0
 4287.70     0.2       0  4287.7    0.12       0 4921.32    0.04       0
 5073.08    0.12       0  5280.6    0.11       0  5481.5     0.2       0
Bank Sta=4921.32,5073.08
Exp/Cntr=0.3,0.1

Type RM Length L Ch R = 1 ,415752.2,108,108,108
BEGIN DESCRIPTION:
Cross Section Little River 101.7
END DESCRIPTION:
#Sta/Elev= 30
  4710.5   320.5  4720.5   320.1  4750.5   318.7  4800.5   315.7  4840.5   311.4
  4910.5   301.9  4930.5   297.4  4940.5   295.4  4960.5   294.1  4970.5   293.8
  4975.1  292.39  4975.3  290.79  4983.2  290.65  4987.6  290.11  4998.2  289.88
  5002.6  290.58  5007.6  290.39  5014.1  291.62  5018.7  291.55  5024.9  292.39
  5026.1  293.37  5040.1  296.42  5044.6   297.4  5074.6   303.2  5124.6   307.9
  5164.6     312  5194.6   314.8  5204.6   315.3  5224.6   315.7  5234.6   316.1
#Mann= 6 , 1 , 0
 4710.50     0.2       0  4710.5    0.12       0  4975.1    0.04       0
  5026.1    0.12       0  5040.1    0.11       0  5234.6     0.2       0
Bank Sta=4975.10,5026.10
Exp/Cntr=0.5,0.3

Type RM Length L Ch R = 1 ,415644.2,66,66,66
BEGIN DESCRIPTION:
Upstream Section of Bridge/Culvert/Weir
END DESCRIPTION:
#Sta/Elev= 30
  4681.7  319.77  4711.7  319.27  4731.7  318.47  4771.7  316.77  4791.7  315.77
  4801.7  314.97 4821.03  312.35 4868.88  307.94  4908.7  300.86 4941.59  296.58
 4952.59  294.87 4958.09  292.98 4972.83  290.76 4981.52  290.62 4986.36  290.08
 4998.02  289.85 5002.86  290.55 5008.36  290.36 5020.57  290.52 5027.39  292.36
 5028.71  293.34 5036.63  294.73 5095.37  298.12  5114.9  301.21  5124.3  302.69
 5176.22  308.14 5220.55  310.94  5227.9   314.2  5257.6  316.47  5276.2  317.17
#Mann= 6 , 1 , 0
 4681.70    0.12       0  4715.1    0.12       0 4952.59   0.045       0
 5036.63    0.12       0  5114.9    0.11       0  5227.9     0.2       0
#XS Ineff= 2 , 0
       0    4945   309.2    5045       0   309.2
Bank Sta=4952.59,5036.63
Exp/Cntr=0.5,0.3

Type RM Length L Ch R = 2 ,415611.2,,,
BEGIN DESCRIPTION:
ZEBULON RD
Structure ID: WK_LITR12
END DESCRIPTION:
Bridge Culvert--1,0,-1,-1, 0
Deck Dist Width WeirC Skew NumUp NumDn MinLoCord MaxHiCord MaxSubmerge Is_Ogee
10,46,3,,58,58,,,0.95,0,1,1,,
  4681.7  4691.7  4699.6  4701.7  4711.7  4721.7  4731.7  4741.7  4745.7  4751.7
  4761.7  4771.7  4781.7  4791.7    4799  4801.7 4821.03  4852.5 4868.88  4902.6
  4908.7 4941.59 4952.59  4952.8 4958.09 4961.61 4972.83 4981.52 4986.36 4991.86
 4998.02 5002.86  5003.9 5008.36 5015.51 5020.57 5027.39 5028.71 5036.63  5053.2
 5069.63 5095.37  5103.2  5114.9  5124.3  5154.4 5176.22  5201.8  5216.4 5220.55
  5226.4  5227.6  5227.9  5237.6  5247.6  5257.6  5267.6  5276.2
   319.8   319.7  319.47  319.41  319.31  318.81  318.51  318.11  317.95  317.71
  317.21  316.81  316.31  315.81  315.23  315.01  312.39  309.49  309.29  309.29
  309.29  309.27  309.27  309.27  309.28  309.29  309.32  309.35  309.36  309.38
  309.39  309.41  309.41  309.39  309.37  309.35  309.33  309.32   309.3  309.24
  309.29  309.37   309.4  309.43  309.46  309.54  309.61   309.8  310.72  310.98
  313.66  314.21  314.24   315.1   315.8   316.5     317   317.2
   319.8   319.7  319.46   319.4   319.3   318.8   318.5   318.1  317.94   317.7
   317.2   316.8   316.3   315.8  315.22     315  312.38  309.48  307.97  301.97
  300.89  296.61   294.9  294.83  293.01  292.39  290.79  290.65  290.11  290.01
  289.88  290.58  290.54  290.39  290.62  290.55  292.39  293.37  294.76  295.67
  296.58  298.15  299.39  301.24  302.72  305.88  308.17  309.79  310.71  310.97
  313.65   314.2  314.23   315.1   315.8   316.5     317   317.2
  4681.7  4691.7  4699.6  4701.7  4711.7  4721.7  4731.7  4741.7  4745.7  4751.7
  4761.7  4771.7  4781.7  4791.7    4799  4801.7 4821.03  4852.5 4868.88  4902.6
  4908.7 4941.59 4952.59  4952.8 4958.09 4961.61 4972.83 4981.52 4986.36 4991.86
 4998.02 5002.86  5003.9 5008.36 5015.51 5020.57 5027.39 5028.71 5036.63  5053.2
 5069.63 5095.37  5103.2  5114.9  5124.3  5154.4 5176.22  5201.8  5216.4 5220.55
  5226.4  5227.6  5227.9  5237.6  5247.6  5257.6  5267.6  5276.2
   319.8   319.7  319.47  319.41  319.31  318.81  318.51  318.11  317.95  317.71
  317.21  316.81  316.31  315.81  315.23  315.01  312.39  309.49  309.29  309.29
  309.29  309.27  309.27  309.27  309.28  309.29  309.32  309.35  309.36  309.38
  309.39  309.41  309.41  309.39  309.37  309.35  309.33  309.32   309.3  309.24
  309.29  309.37   309.4  309.43  309.46  309.54  309.61   309.8  310.72  310.98
  313.66  314.21  314.24   315.1   315.8   316.5     317   317.2
   319.7   319.6  319.36   319.3   319.2   318.7   318.4     318  317.84   317.6
   317.1   316.7   316.2   315.7  315.12   314.9  312.28  309.38  307.87  301.87
  300.79  296.51   294.8  294.73  292.91  292.29  290.69  290.55  290.01  289.91
  289.78  290.48  290.44  290.29  290.52  290.45  292.29  293.27  294.66  295.57
  296.48  298.05  299.29  301.14  302.62  305.78  308.07  309.69  310.61  310.87
  313.55   314.1  314.13     315   315.7   316.4   316.9   317.1
BR Coef= 1 , 0 , 0 ,1.25, 0 ,,,0.8,-1,2,0,
Wspro=,,,, 1 ,,,, 0 ,,,, 0 ,,,,-1 ,-1 ,-1 , 0 , 0 , 0 , 0 , 0
Culvert=2,15.0,15.0,46.0,0.015,0.7,1.0,8,3,291.28,4978.90,291.18,4978.90,Culvert #1  ,0,10
Culvert=2,15.0,15.0,46.0,0.015,0.7,1.0,8,3,291.27,4995.90,291.17,4995.90,Culvert #2  ,0,10
Culvert=2,15.0,15.0,46.0,0.015,0.7,1.0,8,3,291.19,5012.10,291.08,5012.10,Culvert #3  ,0,10
BC Design=,, 0 ,, 0 ,,,,,,
BR U #Sta/Elev= 58
  4681.7   319.8  4691.7   319.7  4699.6  319.46  4701.7   319.4  4711.7   319.3
  4721.7   318.8  4731.7   318.5  4741.7   318.1  4745.7  317.94  4751.7   317.7
  4761.7   317.2  4771.7   316.8  4781.7   316.3  4791.7   315.8    4799  315.22
  4801.7     315 4821.03  312.38  4852.5  309.48 4868.88  307.97  4902.6  301.97
  4908.7  300.89 4941.59  296.61 4952.59   294.9  4952.8  294.83 4958.09  293.01
 4961.61  292.39 4972.83  290.79 4981.52  290.65 4986.36  290.11 4991.86  290.01
 4998.02  289.88 5002.86  290.58  5003.9  290.54 5008.36  290.39 5015.51  290.62
 5020.57  290.55 5027.39  292.39 5028.71  293.37 5036.63  294.76  5053.2  295.67
 5069.63  296.58 5095.37  298.15  5103.2  299.39  5114.9  301.24  5124.3  302.72
  5154.4  305.88 5176.22  308.17  5201.8  309.79  5216.4  310.71 5220.55  310.97
  5226.4  313.65  5227.6   314.2  5227.9  314.23  5237.6   315.1  5247.6   315.8
  5257.6   316.5  5267.6     317  5276.2   317.2
BR U #Mann= 6
 4681.70    0.12  4715.1    0.12 4952.59   0.045 5036.63    0.12  5114.9    0.11
  5227.9     0.2
BR U Banks=4952.59,5036.63
BR D #Sta/Elev= 58
  4681.7   319.7  4691.7   319.6  4699.6  319.36  4701.7   319.3  4711.7   319.2
  4721.7   318.7  4731.7   318.4  4741.7     318  4745.7  317.84  4751.7   317.6
  4761.7   317.1  4771.7   316.7  4781.7   316.2  4791.7   315.7    4799  315.12
  4801.7   314.9 4821.03  312.28  4852.5  309.38 4868.88  307.87  4902.6  301.87
  4908.7  300.79 4941.59  296.51 4952.59   294.8  4952.8  294.73 4958.09  292.91
 4961.61  292.29 4972.83  290.69 4981.52  290.55 4986.36  290.01 4991.86  289.91
 4998.02  289.78 5002.86  290.48  5003.9  290.44 5008.36  290.29 5015.51  290.52
 5020.57  290.45 5027.39  292.29 5028.71  293.27 5036.63  294.66  5053.2  295.57
 5069.63  296.48 5095.37  298.05  5103.2  299.29  5114.9  301.14  5124.3  302.62
  5154.4  305.78 5176.22  308.07  5201.8  309.69  5216.4  310.61 5220.55  310.87
  5226.4  313.55  5227.6   314.1  5227.9  314.13  5237.6     315  5247.6   315.7
  5257.6   316.4  5267.6   316.9  5276.2   317.1
BR D #Mann= 6
 4681.70    0.12  4715.1    0.12 4952.59   0.045 5036.63    0.12  5114.9    0.11
  5227.9     0.2
BR D Banks=4952.59,5036.63

Type RM Length L Ch R = 1 ,415578.2,151.1,151.1,151.1
BEGIN DESCRIPTION:
Downstream Section of Bridge/Culvert/Weir
END DESCRIPTION:
#Sta/Elev= 30
  4681.7  319.64  4711.7  319.14  4751.7  317.54  4791.7  315.64  4801.7  314.84
 4821.03  312.22 4868.88  307.81  4908.7  300.73 4941.59  296.45 4952.59  294.74
 4958.09  292.85 4972.83  290.63 4981.52  290.49 4986.36  289.95 4998.02  289.72
 5002.86  290.42 5008.36  290.23 5015.51  290.46 5020.57  290.39 5027.39  292.23
 5028.71  293.21 5036.63   294.6 5095.37  297.99  5114.9  301.08  5124.3  302.56
 5176.22  308.01 5220.55  310.81  5227.9  314.07  5257.6  316.34  5276.2  317.04
#Mann= 6 , 1 , 0
 4681.70    0.12       0  4715.1    0.12       0 4952.59   0.045       0
 5036.63    0.12       0  5114.9    0.11       0  5227.9     0.2       0
#XS Ineff= 2 , 0
       0    4945   302.2    5045       0   302.2
Bank Sta=4952.59,5036.63
Exp/Cntr=0.5,0.3

Type RM Length L Ch R = 1 ,415427.1,350.3,350.3,350.3
BEGIN DESCRIPTION:
Cross Section Little River 101.5
END DESCRIPTION:
#Sta/Elev= 30
    4557     310    4617   309.3    4637   308.1    4647   308.3    4678   310.2
    4707     310    4717   309.4    4757   304.5    4827   299.6    4907   297.1
  4981.5   293.7 4984.83  291.88 4986.55  291.26 4986.66  289.66 4999.03  288.75
  5001.4  289.45  5004.1  289.26 5007.61  290.49  5010.1  290.42 5013.45  291.26
 5014.09  292.24  5023.8   293.5  5063.8   294.5  5093.8     296  5173.8   298.5
  5193.8   298.4    5276  304.85  5303.8     307  5343.8   311.1  5362.3   312.2
#Mann= 7 , 1 , 0
 4557.00     0.2       0    4557    0.12       0    4678    0.12       0
 4984.83   0.045       0 5014.09    0.12       0    5276    0.11       0
  5362.3     0.2       0
Bank Sta=4984.83,5014.09
Exp/Cntr=0.3,0.1

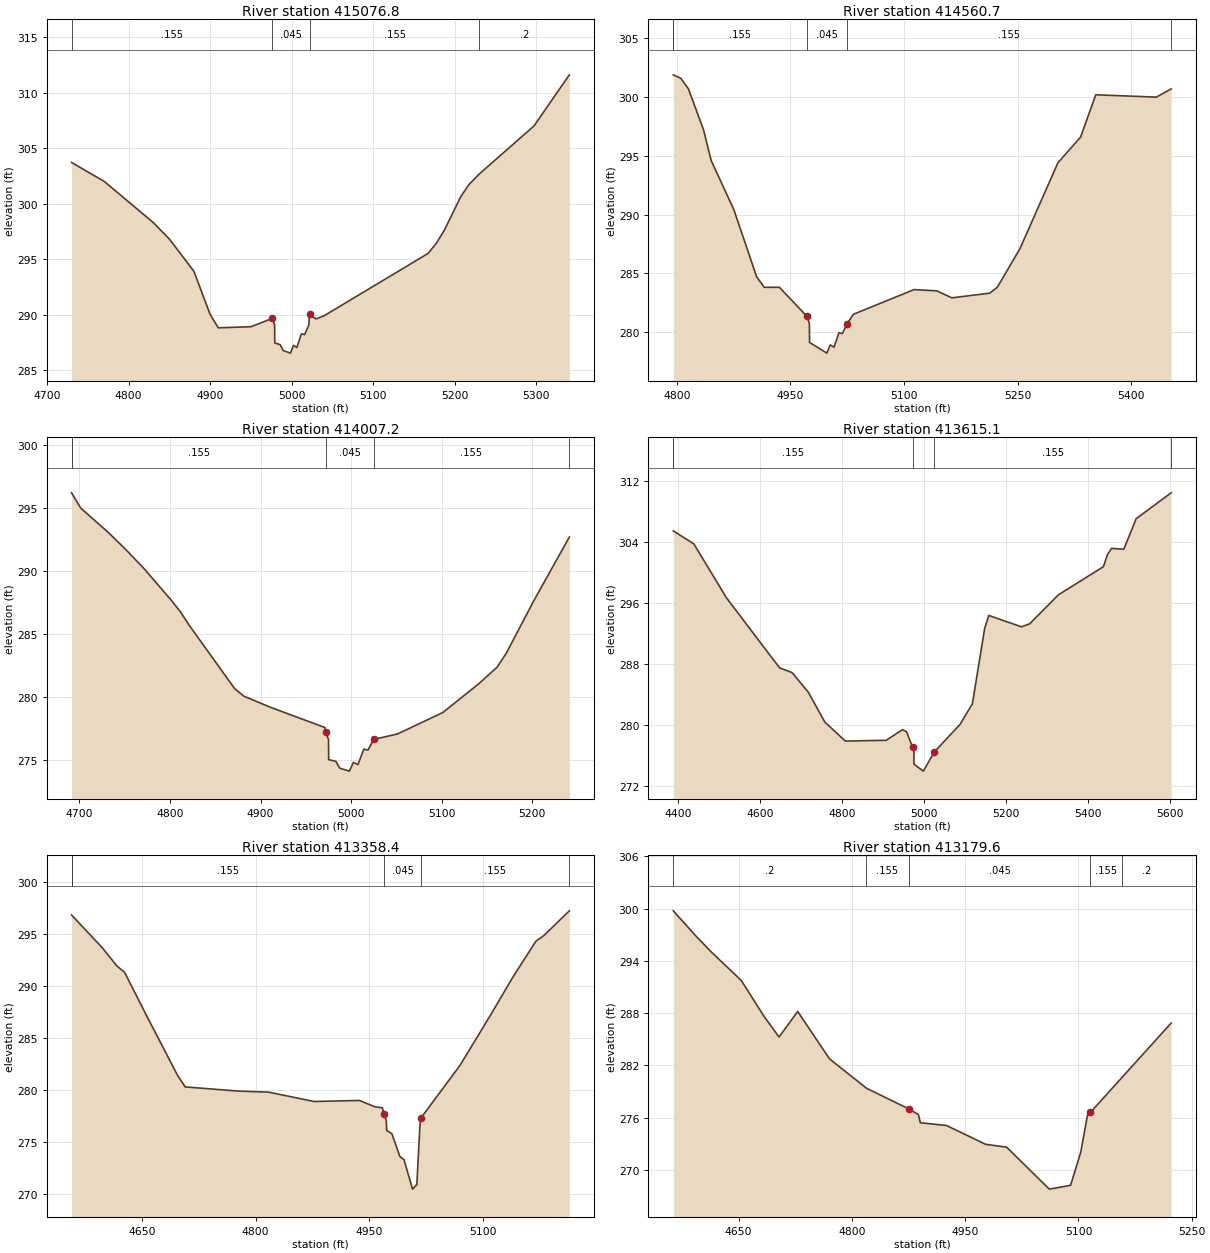
Type RM Length L Ch R = 1 ,415076.8,516.1,516.1,516.1
BEGIN DESCRIPTION:
Cross Section Little River 101.0
END DESCRIPTION:
#Sta/Elev= 30
    4730   303.7    4770     302    4830   298.3    4850   296.8    4880   293.9
    4900     290    4910   288.8    4950   288.9  4976.4  289.65 4979.08  289.03
 4979.25  287.43 4985.89  287.29 4989.58  286.75 4998.49  286.52 5002.18  287.22
 5006.38  287.03 5011.84  288.26 5015.71  288.19 5020.92  289.03 5021.92  290.01
    5030   289.6    5040   289.9  5167.2   295.5  5177.2   296.4  5187.2   297.6
  5207.2   300.6  5217.2   301.7  5230.3  302.68  5297.2     307  5340.5   311.6
#Mann= 4 , 1 , 0
 4730.00   0.155       0  4976.4   0.045       0 5021.92   0.155       0
  5230.3     0.2       0
Bank Sta=4976.40,5021.92
Exp/Cntr=0.3,0.1

Type RM Length L Ch R = 1 ,414560.7,553.5,553.5,553.5
BEGIN DESCRIPTION:
Cross Section Little River 100.0
END DESCRIPTION:
#Sta/Elev= 30
  4795.4   301.9  4805.4   301.6  4815.4   300.7  4835.4   297.2  4845.4   294.6
  4875.4   290.4  4905.4   284.7  4915.4   283.8  4935.4   283.8  4971.9  281.32
  4975.1   280.7  4975.3   279.1  4998.2  278.19  5002.6  278.89  5007.6   278.7
  5014.1  279.93  5018.7  279.86  5024.9   280.7  5033.2   281.5  5113.2   283.6
  5143.2   283.5  5163.2   282.9  5213.2   283.3  5223.2   283.8  5253.2   287.1
  5303.2   294.4  5333.2   296.6  5353.2   300.2  5433.2     300  5452.7   300.7
#Mann= 5 , 1 , 0
 4795.40     0.2       0  4795.4   0.155       0  4971.9   0.045       0
  5024.9   0.155       0  5452.7     0.2       0
Bank Sta=4971.90,5024.90
Exp/Cntr=0.3,0.1

Type RM Length L Ch R = 1 ,414007.2,392.1,392.1,392.1
BEGIN DESCRIPTION:
Cross Section Little River 99.0
END DESCRIPTION:
#Sta/Elev= 30
  4691.3   296.2  4701.3     295  4731.3   293.1  4751.3   291.7  4771.3   290.2
  4801.3   287.7  4811.3   286.8  4821.3   285.7  4871.3   280.7  4881.3   280.1
  4911.3   279.2  4971.3   277.6  4971.9  277.28  4975.1  276.66  4975.3  275.06
  4983.2  274.92  4987.6  274.38  4998.2  274.15  5002.6  274.85  5007.6  274.66
  5014.1  275.89  5018.7  275.82  5024.9  276.66  5051.5   277.1  5101.5   278.8
  5141.5   281.1  5161.5   282.4  5171.5   283.5  5201.5   287.6  5241.1   292.7
#Mann= 5 , 1 , 0
 4691.30     0.2       0  4691.3   0.155       0  4971.9   0.045       0
  5024.9   0.155       0  5241.1     0.2       0
Bank Sta=4971.90,5024.90
Exp/Cntr=0.3,0.1

Type RM Length L Ch R = 1 ,413615.1,256.7,256.7,256.7
BEGIN DESCRIPTION:
Cross Section Little River 98.5
END DESCRIPTION:
#Sta/Elev= 30
  4387.4   305.5  4437.4   303.8  4517.4   296.7  4627.4   288.9  4647.4   287.5
  4677.4   286.9  4717.4   284.3  4757.4   280.4  4807.4   277.9  4907.4     278
  4947.4   279.4  4957.4   279.1  4971.9  277.08  4975.1  276.46  4975.3  274.86
  4998.2  273.95  5024.9  276.46    5088   280.1    5118   282.8    5148   292.7
    5158   294.4    5238   292.9    5258   293.3    5328   297.1    5438   300.8
    5448   302.4    5458   303.2    5488   303.1    5518   307.1  5603.4   310.5
#Mann= 5 , 1 , 0
 4387.40     0.2       0  4387.4   0.155       0  4971.9   0.045       0
  5024.9   0.155       0  5603.4     0.2       0
Bank Sta=4971.90,5024.90
Exp/Cntr=0.3,0.1

Type RM Length L Ch R = 1 ,413358.4,178.8,178.8,178.8
BEGIN DESCRIPTION:
Cross Section Little River 98.0
END DESCRIPTION:
#Sta/Elev= 30
    4557   296.8    4597   293.7    4617   291.9    4627   291.3    4657     287
    4697   281.4    4707   280.3    4777   279.9    4817   279.8    4877   278.9
    4937     279    4957   278.4    4967   278.3  4969.9   277.7 4972.42  277.04
 4972.92  276.12 4979.84   275.8  4990.2  273.64 4995.78  273.31 5007.08  270.49
 5012.72  270.93  5015.4  274.71 5017.18  276.97 5017.96   277.3    5070   282.4
    5110   287.2    5140   290.9    5170   294.3    5180   294.8    5214   297.2
#Mann= 5 , 1 , 0
 4557.00     0.2       0    4557   0.155       0  4969.9   0.045       0
 5017.96   0.155       0    5214     0.2       0
Bank Sta=4969.90,5017.96
Exp/Cntr=0.5,0.3

Type RM Length L Ch R = 1 ,413179.6,30,30,30
BEGIN DESCRIPTION:
Upstream Section of Bridge/Culvert/Weir
END DESCRIPTION:
#Sta/Elev= 21
  4563.5  299.75  4593.5  296.85  4613.5  295.05  4653.5  291.75  4683.5  287.65
  4703.5  285.25  4728.2  288.19  4770.4  282.74  4819.3  279.37  4875.5  276.99
  4888.1  276.33  4890.6  275.41  4925.2  275.09    4977  272.93  5004.9   272.6
  5061.4  267.78  5089.6  268.22    5103     272  5111.9  276.26  5115.8  276.59
  5222.7  286.85
#Mann= 5 , 1 , 0
 4563.50     0.2       0  4818.6   0.155       0  4875.5   0.045       0
  5115.8   0.155       0  5157.9     0.2       0
#XS Ineff= 2 , 0
       0    4865   274.8  5124.4       0   274.8
Bank Sta=4875.50,5115.80
Exp/Cntr=0.5,0.3