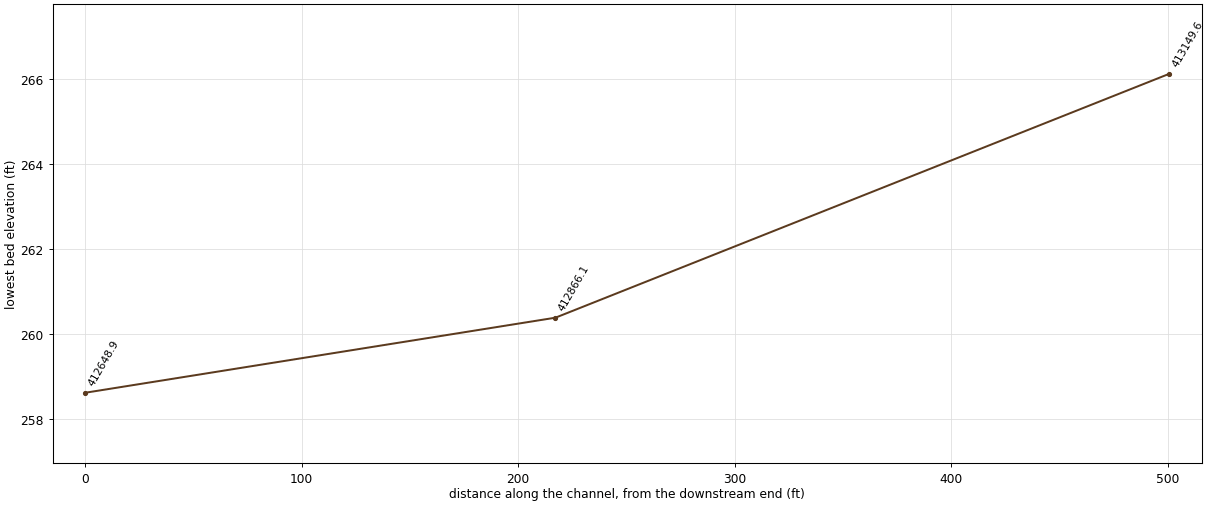
HEC-RAS study Little_River_FINAL.prj: Little River Detail Study

--- Little_River_FINAL.g01 (geometry) --- (continued)

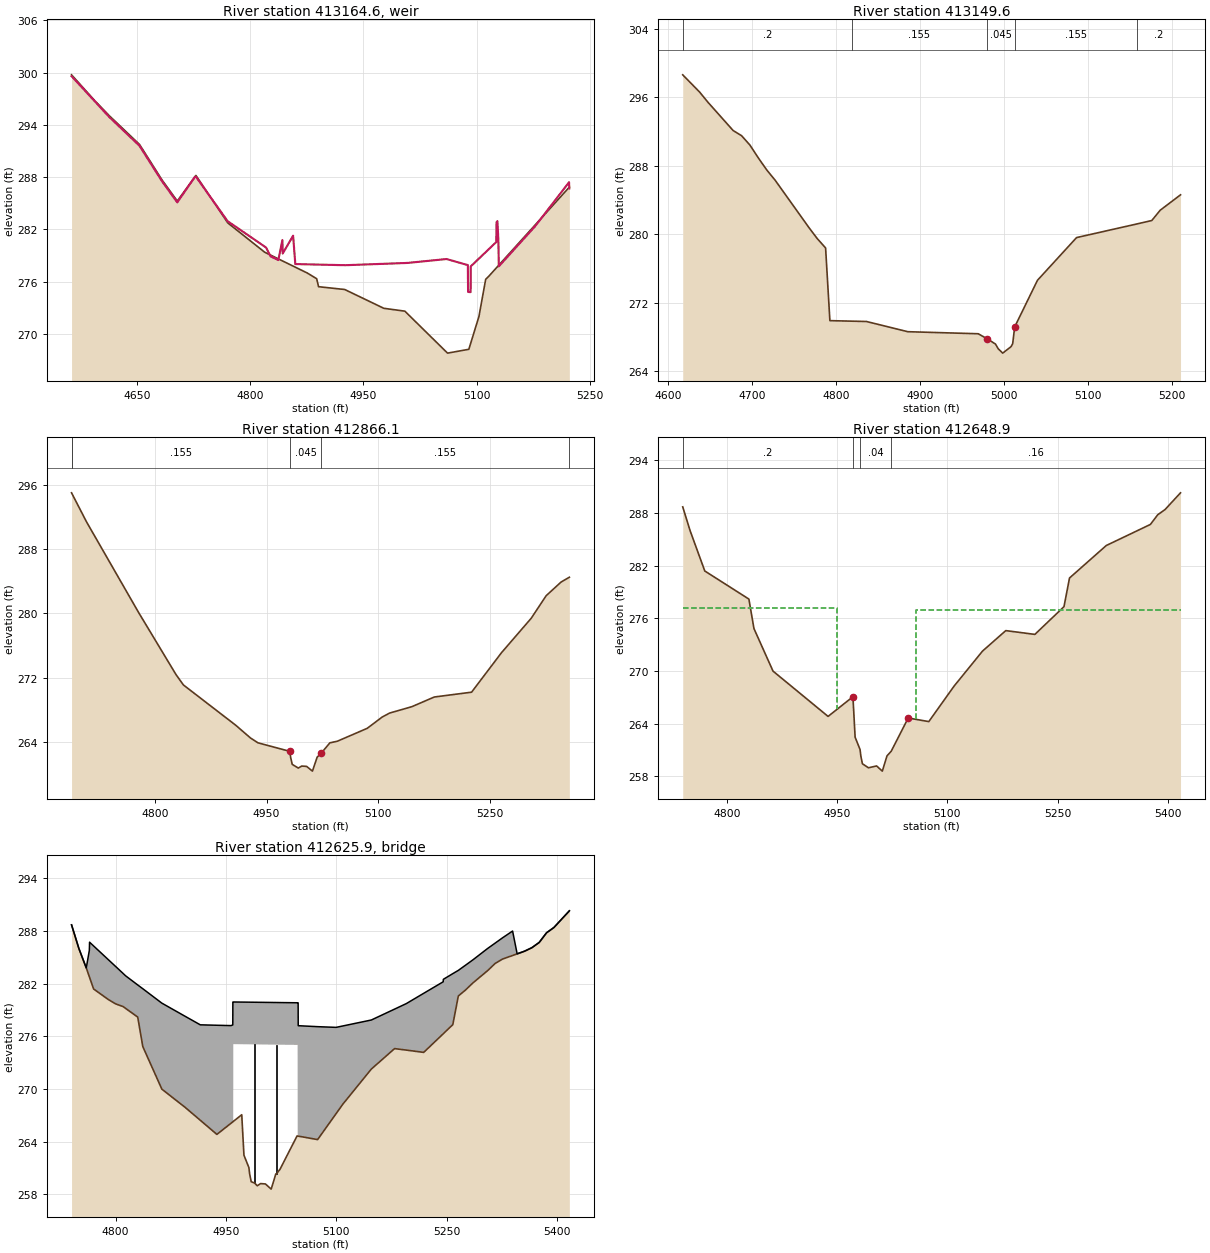
Type RM Length L Ch R = 5 ,413164.6,,,
BEGIN DESCRIPTION:
ZEBULON RD
Structure ID: WK_LITR11DAM
END DESCRIPTION:
#Inline Weir SE= 30
  4563.5   299.6  4613.5   294.9  4653.5   291.6  4683.5   287.5  4703.5   285.1
  4726.9  288.04  4728.2  288.05  4770.1  282.94  4821.1  279.91  4826.9  278.91
  4837.3  278.47  4842.7  280.77  4843.1  279.22  4856.9  281.27  4859.8  278.01
    4926  277.88  5008.1  278.14  5060.1  278.59  5088.3  277.89  5088.6  274.81
    5092  274.79  5092.1  277.74  5125.9  280.54  5126.3  282.83  5127.4  282.95
  5128.7   280.8  5129.3  277.75  5177.2  282.34  5222.3  287.41  5222.7   286.7
IW Dist,WD,Coef,Skew,MaxSub,Min_El,Is_Ogee,SpillHt,DesHd
10.0,10.0,3.0,,0.95,, 0 ,,,2.0,2.0,

Type RM Length L Ch R = 1 ,413149.6,283.5,283.5,283.5
BEGIN DESCRIPTION:
Cross Section FIELD_DS
Located At: ZEBULON RD
END DESCRIPTION:
#Sta/Elev= 30
  4617.6   298.6  4637.6   296.6  4647.6   295.4  4677.6   292.1  4687.6   291.5
  4697.6   290.4  4707.6   288.9  4717.6   287.5  4727.6   286.3  4767.6   280.8
  4777.6   279.5  4787.6   278.4  4792.7  269.92  4818.6  269.86  4836.2  269.82
  4885.4  268.63  4969.2  268.39  4979.9   267.8  4989.7  267.19    4993  266.64
  4998.3  266.13  5008.3  266.89  5010.2  267.24  5012.6  269.19  5039.7  274.63
  5086.2  279.61  5157.9   281.2  5175.7   281.6  5185.7   282.8  5209.9   284.6
#Mann= 5 , 1 , 0
 4617.60     0.2       0  4818.6   0.155       0  4979.9   0.045       0
  5012.6   0.155       0  5157.9     0.2       0
Bank Sta=4979.90,5012.60
Exp/Cntr=0.3,0.1

Type RM Length L Ch R = 1 ,412866.1,217.2,217.2,217.2
BEGIN DESCRIPTION:
Cross Section Little River 97.7
END DESCRIPTION:
#Sta/Elev= 30
  4688.5     295  4708.5   291.4  4778.5   280.1  4828.5   272.4  4838.5   271.1
  4908.5   266.1  4928.5   264.5  4938.5   263.9  4981.2  262.84  4982.3  262.08
  4984.4  261.22  4992.6  260.76  4997.1  261.01  5003.7  260.97  5011.5  260.38
  5017.8  262.11  5023.6  262.65  5034.9   263.9  5044.9   264.1  5084.9   265.7
  5104.9   267.1  5114.9   267.6  5144.9   268.4  5174.9   269.6  5224.9   270.2
  5264.9   275.1  5304.9   279.4  5324.9   282.2  5344.9   283.9    5356   284.5
#Mann= 5 , 1 , 0
 4688.50     0.2       0  4688.5   0.155       0  4981.2   0.045       0
  5023.6   0.155       0    5356     0.2       0
Bank Sta=4981.20,5023.60
Exp/Cntr=0.5,0.3

Type RM Length L Ch R = 1 ,412648.9,46,46,46
BEGIN DESCRIPTION:
Upstream Section of Bridge/Culvert/Weir
END DESCRIPTION:
#Sta/Elev= 30
    4740   288.7    4750     286    4770   281.4    4830   278.2  4836.9  274.84
  4862.8     270  4937.7  264.84  4971.5  267.08  4974.5  262.47  4981.2  261.07
  4982.3  260.31  4984.4  259.45  4992.6  258.99  5003.7   259.2  5011.5  258.61
  5017.8  260.34  5023.6  260.88  5046.7  264.66  5074.7  264.25    5109  268.28
  5147.8  272.28  5179.4  274.61    5219  274.18  5258.6  277.34  5266.1   280.6
  5316.1   284.3  5376.1   286.7  5386.1   287.8  5396.1   288.4  5417.1   290.3
#Mann= 4 , 1 , 0
 4740.00     0.2       0  4971.5    0.16       0  4981.2    0.04       0
  5023.6    0.16       0
#XS Ineff= 2 , 0
       0  4949.7   277.2  5057.6       0     277
Bank Sta=4971.50,5046.70
Exp/Cntr=0.5,0.3

Type RM Length L Ch R = 3 ,412625.9,,,
BEGIN DESCRIPTION:
MITCHELL RD
Structure ID: WK_LITR11
END DESCRIPTION:
Bridge Culvert--1,0,-1,-1, 0
Deck Dist Width WeirC Skew NumUp NumDn MinLoCord MaxHiCord MaxSubmerge Is_Ogee
10,26,2.6,, 49, 49,,,0.95,0,1,1,,
    4740    4750    4760  4764.2  4764.5    4770    4790    4800    4810  4813.4
    4830  4836.9  4862.8  4894.5  4915.1  4937.7  4956.9 4959.29  4959.4 4959.91
    4960 5047.49  5047.6  5048.2 5048.31  5074.7  5099.8    5109  5147.8  5179.4
  5195.4    5219  5245.5  5245.7  5258.6  5266.1  5275.7  5286.1  5305.7  5316.1
  5326.1  5339.9  5346.1  5356.1  5366.1  5376.1  5386.1  5396.1  5417.1
   288.7     286   283.8   285.8  286.73   286.3  284.74  283.96  283.18  282.91
  281.86  281.43  279.79  278.29  277.32  277.27  277.23  277.31  279.91  279.92
  279.92  279.83  279.83  279.82  277.22  277.11  277.03  277.19  277.87  279.11
  279.74  280.91  282.22   282.5  283.15  283.52   284.1  284.73     286  286.62
  287.22     288   285.4   285.7   286.1   286.7   287.8   288.4   290.3
   288.7     286   283.8  282.79  282.72   281.4   280.2   279.7   279.4   279.2
   278.2  274.84     270  267.92  266.45  264.84  266.11  266.27  266.28  266.31
  275.12  275.03  264.65  264.64  264.64  264.25   267.2  268.28  272.28  274.61
  274.44  274.18  276.29  276.31  277.34   280.6  281.27   282.1  283.47   284.3
   284.8  285.21   285.4   285.7   286.1   286.7   287.8   288.4   290.3
    4740    4750    4760  4764.2  4764.5    4770    4790    4800    4810  4813.4
    4830  4836.9  4862.8  4894.5  4915.1  4937.7  4956.9 4959.29  4959.4 4959.91
    4960 5047.49  5047.6  5048.2 5048.31  5074.7  5099.8    5109  5147.8  5179.4
  5195.4    5219  5245.5  5245.7  5258.6  5266.1  5276.1  5286.1  5305.7  5316.1
  5326.1  5339.9  5346.1  5356.1  5366.1  5376.1  5386.1  5396.1  5417.1
   288.7     286   283.8   285.8  286.73   286.3  284.74  283.96  283.18  282.91
  281.86  281.43  279.79  278.29  277.32  277.27  277.23  277.31  279.91  279.92
  279.92  279.83  279.83  279.82  277.22  277.11  277.03  277.19  277.87  279.11
  279.74  280.91  282.22   282.5  283.15  283.52  284.12  284.73     286  286.62
  287.22     288   285.4   285.7   286.1   286.7   287.8   288.4   290.3
  288.41  285.71  283.51   282.5  282.43  281.11  279.91  279.41  279.11  278.91
  277.91  274.55  269.71  267.63  266.16  264.55  265.82  265.98  265.99  266.02
  274.83  274.74  264.36  264.35  264.35  263.96  266.91  267.99  271.99  274.32
  274.15  273.89     276  276.02  277.05  280.31  281.01  281.81  283.18  284.01
  284.51  284.92  285.11  285.41  285.81  286.41  287.51  288.11  290.01
Pier Skew, UpSta & Num, DnSta & Num=,4988.9, 2 ,4988.9, 2 , 0 , 0 , 0 ,,
       1       1
  258.27  276.09
       1       1
  257.98   275.8
Pier Skew, UpSta & Num, DnSta & Num=,5019.0, 2 ,5019.0, 2 , 0 , 0 , 0 ,,
       1       1
  259.36  276.06
       1       1
  259.07  275.77
Abutment Skew #Up #Dn=, 2 , 2
 4959.80 4974.50
  275.12  262.47
 4959.80 4974.50
  274.83  262.18
BR Coef= 1 , 1 , 0 ,1.25, 0 ,,,0.8,0,2,0,
Wspro=,,,, 1 ,,,, 0 ,,,, 0 ,,,,-1 ,-1 ,-1 , 0 , 0 , 0 , 0 , 0
BC Design=,, 0 ,, 0 ,,,,,,
BR U #Sta/Elev= 85
    4740   288.7    4750     286    4760   283.8  4764.2  282.79  4764.5  282.72
    4770   281.4    4780   280.8    4790   280.2    4800   279.7    4810   279.4
  4813.4   279.2    4820   278.8    4830   278.2  4836.9  274.84  4862.8     270
  4863.8  269.93  4894.5  267.92  4915.1  266.45  4937.7  264.84  4956.9  266.11
 4959.29  266.27  4959.4  266.28 4959.51  266.29  4959.8   266.3 4959.91  266.31
    4960  266.32  4971.5  267.08  4974.4  262.62  4974.5  262.47  4981.2  261.07
  4982.3  260.31  4984.4  259.45  4988.9  259.31  4992.6  258.99  4997.1  259.24
  5003.7   259.2  5011.5  258.61  5015.7  259.74  5017.8  260.34    5019  260.38
  5023.6  260.88  5046.7  264.66  5046.8  264.66  5046.9  264.66 5047.49  264.65
  5047.6  264.65  5047.7  264.65 5048.09  264.64  5048.2  264.64 5048.31  264.64
  5051.9  264.59  5074.7  264.25  5099.8   267.2    5109  268.28    5147   272.2
  5147.8  272.28  5179.4  274.61  5195.4  274.44    5219  274.18  5245.5  276.29
  5245.7  276.31  5255.7  277.11  5258.6  277.34  5265.7  280.43  5266.1   280.6
  5275.7  281.27  5276.1   281.3  5285.7  282.07  5286.1   282.1  5296.1   282.8
  5305.7  283.47  5306.1   283.5  5316.1   284.3  5326.1   284.8  5335.7  285.09
  5336.1   285.1  5339.9  285.21  5346.1   285.4  5356.1   285.7  5366.1   286.1
  5376.1   286.7  5386.1   287.8  5396.1   288.4  5416.1   290.2  5417.1   290.3
BR U #Mann= 4
 4740.00     0.2  4971.5    0.16  4981.2    0.04  5023.6    0.16
BR U Banks=4971.50,5046.70
BR D #Sta/Elev= 85
    4740  288.41    4750  285.71    4760  283.51  4764.2   282.5  4764.5  282.43
    4770  281.11    4780  280.51    4790  279.91    4800  279.41    4810  279.11
  4813.4  278.91    4820  278.51    4830  277.91  4836.9  274.55  4862.8  269.71
  4863.8  269.64  4894.5  267.63  4915.1  266.16  4937.7  264.55  4956.9  265.82
 4959.29  265.98  4959.4  265.99 4959.51     266  4959.8  266.01 4959.91  266.02
    4960  266.03  4971.5  266.79  4974.4  262.33  4974.5  262.18  4981.2  260.78
  4982.3  260.02  4984.4  259.16  4988.9  259.02  4992.6   258.7  4997.1  258.95
  5003.7  258.91  5011.5  258.32  5015.7  259.45  5017.8  260.05    5019  260.09
  5023.6  260.59  5046.7  264.37  5046.8  264.37  5046.9  264.37 5047.49  264.36
  5047.6  264.36  5047.7  264.36 5048.09  264.35  5048.2  264.35 5048.31  264.35
  5051.9   264.3  5074.7  263.96  5099.8  266.91    5109  267.99    5147  271.91
  5147.8  271.99  5179.4  274.32  5195.4  274.15    5219  273.89  5245.5     276
  5245.7  276.02  5255.7  276.82  5258.6  277.05  5265.7  280.14  5266.1  280.31
  5275.7  280.98  5276.1  281.01  5285.7  281.78  5286.1  281.81  5296.1  282.51
  5305.7  283.18  5306.1  283.21  5316.1  284.01  5326.1  284.51  5335.7   284.8
  5336.1  284.81  5339.9  284.92  5346.1  285.11  5356.1  285.41  5366.1  285.81
  5376.1  286.41  5386.1  287.51  5396.1  288.11  5416.1  289.91  5417.1  290.01
BR D #Mann= 4
 4740.00     0.2  4971.5    0.16  4981.2    0.04  5023.6    0.16
BR D Banks=4971.50,5046.70