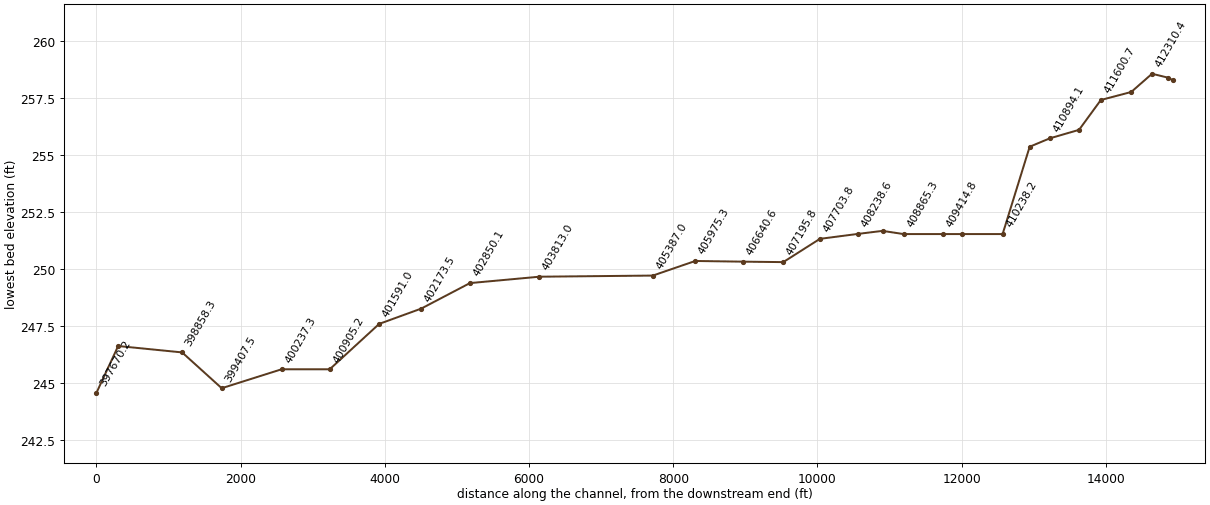
HEC-RAS study Little_River_FINAL.prj: Little River Detail Study

--- Little_River_FINAL.g01 (geometry) --- (continued)

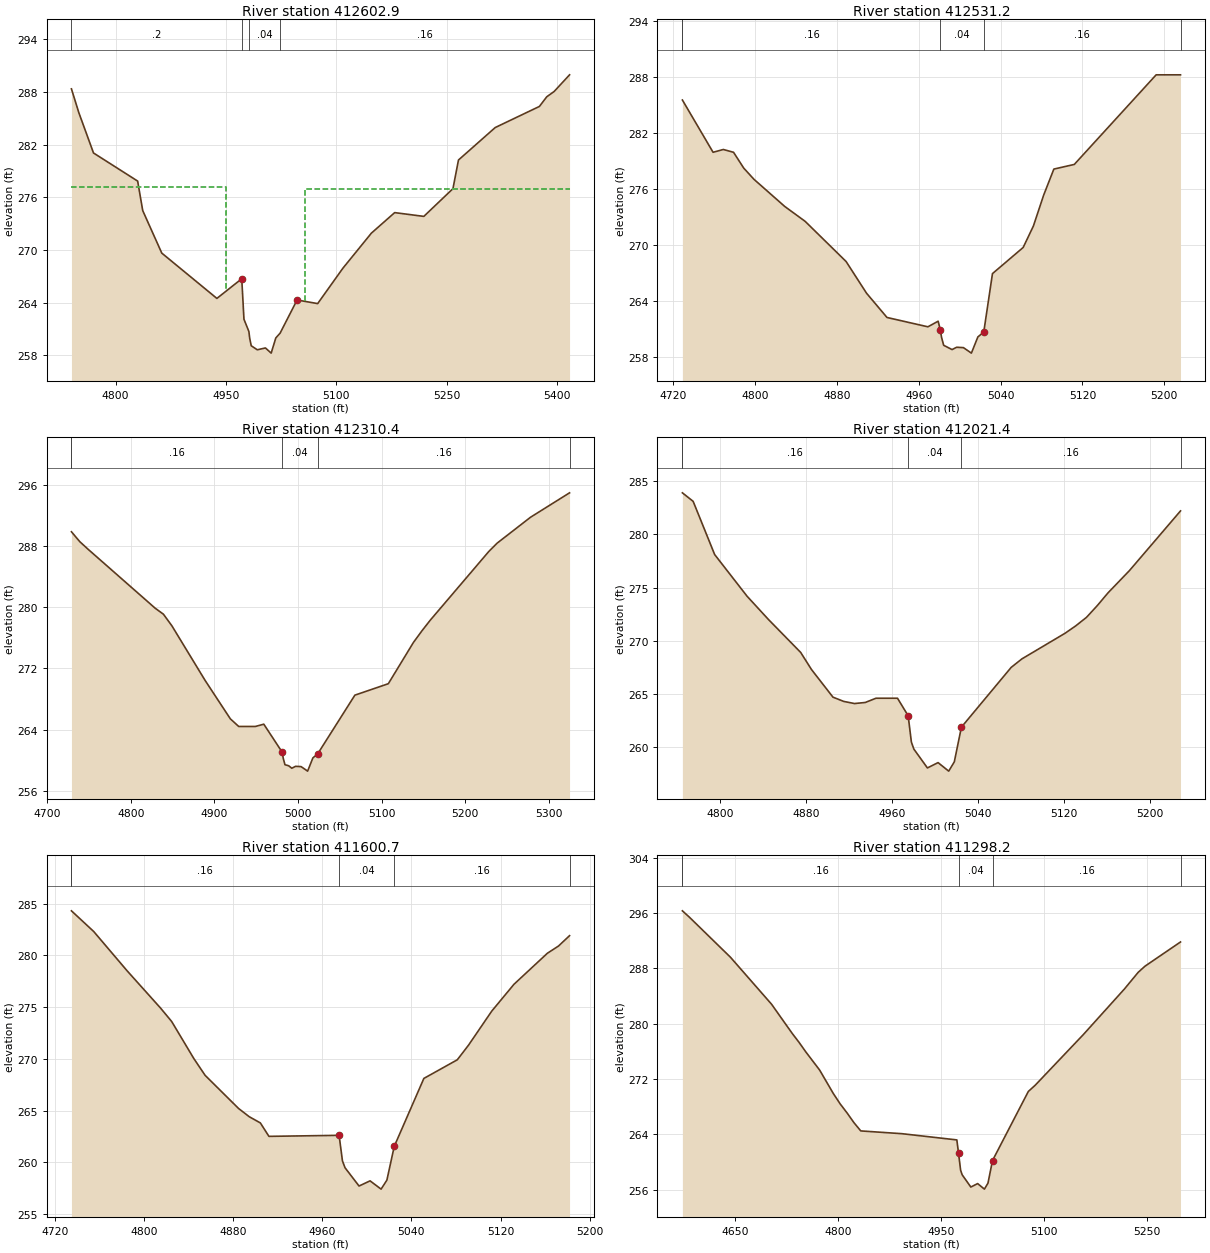
Type RM Length L Ch R = 1 ,412602.9,71.7,71.7,71.7
BEGIN DESCRIPTION:
Downstream Section of Bridge/Culvert/Weir
END DESCRIPTION:
#Sta/Elev= 30
    4740  288.35    4750  285.65    4770  281.05    4830  277.85  4836.9  274.49
  4862.8  269.65  4937.7  264.49  4971.5  266.73  4974.5  262.12  4981.2  260.72
  4982.3  259.96  4984.4   259.1  4992.6  258.64  5003.7  258.85  5011.5  258.26
  5017.8  259.99  5023.6  260.53  5046.7  264.31  5074.7   263.9    5109  267.93
  5147.8  271.93  5179.4  274.26    5219  273.83  5258.6  276.99  5266.1  280.25
  5316.1  283.95  5376.1  286.35  5386.1  287.45  5396.1  288.05  5417.1  289.95
#Mann= 4 , 1 , 0
 4740.00     0.2       0  4971.5    0.16       0  4981.2    0.04       0
  5023.6    0.16       0
#XS Ineff= 2 , 0
       0  4949.7   277.2  5057.6       0     277
Bank Sta=4971.50,5046.70
Exp/Cntr=0.5,0.3

Type RM Length L Ch R = 1 ,412531.2,220.8,220.8,220.8
BEGIN DESCRIPTION:
Cross Section Little River 97.5
END DESCRIPTION:
#Sta/Elev= 30
    4729   285.5    4759   279.9    4769   280.2    4779   279.9    4789   278.2
    4799     277    4829   274.1    4849   272.5    4889   268.2    4909   264.8
    4929   262.2    4969   261.2    4979   261.8  4981.2  260.84  4982.3  260.08
  4984.4  259.22  4992.6  258.76  4997.1  259.01  5003.7  258.97  5011.5  258.38
  5017.8  260.11  5023.6  260.65  5032.1   266.9  5062.1   269.7  5072.1     272
  5082.1   275.3  5092.1   278.1  5112.1   278.6  5192.1   288.2  5215.9   288.2
#Mann= 5 , 1 , 0
 4729.00     0.2       0    4729    0.16       0  4981.2    0.04       0
  5023.6    0.16       0  5215.9     0.2       0
Bank Sta=4981.20,5023.60
Exp/Cntr=0.3,0.1

Type RM Length L Ch R = 1 ,412310.4,289,289,289
BEGIN DESCRIPTION:
Cross Section Little River 97.9
END DESCRIPTION:
#Sta/Elev= 30
  4729.1   289.9  4739.1   288.6  4749.1   287.6  4829.1   279.9  4839.1   279.1
  4849.1   277.6  4889.1   270.4  4919.1   265.4  4929.1   264.4  4949.1   264.4
  4959.1   264.7  4981.2  261.01  4982.3  260.25  4984.4  259.39  4988.9  259.25
  4992.6  258.93  4997.1  259.18  5003.7  259.14  5011.5  258.55  5017.8  260.28
  5023.6  260.82    5068   268.5    5108     270    5138   275.4    5148   276.9
    5158   278.3    5228   287.3    5238   288.4    5278   291.8  5324.7     295
#Mann= 5 , 1 , 0
 4729.10     0.2       0  4729.1    0.16       0  4981.2    0.04       0
  5023.6    0.16       0  5324.7     0.2       0
Bank Sta=4981.20,5023.60
Exp/Cntr=0.3,0.1

Type RM Length L Ch R = 1 ,412021.4,420.7,420.7,420.7
BEGIN DESCRIPTION:
Cross Section Little River 97.0
END DESCRIPTION:
#Sta/Elev= 30
  4765.2   283.9  4775.2   283.1  4795.2   278.1  4825.2   274.2  4845.2     272
  4875.2   268.9  4885.2   267.3  4905.2   264.7  4915.2   264.3  4925.2   264.1
  4935.2   264.2  4945.2   264.6  4965.2   264.6  4975.1  262.95  4978.1  260.48
  4980.4  259.82    4993  258.05  5002.9  258.55  5012.8  257.75    5018  258.62
  5024.6  261.88  5070.9   267.5  5080.9   268.3  5120.9   270.7  5130.9   271.4
  5140.9   272.2  5150.9   273.3  5160.9   274.5  5180.9   276.6  5228.3   282.2
#Mann= 5 , 1 , 0
 4765.20     0.2       0  4765.2    0.16       0  4975.1    0.04       0
  5024.6    0.16       0  5228.3     0.2       0
Bank Sta=4975.10,5024.60
Exp/Cntr=0.3,0.1

Type RM Length L Ch R = 1 ,411600.7,302.5,302.5,302.5
BEGIN DESCRIPTION:
Cross Section Little River 96.0  CCX183
END DESCRIPTION:
#Sta/Elev= 27
  4734.8   284.3  4754.8   282.3  4784.8   278.5  4814.8   274.9  4824.8   273.6
  4844.8     270  4854.8   268.4  4884.8   265.2  4894.4   264.4  4904.4   263.8
  4912.1   262.5  4975.1   262.6  4978.1  260.13  4980.4  259.47    4993   257.7
  5002.9   258.2  5012.8   257.4    5018  258.27  5024.6  261.53  5051.2   268.1
  5081.2   269.9  5091.2   271.3  5112.1   274.6  5132.1   277.2  5162.1   280.2
  5172.1   280.9    5182   281.9
#Mann= 5 , 1 , 0
 4734.80     0.2       0  4734.8    0.16       0  4975.1    0.04       0
  5024.6    0.16       0    5182     0.2       0
Bank Sta=4975.10,5024.60
Exp/Cntr=0.3,0.1

Type RM Length L Ch R = 1 ,411298.2,404.1,404.1,404.1
BEGIN DESCRIPTION:
Cross Section Little River 95.5
END DESCRIPTION:
#Sta/Elev= 30
  4572.6   296.3  4582.6   295.4  4642.6   289.6  4702.6   282.8  4732.6   278.6
  4742.6   277.3  4752.6   275.9  4772.6   273.3  4792.6   269.9  4802.6   268.4
  4812.6   267.1  4822.6   265.7  4832.6   264.5  4892.6   264.1  4972.6   263.2
  4975.1  261.29  4978.1  258.82  4980.4  258.16    4993  256.39  5002.9  256.89
  5012.8  256.09    5018  256.96  5024.6  260.22  5076.8   270.2  5086.8   271.1
  5156.8   278.4  5216.8     285  5236.8   287.4  5246.8   288.3  5298.6   291.8
#Mann= 5 , 1 , 0
 4572.60     0.2       0  4572.6    0.16       0  4975.1    0.04       0
  5024.6    0.16       0  5298.6     0.2       0
Bank Sta=4975.10,5024.60
Exp/Cntr=0.3,0.1

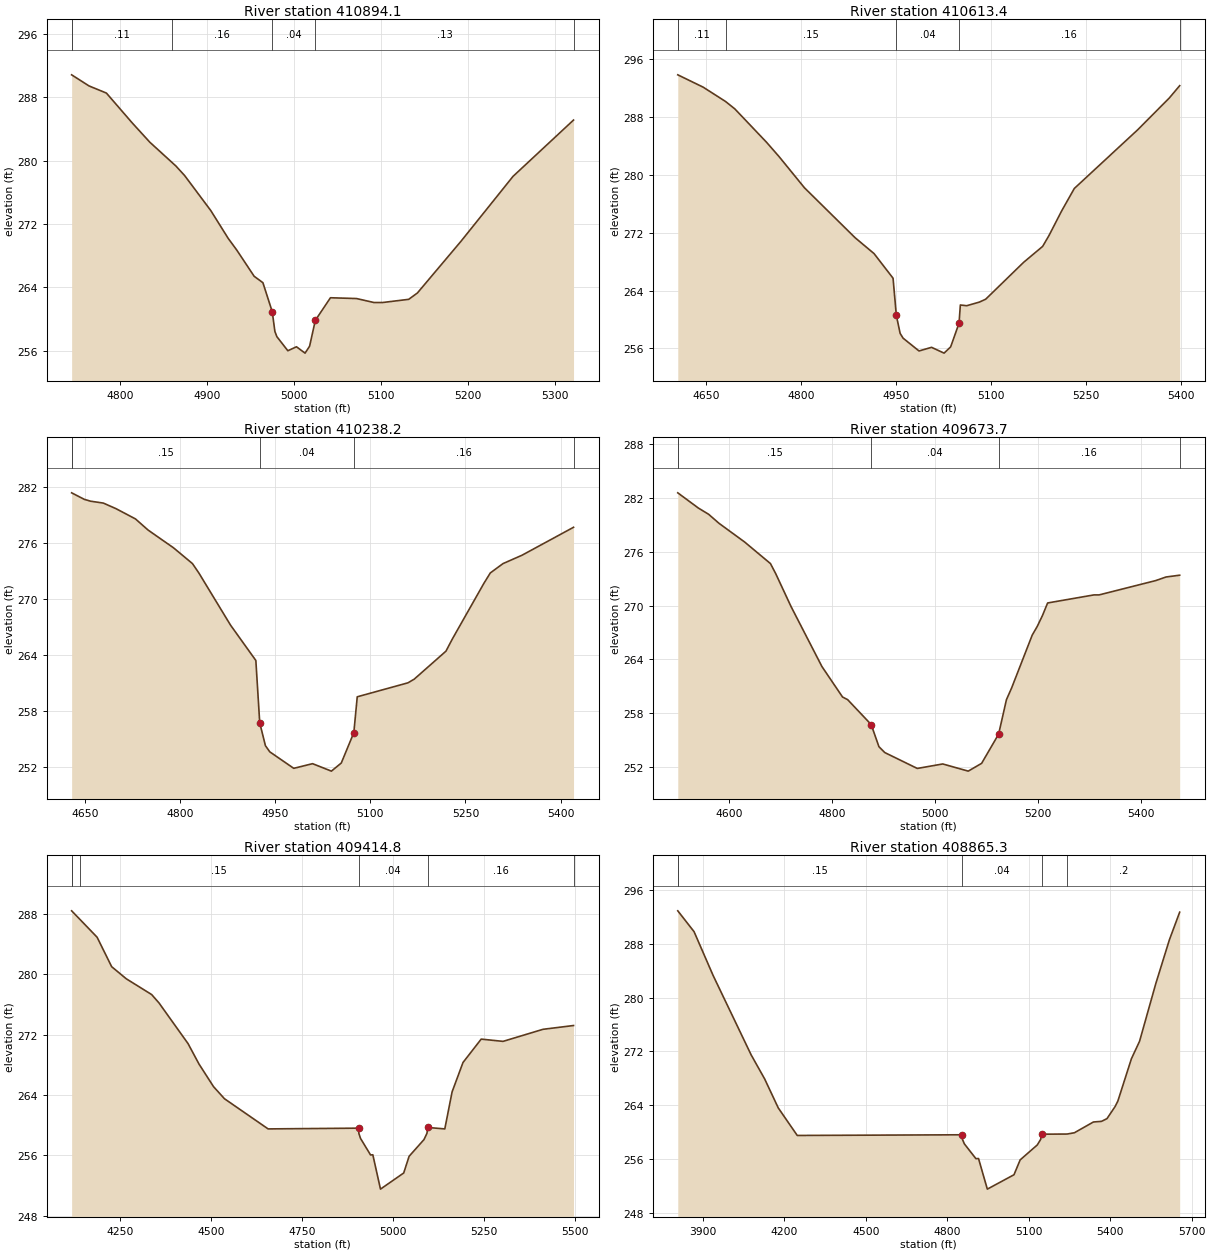
Type RM Length L Ch R = 1 ,410894.1,280.7,280.7,280.7
BEGIN DESCRIPTION:
Cross Section Little River 95.0
END DESCRIPTION:
#Sta/Elev= 30
  4744.3   290.8  4764.3   289.4  4784.3   288.5  4814.3   284.7  4834.3   282.3
  4859.2  279.81  4864.3   279.3  4874.3   278.1  4904.3   273.7  4924.3   270.2
  4934.3   268.7  4954.3   265.4  4964.3   264.6  4975.1  260.92  4978.1  258.45
  4980.4  257.79    4993  256.02  5002.9  256.52  5012.8  255.72    5018  256.59
  5024.6  259.85    5042   262.7    5072   262.6    5092   262.1    5102   262.1
    5132   262.5    5142   263.3    5192   269.8    5252     278  5321.6   285.1
#Mann= 6 , 1 , 0
 4744.30     0.2       0  4744.3    0.11       0  4859.2    0.16       0
  4975.1    0.04       0  5024.6    0.13       0  5321.6     0.2       0
Bank Sta=4975.10,5024.60
Exp/Cntr=0.3,0.1

Type RM Length L Ch R = 1 ,410613.4,375.2,375.2,375.2
BEGIN DESCRIPTION:
Cross Section Little River 94.5
END DESCRIPTION:
#Sta/Elev= 30
    4605   293.8    4645   292.1  4680.4  290.12    4695   289.1    4745   284.5
    4765   282.5    4805   278.2    4885   271.3    4915   269.1    4945   265.7
  4950.2  260.55  4956.2  258.08  4960.8  257.42    4986  255.65  5005.8  256.15
  5025.6  255.35    5036  256.22  5049.2  259.48  5051.3     262  5061.3   261.9
  5081.3   262.4  5091.3   262.8  5151.3   267.9  5181.3   270.1  5191.3   271.6
  5211.3     275  5231.3   278.1  5331.3   286.2  5381.3   290.6  5397.7   292.3
#Mann= 6 , 1 , 0
 4605.00     0.2       0    4605    0.11       0  4680.4    0.15       0
  4950.2    0.04       0  5049.2    0.16       0  5397.7     0.2       0
Bank Sta=4950.20,5049.20
Exp/Cntr=0.3,0.1

Type RM Length L Ch R = 1 ,410238.2,564.5,564.5,564.5
BEGIN DESCRIPTION:
Cross Section Little River 94.0
END DESCRIPTION:
#Sta/Elev= 30
  4628.5   281.4  4648.5   280.7  4658.5   280.5  4678.5   280.3  4698.5   279.7
  4729.2   278.6  4749.2   277.4  4789.2   275.5  4819.2   273.8  4829.2   272.8
  4879.2   267.2  4919.2   263.4  4925.3  256.72  4934.3  254.25  4941.2  253.59
    4979  251.82  5008.7  252.32  5038.4  251.52    5054  252.39  5073.8  255.65
  5079.2   259.5  5159.2     261  5169.2   261.4  5219.2   264.4  5229.2   265.7
  5279.2   271.7  5289.2   272.8  5309.2   273.8  5339.2   274.7  5420.5   277.7
#Mann= 5 , 1 , 0
 4628.50     0.2       0  4628.5    0.15       0  4925.3    0.04       0
  5073.8    0.16       0  5420.5     0.2       0
Bank Sta=4925.30,5073.80
Exp/Cntr=0.3,0.1

Type RM Length L Ch R = 1 ,409673.7,258.9,258.9,258.9
BEGIN DESCRIPTION:
Cross Section Little River 93.0
END DESCRIPTION:
#Sta/Elev= 30
  4499.8   282.6  4539.8   280.9  4559.8   280.2  4579.8   279.2  4629.8   277.1
  4679.8   274.7  4689.8   273.6  4719.8   269.9  4779.8   263.2  4819.8   259.8
  4829.8   259.5  4875.5  256.72  4890.5  254.25    4902  253.59    4965  251.82
  5014.5  252.32    5064  251.52    5090  252.39    5123  255.65  5138.2   259.5
  5148.2   260.8  5188.2   266.7  5198.2   267.7  5208.2   268.9  5218.2   270.3
  5308.2   271.2  5318.2   271.2  5428.2   272.8  5448.2   273.2  5474.7   273.4
#Mann= 5 , 1 , 0
 4499.80     0.2       0  4499.8    0.15       0  4875.5    0.04       0
    5123    0.16       0  5474.7     0.2       0
Bank Sta=4875.50,5123.00
Exp/Cntr=0.3,0.1

Type RM Length L Ch R = 1 ,409414.8,549.5,549.5,549.5
BEGIN DESCRIPTION:
Cross Section Little River 92.5
END DESCRIPTION:
#Sta/Elev= 30
  4117.1   288.4  4139.2   287.3  4187.1   284.9  4227.1     281  4267.1   279.4
  4337.1   277.3  4357.1   276.2  4437.1   270.8  4467.1   268.1  4507.1   265.1
  4537.1   263.5  4657.1   259.5 4906.01   259.6 4906.53   258.9 4911.08  258.24
 4938.64  256.05 4944.88  256.07 4965.94  251.52 5029.77  253.66 5044.59  255.87
 5085.54  258.09  5093.6  258.91 5096.07  259.69  5142.7   259.5  5162.7   264.4
  5192.7   268.3  5242.7   271.4  5302.7   271.1  5412.7   272.7  5496.5   273.2
#Mann= 6 , 1 , 0
 4117.10     0.2       0  4117.1    0.11       0  4139.2    0.15       0
 4906.01    0.04       0 5096.07    0.16       0  5496.5     0.2       0
Bank Sta=4906.01,5096.07
Exp/Cntr=0.3,0.1

Type RM Length L Ch R = 1 ,408865.3,292.6,292.6,292.6
BEGIN DESCRIPTION:
Cross Section Little River 92.0
END DESCRIPTION:
#Sta/Elev= 30
  3807.6   292.9  3867.6   289.8  3937.6   283.3  4077.6   271.5  4127.6   267.9
  4177.6   263.6  4247.6   259.5  4855.4   259.6  4856.2   258.9  4863.2  258.24
  4905.6  256.05  4915.2  256.07  4947.6  251.52  5045.8  253.66  5068.6  255.87
  5131.6  258.09    5144  258.91  5147.8  259.69  5241.1  259.71  5268.2   259.9
  5338.2   261.5  5368.2   261.6  5388.2     262  5418.2   263.8  5428.2   264.6
  5478.2   270.9  5508.2   273.5  5568.2   282.1  5618.2   288.6    5656   292.7
#Mann= 5 , 1 , 0
 3807.60     0.2       0  3807.6    0.15       0  4855.4    0.04       0
  5147.8    0.15       0  5241.1     0.2       0
Bank Sta=4855.40,5147.80
Exp/Cntr=0.3,0.1

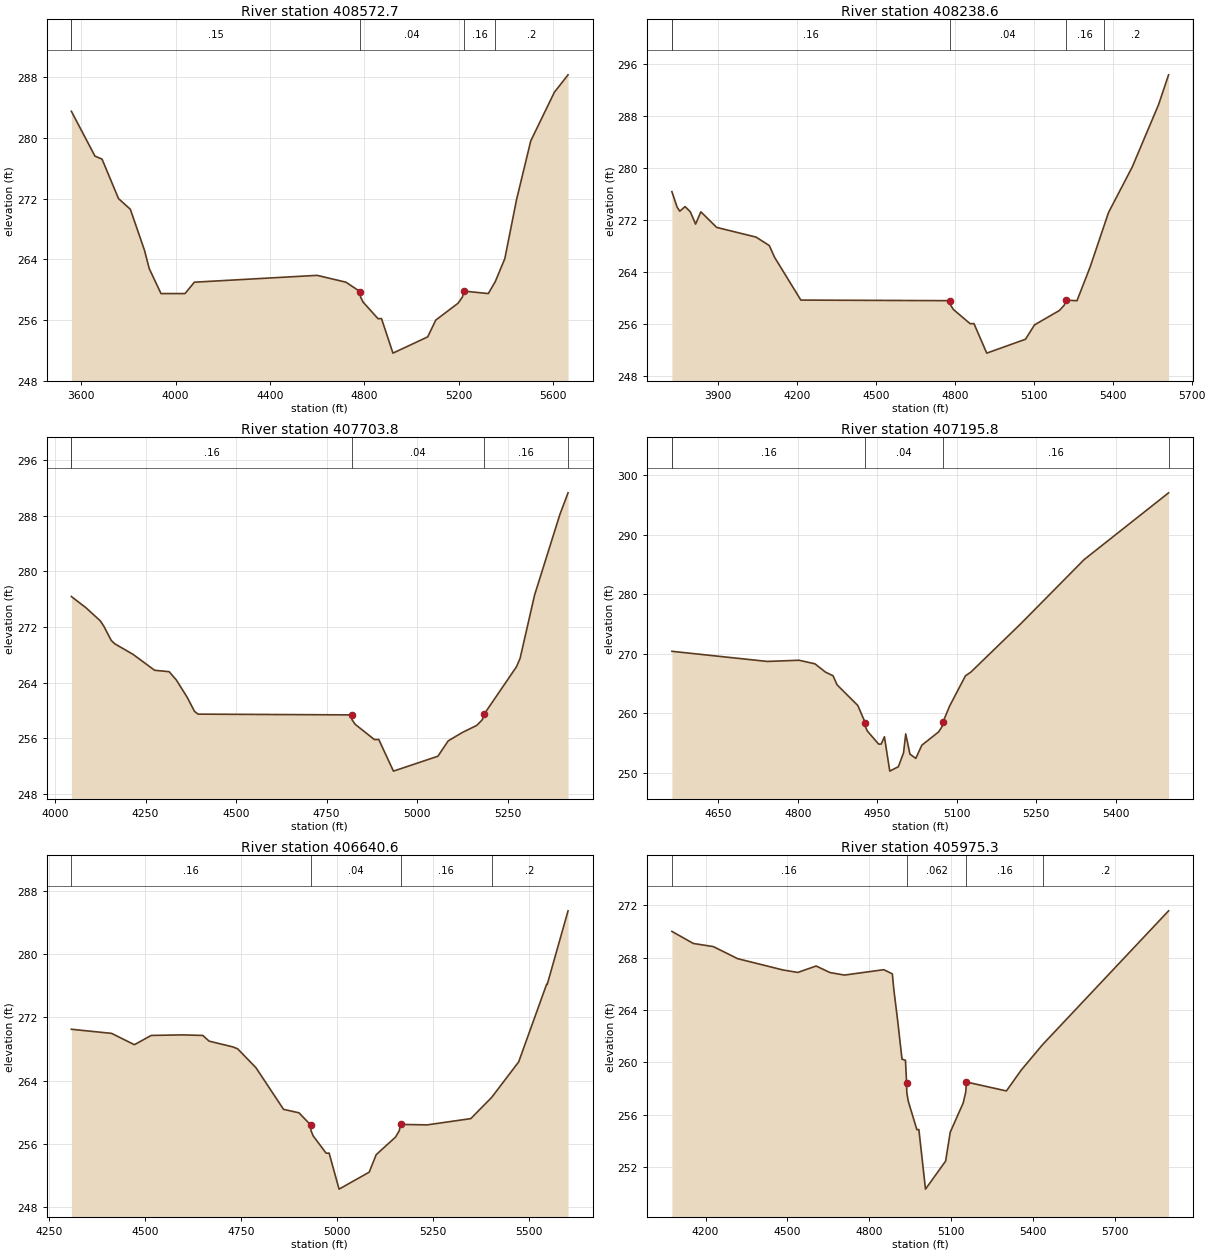
Type RM Length L Ch R = 1 ,408572.7,334.1,334.1,334.1
BEGIN DESCRIPTION:
Cross Section Little River 91.0
END DESCRIPTION:
#Sta/Elev= 30
  3558.1   283.5  3658.1   277.6  3688.1   277.2  3758.1     272  3808.1   270.6
  3868.1   265.2  3888.1   262.8  3938.1   259.5  4039.7   259.5  4079.7     261
  4599.7   261.9  4721.9     261  4783.1  259.74  4784.3  259.04  4794.8  258.38
  4858.4  256.19  4872.8  256.21  4921.4  251.66  5068.7   253.8  5102.9  256.01
  5197.4  258.23    5216  259.05  5221.7  259.83  5325.6   259.5  5355.4  261.09
  5395.6   264.1  5445.6   271.9  5505.6   279.6  5605.6     286  5663.7   288.3
#Mann= 5 , 1 , 0
 3558.10     0.2       0  3558.1    0.15       0  4783.1    0.04       0
  5221.7    0.16       0  5355.4     0.2       0
Bank Sta=4783.10,5221.70
Exp/Cntr=0.3,0.1

Type RM Length L Ch R = 1 ,408238.6,534.8,534.8,534.8
BEGIN DESCRIPTION:
Cross Section Little River 90.9
END DESCRIPTION:
#Sta/Elev= 30
  3725.1   276.4  3745.1     274  3755.1   273.4  3775.1   274.1  3795.1   273.3
  3815.1   271.4  3835.1   273.3  3895.1   270.9  4045.1   269.4  4095.1   268.1
  4115.1   266.3  4215.1   259.7  4783.1  259.61  4784.3  258.91  4794.8  258.25
  4858.4  256.06  4872.8  256.08  4921.4  251.53  5068.7  253.67  5102.9  255.88
  5197.4   258.1    5216  258.92  5221.7   259.7  5264.2   259.6  5314.2   264.8
  5365.8  270.99  5384.2   273.2  5474.2   280.2  5574.2   289.8  5612.3   294.4
#Mann= 5 , 1 , 0
 3725.10     0.2       0  3725.1    0.16       0  4783.1    0.04       0
  5221.7    0.16       0  5365.8     0.2       0
Bank Sta=4783.10,5221.70
Exp/Cntr=0.3,0.1

Type RM Length L Ch R = 1 ,407703.8,508,508,508
BEGIN DESCRIPTION:
Cross Section Little River 90.7
END DESCRIPTION:
#Sta/Elev= 30
  4045.1   276.4  4085.1   274.8  4125.1   272.9  4135.1   272.1  4155.1   270.1
  4165.1   269.6  4215.1   268.1  4275.1   265.8  4315.1   265.6  4335.1   264.4
  4365.1   261.9  4385.1   259.9  4395.1   259.5 4819.25  259.39 4820.25  258.69
    4829  258.03    4882  255.84    4894  255.86  4934.5  251.31 5057.25  253.45
 5085.75  255.66 5124.75  256.86  5164.5  257.88    5180   258.7 5184.75  259.48
  5274.2   266.3  5284.2   267.5  5324.2   276.6  5394.2   288.2  5416.7   291.3
#Mann= 5 , 1 , 0
 4045.10     0.2       0  4045.1    0.16       0 4819.25    0.04       0
 5184.75    0.16       0  5416.7     0.2       0
Bank Sta=4819.25,5184.75
Exp/Cntr=0.3,0.1

Type RM Length L Ch R = 1 ,407195.8,555.2,555.2,555.2
BEGIN DESCRIPTION:
Cross Section Little River 90.5 (CCX 182)
END DESCRIPTION:
#Sta/Elev= 30
  4562.6   270.4  4742.6   268.7  4802.6   268.9  4832.6   268.3  4852.6   266.9
  4866.7   266.3  4874.4  264.77  4913.5   261.3  4927.7  258.37  4928.1  257.67
  4931.6  257.01  4952.8  254.82  4957.6  254.84  4963.7  256.06  4973.8  250.29
    4990  251.03  4999.8  253.37  5003.9  256.54  5011.9  253.14  5022.9  252.43
  5034.3  254.64  5065.8  256.86    5072  257.68  5073.9  258.46  5086.5  261.17
  5116.7   266.3  5126.7   266.9  5220.7     275  5340.7   285.8    5500     297
#Mann= 5 , 1 , 0
 4562.60     0.2       0  4562.6    0.16       0  4927.7    0.04       0
  5073.9    0.16       0    5500     0.2       0
Bank Sta=4927.70,5073.90
Exp/Cntr=0.3,0.1

Type RM Length L Ch R = 1 ,406640.6,665.3,665.3,665.3
BEGIN DESCRIPTION:
Cross Section Little River 90.0
END DESCRIPTION:
#Sta/Elev= 30
  4308.3  270.49  4413.2  269.97  4472.6  268.54  4516.3  269.71  4597.3  269.78
  4650.8  269.71  4667.4  268.99  4729.5  268.26  4741.8  268.02  4789.6  265.63
  4861.4  260.38  4901.8  259.94 4932.32  258.39 4932.96  257.69 4938.56  257.03
 4972.48  254.84 4980.16  254.86 5006.08  250.31 5084.64  252.45 5102.88  254.66
 5153.28  256.88  5163.2   257.7 5166.24  258.48  5235.7  258.42  5349.4  259.21
  5403.9  261.89  5474.3  266.37    5547  276.15  5548.7  276.15    5603  285.44
#Mann= 4 , 1 , 0
 4308.30    0.16       0 4932.32    0.04       0 5166.24    0.16       0
  5403.9     0.2       0
Bank Sta=4932.32,5166.24
Exp/Cntr=0.3,0.1

Type RM Length L Ch R = 1 ,405975.3,588.3,588.3,588.3
BEGIN DESCRIPTION:
Cross Section Little River 89.0
END DESCRIPTION:
#Sta/Elev= 30
  4076.9     270  4155.4  269.08  4228.7  268.84  4317.8  267.92  4483.3  267.06
    4538  266.87  4605.1  267.36  4655.9  266.86  4708.8  266.67  4853.1  267.08
  4884.3  266.76  4889.6  265.59  4904.1  263.13  4919.7  260.25  4932.3  260.17
 4936.55  258.42 4937.15  257.72  4942.4  257.06  4974.2  254.87  4981.4  254.89
  5005.7  250.34 5079.35  252.48 5096.45  254.69  5143.7  256.91    5153  257.73
 5155.85  258.51    5302  257.83  5356.3  259.42  5434.4  261.36    5896  271.57
#Mann= 4 , 1 , 0
 4076.90    0.16       0 4936.55   0.062       0 5155.85    0.16       0
  5434.4     0.2       0
Bank Sta=4936.55,5155.85
Exp/Cntr=0.3,0.1

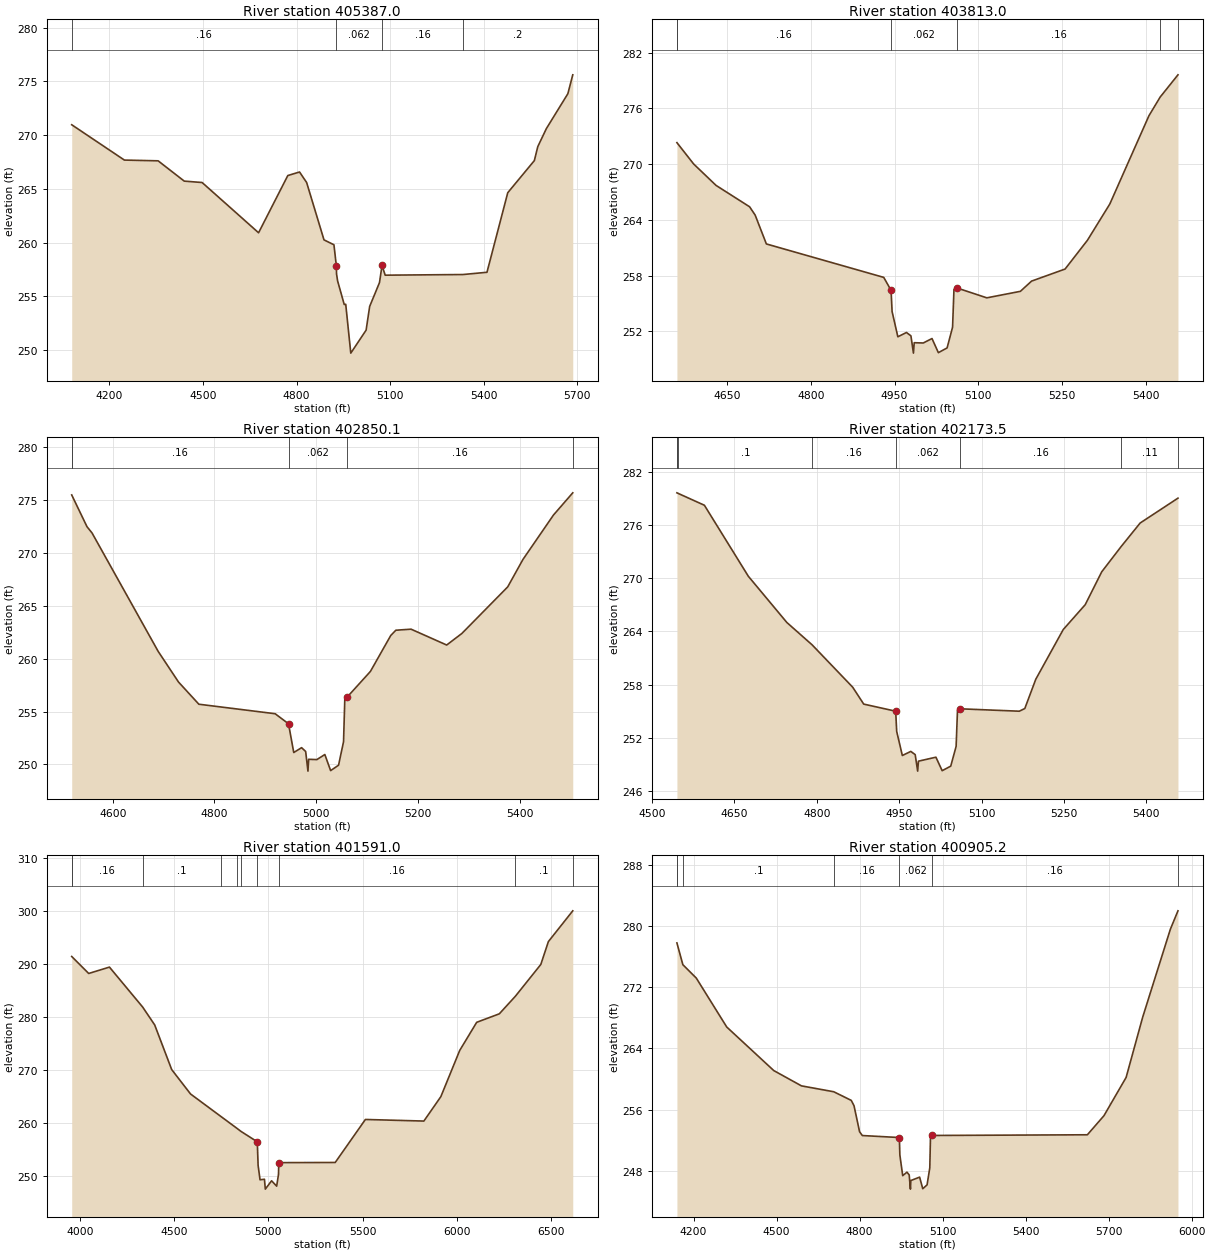
Type RM Length L Ch R = 1 ,405387.0,1574,1574,1574
BEGIN DESCRIPTION:
Cross Section Little River 88.0
END DESCRIPTION:
#Sta/Elev= 30
  4079.5  270.97  4248.3  267.68  4356.4  267.61  4440.1  265.72  4497.4  265.59
  4678.3  260.91    4772  266.24  4809.6  266.57  4832.3  265.59  4887.9  260.25
  4919.8  259.79  4927.7  257.78  4928.1  257.08  4931.6  256.42  4952.8  254.23
  4957.6  254.25  4973.8   249.7  5022.9  251.84  5034.3  254.05  5065.8  256.27
  5073.9  257.87    5084  256.96  5333.2  257.02  5410.2  257.23  5476.8  264.64
    5562  267.63    5573  268.93  5600.5  270.61  5669.4  273.86  5685.1  275.62
#Mann= 4 , 1 , 0
 4079.50    0.16       0  4927.7   0.062       0  5073.9    0.16       0
  5333.2     0.2       0
Bank Sta=4927.70,5073.90
Exp/Cntr=0.3,0.1

Type RM Length L Ch R = 1 ,403813.0,962.9,962.9,962.9
BEGIN DESCRIPTION:
Cross Section Little River 87.0
END DESCRIPTION:
#Sta/Elev= 30
  4560.7   272.3  4590.7     270  4630.7   267.7  4690.7   265.4  4700.7   264.5
  4720.7   261.4  4930.7   257.8  4943.8   256.4  4945.6  254.13  4955.9  251.41
  4971.3  251.87  4979.3  251.51  4983.8  249.65  4985.2  250.77  5001.3  250.74
    5017  251.22  5028.4   249.7    5044  250.21  5053.8  252.44  5056.3  256.51
  5061.2  256.67  5115.1   255.6  5175.1   256.3  5195.1   257.4  5255.1   258.7
  5295.1   261.8  5335.1   265.7  5405.1   275.2  5425.2  277.21    5457   279.6
#Mann= 6 , 1 , 0
 4560.70     0.2       0  4560.7    0.16       0  4943.8   0.062       0
  5061.2    0.16       0  5425.2    0.11       0    5457     0.2       0
Bank Sta=4943.80,5061.20
Exp/Cntr=0.3,0.1

Type RM Length L Ch R = 1 ,402850.1,676.6,676.6,676.6
BEGIN DESCRIPTION:
Cross Section Little River 86.0
END DESCRIPTION:
#Sta/Elev= 30
  4519.3   275.5  4549.3   272.5  4559.3   271.9  4689.3   260.7  4729.3   257.8
  4769.3   255.7  4919.3   254.8  4945.6  253.85  4955.9  251.13  4971.3  251.59
  4979.3  251.23  4983.8  249.37  4985.2  250.49  5001.3  250.46    5017  250.94
  5028.4  249.42    5044  249.93  5053.8  252.16  5056.3  256.23  5061.2  256.39
  5106.6   258.8  5146.6   262.2  5156.6   262.7  5186.6   262.8  5256.6   261.3
  5286.6   262.4  5376.6   266.8  5406.6   269.4  5466.6   273.6  5504.5   275.7
#Mann= 5 , 1 , 0
 4519.30     0.2       0  4519.3    0.16       0  4945.6   0.062       0
  5061.2    0.16       0  5504.5     0.2       0
Bank Sta=4945.60,5061.20
Exp/Cntr=0.3,0.1

Type RM Length L Ch R = 1 ,402173.5,582.5,582.5,582.5
BEGIN DESCRIPTION:
Cross Section Little River 85.0
END DESCRIPTION:
#Sta/Elev= 30
  4545.6   279.6  4548.4  279.52  4595.6   278.2  4675.6   270.2  4745.6     265
  4791.6  262.48  4865.6   257.7  4885.6   255.8  4943.8     255  4945.6  252.73
  4955.9  250.01  4971.3  250.47  4979.3  250.11  4983.8  248.25  4985.2  249.37
    5017  249.82  5028.4   248.3    5044  248.81  5053.8  251.04  5056.3  255.11
  5061.2  255.27  5168.8     255  5178.8   255.3  5198.8   258.6  5248.8   264.2
  5288.8     267  5318.8   270.7  5354.2  273.55  5388.8   276.2  5457.6     279
#Mann= 8 , 1 , 0
 4545.60     0.2       0  4545.6    0.16       0  4548.4     0.1       0
  4791.6    0.16       0  4943.8   0.062       0  5061.2    0.16       0
  5354.2    0.11       0  5457.6     0.2       0
Bank Sta=4943.80,5061.20
Exp/Cntr=0.3,0.1

Type RM Length L Ch R = 1 ,401591.0,685.8,685.8,685.8
BEGIN DESCRIPTION:
Cross Section Little River 84.0
END DESCRIPTION:
#Sta/Elev= 30
  3957.5   291.4  4047.5   288.2  4157.5   289.4  4333.5  281.88  4397.5   278.5
  4487.5   270.1  4587.5   265.5  4748.6  261.26  4831.6  259.08  4854.2  258.47
  4941.4  256.49  4945.6  252.06  4955.9  249.34  4979.3  249.44  4983.8  247.58
    5017  249.15    5044  248.14  5053.8  250.37  5055.1  252.57  5354.4   252.6
  5514.4   260.7  5824.4   260.4  5914.4     265  6014.4   273.7  6104.4     279
  6224.4   280.6  6309.5  283.91  6444.4   289.9  6484.4   294.2  6613.7     300
#Mann= 10 , 1 , 0
 3957.50     0.2       0  3957.5    0.16       0  4333.5     0.1       0
  4748.6    0.16       0  4831.6     0.1       0  4854.2    0.16       0
  4941.4   0.062       0  5055.1    0.16       0  6309.5     0.1       0
  6613.7     0.2       0
Bank Sta=4941.40,5055.10
Exp/Cntr=0.3,0.1

Type RM Length L Ch R = 1 ,400905.2,667.9,667.9,667.9
BEGIN DESCRIPTION:
Cross Section Little River 83.0
END DESCRIPTION:
#Sta/Elev= 30
    4140   277.8  4161.5  274.95    4210   273.2    4320   266.8    4490   261.1
    4590   259.1  4706.7  258.33    4770   257.2    4780   256.5    4800   253.1
    4810   252.6  4943.8  252.34  4945.6  250.07  4955.9  247.35  4971.3  247.81
  4979.3  247.45  4983.8  245.59  4985.2  246.71    5017  247.16  5028.4  245.64
    5044  246.15  5053.8  248.38  5056.3  252.45  5061.2  252.61  5623.2   252.7
  5683.2   255.2  5763.2   260.2  5823.2   268.1  5923.2   279.6  5950.6     282
#Mann= 7 , 1 , 0
 4140.00     0.2       0    4140    0.16       0  4161.5     0.1       0
  4706.7    0.16       0  4943.8   0.062       0  5061.2    0.16       0
  5950.6     0.2       0
Bank Sta=4943.80,5061.20
Exp/Cntr=0.3,0.1

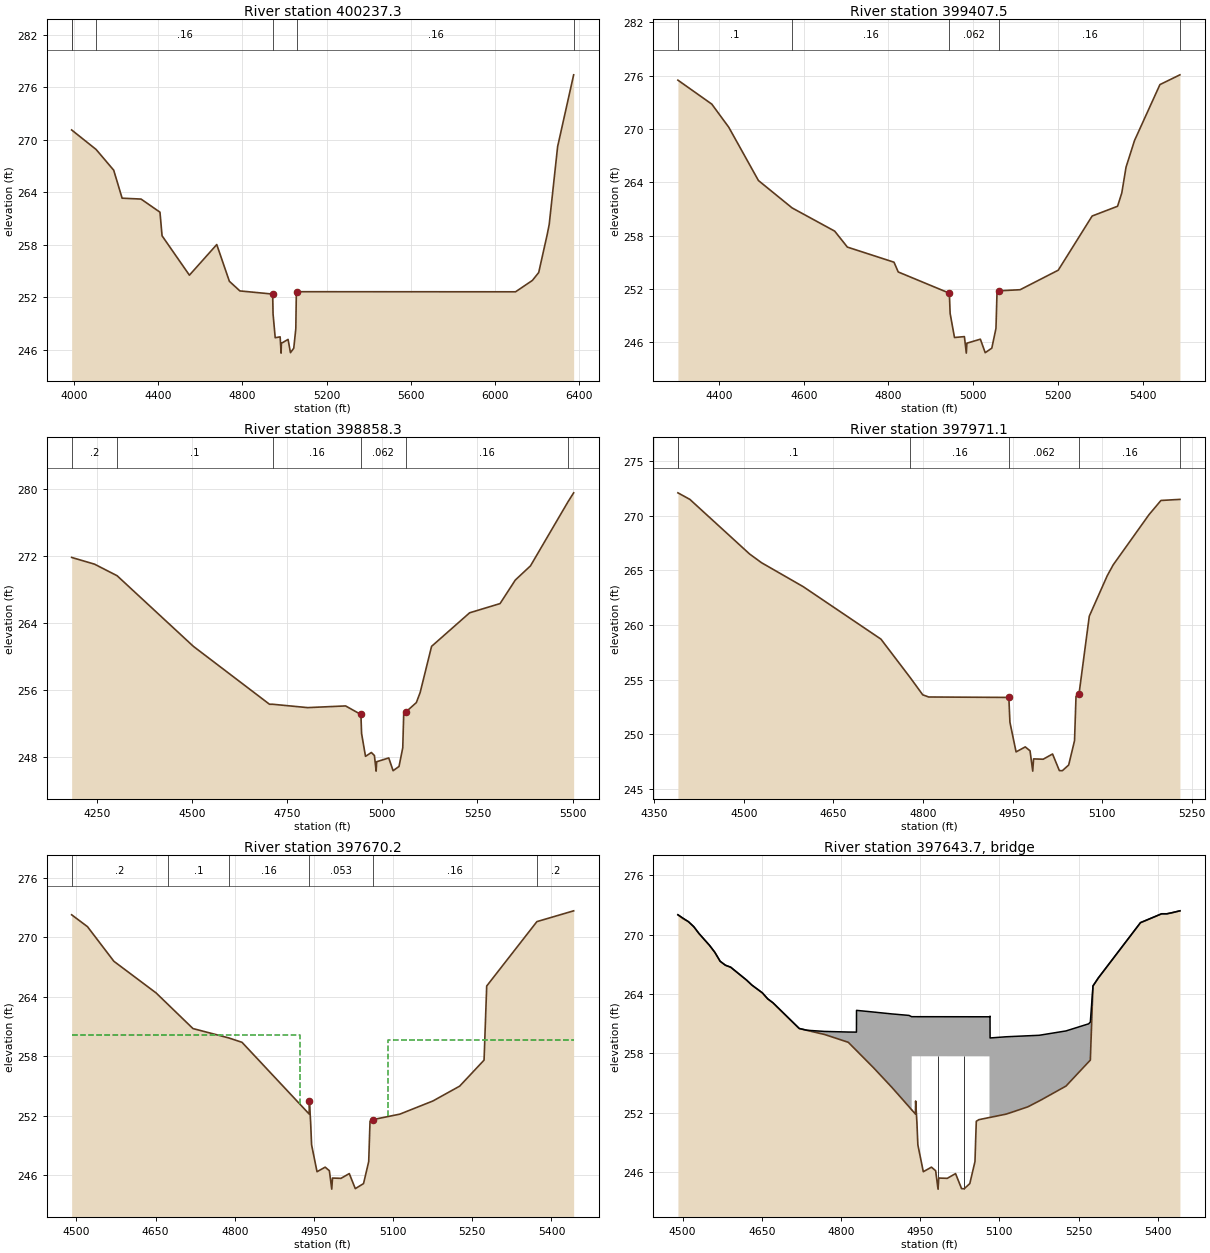
Type RM Length L Ch R = 1 ,400237.3,829.8,829.8,829.8
BEGIN DESCRIPTION:
Cross Section Little River 82.0
END DESCRIPTION:
#Sta/Elev= 30
  3987.9   271.1  4104.2  268.87  4187.9   266.5  4227.9   263.3  4317.9   263.2
  4407.9   261.7  4417.9     259  4547.9   254.5  4677.9     258  4737.9   253.8
  4787.9   252.7  4943.8  252.34  4945.6  250.07  4955.9  247.35  4979.3  247.45
  4983.8  245.59  4985.2  246.71    5017  247.16  5028.4  245.64    5044  246.15
  5053.8  248.38  5056.3  252.45  5061.2  252.61  6098.7   252.6  6178.7   253.9
  6208.7   254.8  6248.7   259.1  6258.7   260.3  6298.7   269.2  6374.9   277.4
#Mann= 6 , 1 , 0
 3987.90     0.2       0  3987.9     0.1       0  4104.2    0.16       0
  4943.8   0.062       0  5061.2    0.16       0  6374.9     0.2       0
Bank Sta=4943.80,5061.20
Exp/Cntr=0.3,0.1

Type RM Length L Ch R = 1 ,399407.5,549.2,549.2,549.2
BEGIN DESCRIPTION:
Cross Section Little River 81.0
END DESCRIPTION:
#Sta/Elev= 30
  4303.1   275.5  4383.1   272.8  4423.1   270.2  4493.1   264.2  4572.7  261.11
  4673.1   258.5  4703.1   256.7  4813.1     255  4823.1   253.9  4943.8  251.51
  4945.6  249.24  4955.9  246.52  4979.3  246.62  4983.8  244.76  4985.2  245.88
    5017  246.33  5028.4  244.81    5044  245.32  5053.8  247.55  5056.3  251.62
  5061.2  251.78  5110.8   251.9  5200.8   254.1  5280.8   260.2  5340.8   261.3
  5350.8   262.8  5360.8   265.7  5380.8   268.7  5440.8     275    5488   276.1
#Mann= 6 , 1 , 0
 4303.10     0.2       0  4303.1     0.1       0  4572.7    0.16       0
  4943.8   0.062       0  5061.2    0.16       0    5488     0.2       0
Bank Sta=4943.80,5061.20
Exp/Cntr=0.3,0.1

Type RM Length L Ch R = 1 ,398858.3,887.2,887.2,887.2
BEGIN DESCRIPTION:
Cross Section Little River 80.0
END DESCRIPTION:
#Sta/Elev= 30
  4183.6   271.8  4243.6     271  4303.1  269.62  4503.6   261.2  4703.6   254.3
    4712   254.3  4803.6   253.9  4903.6   254.1  4943.8  253.08  4945.6  250.81
  4955.9  248.09  4971.3  248.55  4979.3  248.19  4983.8  246.33  4985.2  247.45
    5017   247.9  5028.4  246.38    5044  246.89  5053.8  249.12  5056.3  253.19
  5061.2  253.35  5089.5   254.5  5099.5   255.7  5129.5   261.2  5229.5   265.2
  5309.5   266.3  5349.5   269.1  5389.5   270.8    5488  278.43  5502.9   279.5
#Mann= 6 , 1 , 0
 4183.60     0.2       0  4303.1     0.1       0    4712    0.16       0
  4943.8   0.062       0  5061.2    0.16       0    5488     0.2       0
Bank Sta=4943.80,5061.20
Exp/Cntr=0.3,0.1

Type RM Length L Ch R = 1 ,397971.1,300.9,300.9,300.9
BEGIN DESCRIPTION:
Cross Section Little River 79.0
END DESCRIPTION:
#Sta/Elev= 30
  4389.6   272.1  4409.6   271.5  4509.6   266.5  4529.6   265.7  4599.6   263.5
  4729.6   258.7  4778.7  255.17  4799.6   253.6  4809.6   253.4  4943.8  253.36
  4945.6  251.09  4955.9  248.37  4971.3  248.83  4979.3  248.47  4983.8  246.61
  4985.2  247.73  5001.3   247.7    5017  248.18  5028.4  246.66  5033.4  246.65
    5044  247.17  5053.8   249.4  5056.3  253.47  5061.2  253.63  5078.5   260.8
  5108.5   264.5  5118.5   265.5  5178.5   270.1  5198.5   271.4  5230.3   271.5
#Mann= 6 , 1 , 0
 4389.60     0.2       0  4389.6     0.1       0  4778.7    0.16       0
  4943.8   0.062       0  5061.2    0.16       0  5230.3     0.2       0
Bank Sta=4943.80,5061.20
Exp/Cntr=0.5,0.3

Type RM Length L Ch R = 1 ,397670.2,53,53,53
BEGIN DESCRIPTION:
Upstream Section of Bridge/Culvert/Weir
END DESCRIPTION:
#Sta/Elev= 30
  4491.1  272.29  4521.1  271.09  4571.1  267.59  4651.1  264.39  4720.9  260.79
  4788.9  259.84  4813.8   259.4    4941  252.15  4941.4  253.47  4943.8  251.31
  4945.6  249.04  4955.9  246.32  4971.3  246.78  4979.3  246.42  4983.8  244.56
  4985.2  245.68  5001.3  245.65    5017  246.13  5028.4  244.61    5044  245.12
  5053.8  247.35  5056.3  251.42  5061.2  251.58  5112.8  252.14  5175.4  253.47
  5226.1  254.97  5272.3   257.6  5277.3  265.09  5372.4   271.6    5442  272.69
#Mann= 6 , 1 , 0
 4491.10     0.2       0  4674.2     0.1       0  4788.9    0.16       0
  4941.4   0.053       0  5061.2    0.16       0  5372.4     0.2       0
#XS Ineff= 2 , 0
       0  4923.8   260.1  5091.1       0   259.6
Bank Sta=4941.40,5061.20
Exp/Cntr=0.5,0.3

Type RM Length L Ch R = 3 ,397643.7,,,
BEGIN DESCRIPTION:
FOWLER ROAD
Structure ID: WK_LITR10
END DESCRIPTION:
Bridge Culvert--1,0,-1,-1, 0
Deck Dist Width WeirC Skew NumUp NumDn MinLoCord MaxHiCord MaxSubmerge Is_Ogee
10,33,2.6,, 42, 42,,,0.95,0,1,1,,
  4491.1  4511.1  4521.1  4531.1  4551.1  4561.1  4571.1  4581.1  4591.1  4621.1
  4631.1  4651.1  4661.1  4671.1  4720.9  4735.5  4768.8  4813.8 4829.29  4829.4
  4861.6  4896.3  4928.8  4933.8 4933.91    4934 5081.19  5081.3  5082.3 5082.41
  5112.8  5154.1  5175.4  5226.1  5269.1  5272.3  5277.3  5287.3  5367.3  5407.3
  5417.3    5442
     272   271.3   270.8   270.1   268.9   268.2   267.3   266.9   266.7   265.4
   264.9  264.11  263.51  263.11  260.51  260.33  260.21  260.15  260.14  262.34
  262.17  261.98  261.83   261.7   261.7   261.7  261.69  261.69  261.75  259.55
  259.67  259.77  259.82  260.26  260.98  261.16  264.81  265.61  271.21   272.1
   272.1   272.4
     272   271.3   270.8   270.1   268.9   268.2   267.3   266.9   266.7   265.4
   264.9   264.1   263.5   263.1   260.5  260.32   259.9  259.11  258.28  258.27
  256.54  254.56   252.6  252.29  252.29   257.7  257.69  251.51  251.52  251.52
  251.85  252.59  253.18  254.68  257.13  257.31   264.8   265.6   271.2   272.1
   272.1   272.4
  4491.1  4511.1  4521.1  4531.1  4551.1  4561.1  4571.1  4581.1  4591.1  4621.1
  4631.1  4651.1  4661.1  4671.1  4720.9  4735.5  4768.8  4813.8 4829.29  4829.4
  4861.6  4896.3  4928.8  4933.8 4933.91    4934 5081.19  5081.3  5082.3 5082.41
  5112.8  5154.1  5175.4  5226.1  5269.1  5272.3  5277.3  5287.3  5367.3  5407.3
  5417.3    5442
     272   271.3   270.8   270.1   268.9   268.2   267.3   266.9   266.7   265.4
   264.9  264.11  263.51  263.11  260.51  260.33  260.21  260.15  260.14  262.34
  262.17  261.98  261.83   261.7   261.7   261.7  261.69  261.69  261.75  259.55
  259.67  259.77  259.82  260.26  260.98  261.16  264.81  265.61  271.21   272.1
   272.1   272.4
   271.9   271.2   270.7     270   268.8   268.1   267.2   266.8   266.6   265.3
   264.8     264   263.4     263   260.4  260.22   259.8  259.01  258.18  258.17
  256.44  254.46   252.5  252.19  252.19   257.6  257.59  251.41  251.42  251.42
  251.75  252.49  253.08  254.58  257.03  257.21   264.7   265.5   271.1     272
     272   272.3
Pier Skew, UpSta & Num, DnSta & Num=,4983.8, 2 ,4983.8, 2 , 0 , 0 , 0 ,,
       1       1
  243.48   258.7
       1       1
  243.38   258.6
Pier Skew, UpSta & Num, DnSta & Num=,5033.4, 2 ,5033.4, 2 , 0 , 0 , 0 ,,
       1       1
  243.31  258.69
       1       1
  243.21  258.59
BR Coef= 1 , 1 , 0 ,1.25, 0 ,,,0.8,0,2,0,
Wspro=,,,, 1 ,,,, 0 ,,,, 0 ,,,,-1 ,-1 ,-1 , 0 , 0 , 0 , 0 , 0
BC Design=,, 0 ,, 0 ,,,,,,
BR U #Sta/Elev= 89
  4491.1     272  4501.1   271.6  4511.1   271.3  4521.1   270.8  4531.1   270.1
  4541.1   269.5  4551.1   268.9  4561.1   268.2  4571.1   267.3  4581.1   266.9
  4591.1   266.7  4621.1   265.4  4631.1   264.9    4636   264.7  4641.1   264.5
  4651.1   264.1  4661.1   263.5  4671.1   263.1  4685.1  262.37  4720.9   260.5
  4735.5  260.32  4768.8   259.9    4786   259.6  4788.9  259.55  4813.8  259.11
 4829.29  258.28  4829.4  258.27 4829.51  258.27  4833.9  258.03  4861.6  256.54
  4883.7  255.28  4896.3  254.56  4928.8   252.6  4933.8  252.29 4933.91  252.29
    4934  252.28  4934.1  252.28    4941  251.86  4941.4  253.18  4943.8  251.02
  4945.6  248.75  4955.9  246.03  4971.3  246.49  4979.3  246.13  4983.8  244.27
  4985.2  245.39  5001.3  245.36    5017  245.84  5028.4  244.32  5033.4  244.31
    5044  244.83  5053.8  247.06  5055.1  249.26  5056.3  251.13  5061.2  251.29
  5081.1  251.51 5081.19  251.51  5081.3  251.51  5081.4  251.51 5082.19  251.52
  5082.3  251.52 5082.41  251.52  5083.4  251.53  5112.8  251.85  5127.5  252.11
  5154.1  252.59  5175.4  253.18  5180.3  253.32    5224  254.62  5226.1  254.68
  5269.1  257.13  5272.3  257.31  5277.3   264.8  5281.6  265.14  5287.3   265.6
  5301.6   266.6  5311.6   267.3  5321.6     268  5337.3   269.1  5341.6   269.4
  5357.3   270.5  5361.6   270.8  5367.3   271.2  5371.6   271.3  5372.4  271.31
  5407.3   272.1  5417.3   272.1  5427.3   272.2    5442   272.4
BR U #Mann= 6
 4491.10     0.2  4674.2     0.1  4788.9    0.16  4941.4   0.053  5061.2    0.16
  5372.4     0.2
BR U Banks=4941.40,5061.20
BR D #Sta/Elev= 89
  4491.1   271.9  4501.1   271.5  4511.1   271.2  4521.1   270.7  4531.1     270
  4541.1   269.4  4551.1   268.8  4561.1   268.1  4571.1   267.2  4581.1   266.8
  4591.1   266.6  4621.1   265.3  4631.1   264.8    4636   264.6  4641.1   264.4
  4651.1     264  4661.1   263.4  4671.1     263  4685.1  262.27  4720.9   260.4
  4735.5  260.22  4768.8   259.8    4786   259.5  4788.9  259.45  4813.8  259.01
 4829.29  258.18  4829.4  258.17 4829.51  258.17  4833.9  257.93  4861.6  256.44
  4883.7  255.18  4896.3  254.46  4928.8   252.5  4933.8  252.19 4933.91  252.19
    4934  252.18  4934.1  252.18    4941  251.76  4941.4  253.08  4943.8  250.92
  4945.6  248.65  4955.9  245.93  4971.3  246.39  4979.3  246.03  4983.8  244.17
  4985.2  245.29  5001.3  245.26    5017  245.74  5028.4  244.22  5033.4  244.21
    5044  244.73  5053.8  246.96  5055.1  249.16  5056.3  251.03  5061.2  251.19
  5081.1  251.41 5081.19  251.41  5081.3  251.41  5081.4  251.41 5082.19  251.42
  5082.3  251.42 5082.41  251.42  5083.4  251.43  5112.8  251.75  5127.5  252.01
  5154.1  252.49  5175.4  253.08  5180.3  253.22    5224  254.52  5226.1  254.58
  5269.1  257.03  5272.3  257.21  5277.3   264.7  5281.6  265.04  5287.3   265.5
  5301.6   266.5  5311.6   267.2  5321.6   267.9  5337.3     269  5341.6   269.3
  5357.3   270.4  5361.6   270.7  5367.3   271.1  5371.6   271.2  5372.4  271.21
  5407.3     272  5417.3     272  5427.3   272.1    5442   272.3
BR D #Mann= 6
 4491.10     0.2  4674.2     0.1  4788.9    0.16  4941.4   0.053  5061.2    0.16
  5372.4     0.2
BR D Banks=4941.40,5061.20