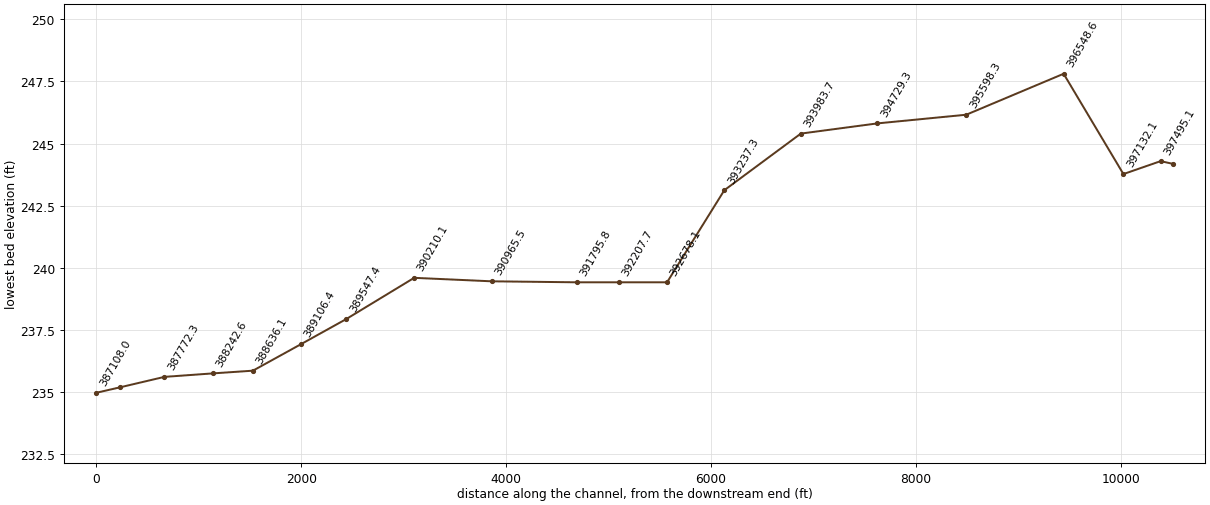
HEC-RAS study Little_River_FINAL.prj: Little River Detail Study

--- Little_River_FINAL.g01 (geometry) --- (continued)

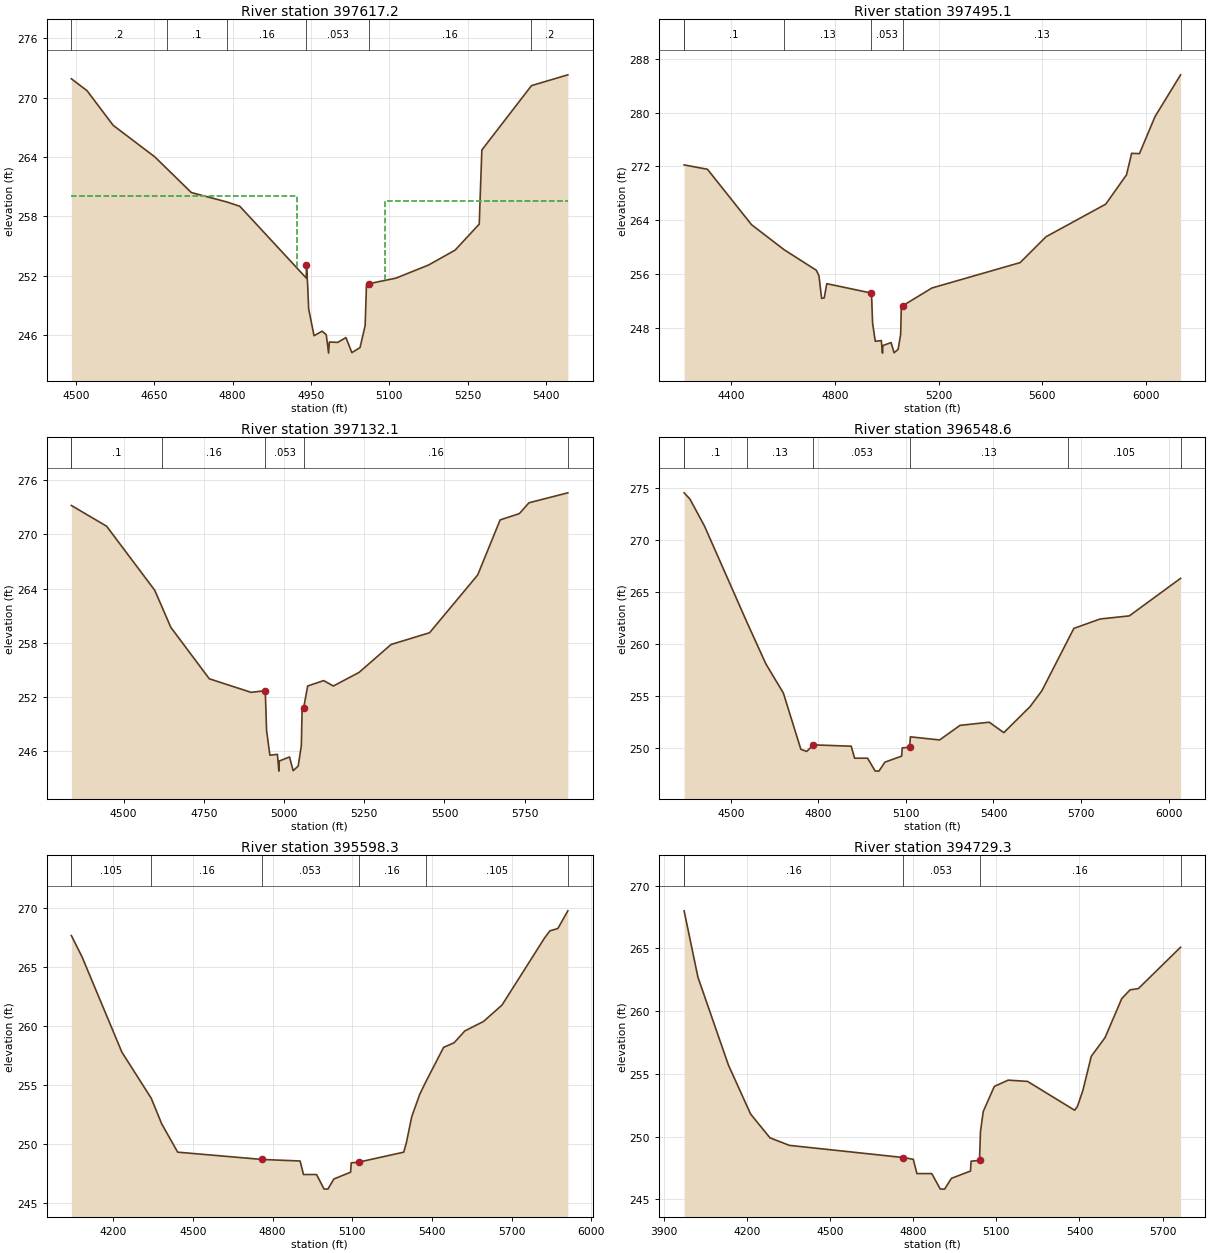
Type RM Length L Ch R = 1 ,397617.2,122.1,122.1,122.1
BEGIN DESCRIPTION:
Downstream Section of Bridge/Culvert/Weir
END DESCRIPTION:
#Sta/Elev= 30
  4491.1  271.91  4521.1  270.71  4571.1  267.21  4651.1  264.01  4720.9  260.41
  4788.9  259.46  4813.8  259.02    4941  251.77  4941.4  253.09  4943.8  250.93
  4945.6  248.66  4955.9  245.94  4971.3   246.4  4979.3  246.04  4983.8  244.18
  4985.2   245.3  5001.3  245.27    5017  245.75  5028.4  244.23    5044  244.74
  5053.8  246.97  5056.3  251.04  5061.2   251.2  5112.8  251.76  5175.4  253.09
  5226.1  254.59  5272.3  257.22  5277.3  264.71  5372.4  271.22    5442  272.31
#Mann= 6 , 1 , 0
 4491.10     0.2       0  4674.2     0.1       0  4788.9    0.16       0
  4941.4   0.053       0  5061.2    0.16       0  5372.4     0.2       0
#XS Ineff= 2 , 0
       0  4923.8   260.1  5091.1       0   259.6
Bank Sta=4941.40,5061.20
Exp/Cntr=0.5,0.3

Type RM Length L Ch R = 1 ,397495.1,363,363,363
BEGIN DESCRIPTION:
Cross Section Little River 78.5
END DESCRIPTION:
#Sta/Elev= 30
  4219.1  272.23  4309.1  271.58  4479.1  263.35    4605  259.63  4729.1  256.58
  4739.1  255.73  4749.1  252.42  4759.1  252.49  4769.1   254.6  4941.4   253.2
  4945.6  248.77  4955.9  246.05  4979.3  246.15  4983.8  244.29  4985.2  245.41
    5017  245.86  5028.4  244.34    5044  244.85  5053.8  247.08  5056.3  251.15
  5061.2  251.31  5174.5  253.96  5514.5  257.73  5614.3  261.57  5844.3   266.4
  5924.3  270.75  5944.3  273.95  5974.3   273.9  6034.3   279.4  6132.9   285.6
#Mann= 6 , 1 , 0
 4219.10     0.2       0  4219.1     0.1       0    4605    0.13       0
  4941.4   0.053       0  5061.2    0.13       0  6132.9     0.2       0
Bank Sta=4941.40,5061.20
Exp/Cntr=0.3,0.1

Type RM Length L Ch R = 1 ,397132.1,583.5,583.5,583.5
BEGIN DESCRIPTION:
Cross Section Little River 78.0
END DESCRIPTION:
#Sta/Elev= 30
    4337   273.2    4447   270.9    4597   263.8  4619.5  261.96    4647   259.7
    4767     254    4897   252.5  4941.4  252.68  4945.6  248.25  4955.9  245.53
  4979.3  245.63  4983.8  243.77  4985.2  244.89    5017  245.34  5028.4  243.82
    5044  244.33  5053.8  246.56  5056.3  250.63  5061.2  250.79  5073.6   253.2
  5123.6   253.8  5153.6   253.2  5233.6   254.7  5333.6   257.8  5453.6   259.1
  5603.6   265.5  5673.6   271.6  5733.6   272.3  5763.6   273.5  5884.6   274.6
#Mann= 6 , 1 , 0
 4337.00     0.2       0    4337     0.1       0  4619.5    0.16       0
  4941.4   0.053       0  5061.2    0.16       0  5884.6     0.2       0
Bank Sta=4941.40,5061.20
Exp/Cntr=0.3,0.1

Type RM Length L Ch R = 1 ,396548.6,950.3,950.3,950.3
BEGIN DESCRIPTION:
Cross Section Little River 77.0 CCX179
END DESCRIPTION:
#Sta/Elev= 30
  4340.1   274.5  4360.1   273.9  4410.1   271.3  4555.6  262.07  4620.1   258.1
  4680.1   255.3  4740.1   249.9  4760.1   249.7  4782.9  250.33  4912.6   250.2
  4924.2  249.05  4968.8  249.05  4994.5  247.82  5007.5  247.81    5028  248.67
  5085.3  249.25  5087.4  250.04  5112.5   250.1  5115.4   251.1  5215.4   250.8
  5285.4   252.2  5385.4   252.5  5435.4   251.5  5525.4     254  5565.4   255.5
  5654.1  260.34  5675.4   261.5  5765.4   262.4  5865.4   262.7    6041   266.3
#Mann= 7 , 1 , 0
 4340.10     0.2       0  4340.1     0.1       0  4555.6    0.13       0
  4782.9   0.053       0  5112.5    0.13       0  5654.1   0.105       0
    6041     0.2       0
Bank Sta=4782.90,5112.50
Exp/Cntr=0.3,0.1

Type RM Length L Ch R = 1 ,395598.3,869,869,869
BEGIN DESCRIPTION:
Cross Section Little River 76.0
END DESCRIPTION:
#Sta/Elev= 30
  4043.3   267.7  4083.3   265.9  4233.3   257.8    4344  253.87  4383.3   251.7
  4443.3   249.3 4761.19  248.68 4903.86  248.55 4916.62   247.4 4965.68   247.4
 4993.95  246.17 5008.25  246.16  5030.8  247.02 5093.83   247.6 5096.14  248.39
 5123.75  248.45  5293.6   249.3  5303.6   250.1  5323.6   252.3  5353.6   254.2
  5377.5  255.31  5443.6   258.2  5483.6   258.6  5523.6   259.6  5593.6   260.4
  5663.6   261.8  5823.6   267.5  5843.6   268.1  5873.6   268.3    5911   269.8
#Mann= 7 , 1 , 0
 4043.30     0.2       0  4043.3   0.105       0    4344    0.16       0
 4761.19   0.053       0 5123.75    0.16       0  5377.5   0.105       0
    5911     0.2       0
Bank Sta=4761.19,5123.75
Exp/Cntr=0.3,0.1

Type RM Length L Ch R = 1 ,394729.3,745.6,745.6,745.6
BEGIN DESCRIPTION:
Cross Section Little River 75.0
END DESCRIPTION:
#Sta/Elev= 30
  3972.6     268  4022.6   262.7  4132.6   255.7  4212.6   251.8  4282.6   249.9
  4352.6   249.3 4763.48  248.33 4799.84  248.19 4813.04  247.05 4866.56  247.05
  4897.4  245.82    4913  245.81  4937.6  246.67 5006.36  247.25 5008.88  248.04
    5039   248.1  5042.5   250.4  5052.5     252  5092.5     254  5142.5   254.5
  5212.5   254.4  5382.5   252.1  5392.5   252.4  5412.5   253.7  5442.5   256.4
  5492.5   257.9  5552.5     261  5582.5   261.7  5612.5   261.8    5765   265.1
#Mann= 5 , 1 , 0
 3972.60     0.2       0  3972.6    0.16       0 4763.48   0.053       0
    5039    0.16       0    5765     0.2       0
Bank Sta=4763.48,5039.00
Exp/Cntr=0.3,0.1

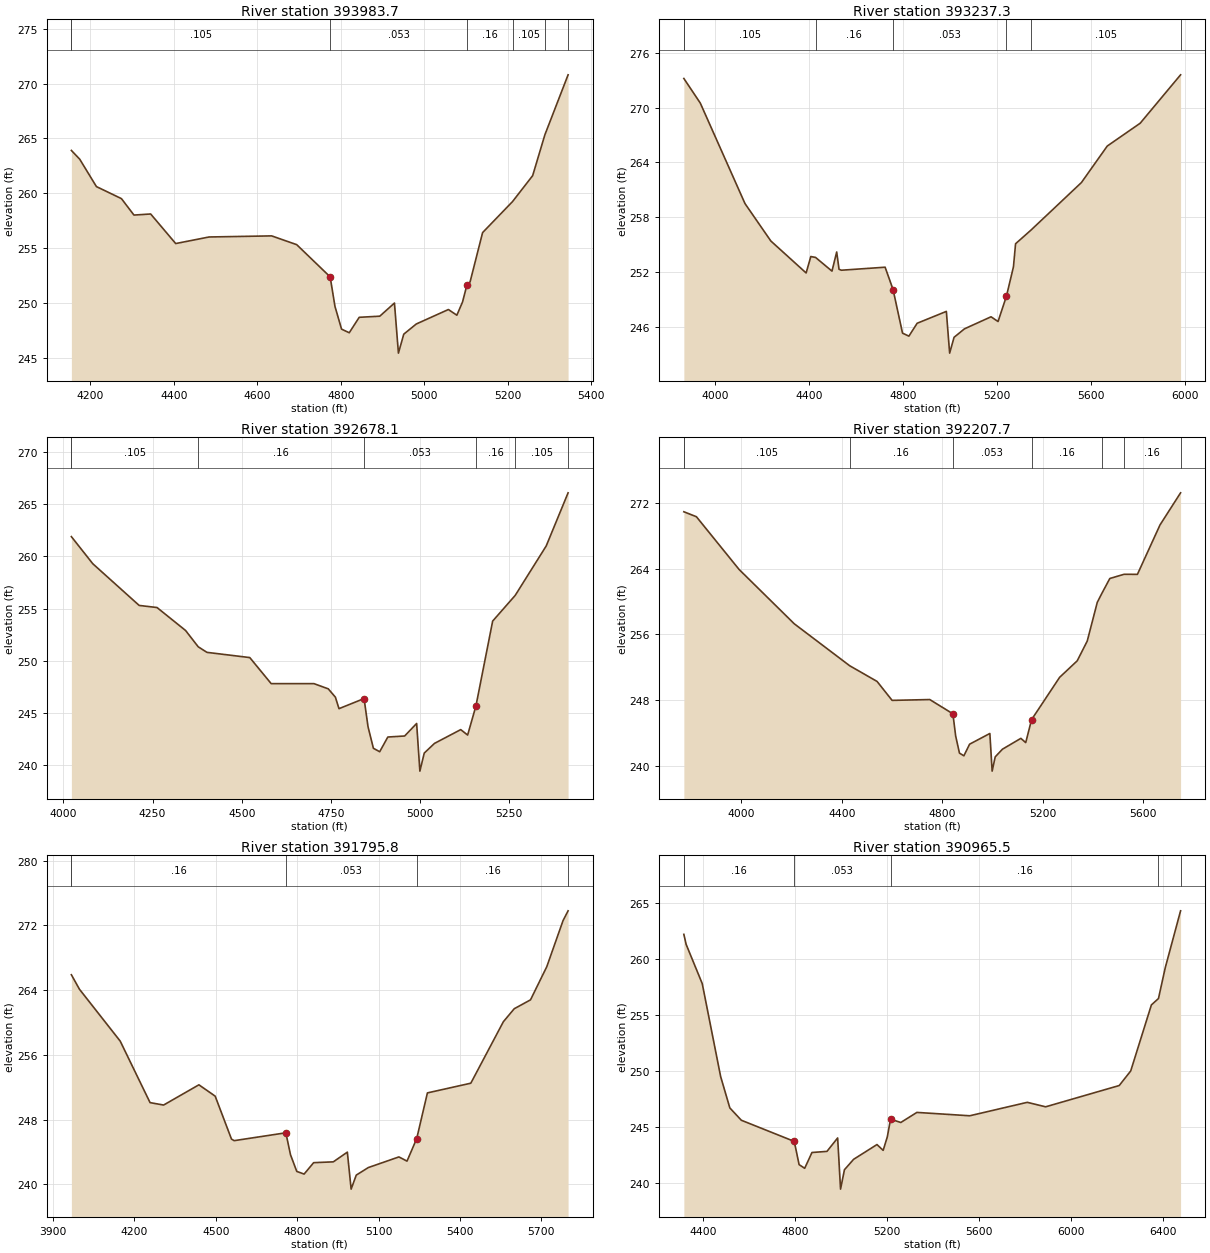
Type RM Length L Ch R = 1 ,393983.7,746.4,746.4,746.4
BEGIN DESCRIPTION:
Cross Section Little River 74.0
END DESCRIPTION:
#Sta/Elev= 30
  4154.2   263.9  4174.2   263.1  4214.2   260.6  4274.2   259.5  4304.2     258
  4344.2   258.1  4404.2   255.4  4484.2     256  4634.2   256.1  4694.2   255.3
 4774.38  252.36 4785.94  249.66 4801.71  247.59 4820.14  247.26 4844.01  248.67
 4893.31  248.77 4928.46  249.97 4937.98   245.4 4950.77  247.13 4980.82  248.06
 5057.73  249.38    5078  248.86 5091.66  250.07 5102.34  251.65  5109.7   251.9
  5139.7   256.4  5211.4  259.23  5259.7   261.6  5288.9  265.32  5344.6   270.8
#Mann= 7 , 1 , 0
 4154.20     0.2       0  4154.2   0.105       0 4774.38   0.053       0
 5102.34    0.16       0  5211.4   0.105       0  5288.9    0.16       0
  5344.6     0.2       0
Bank Sta=4774.38,5102.34
Exp/Cntr=0.3,0.1

Type RM Length L Ch R = 1 ,393237.3,559.2,559.2,559.2
BEGIN DESCRIPTION:
Cross Section Little River 73.0 (CCX_WA178)
END DESCRIPTION:
#Sta/Elev= 30
  3868.4   273.2  3938.4   270.5  4128.4   259.5  4238.4   255.4  4388.4   251.9
  4408.4   253.7  4428.6   253.6  4498.4   252.1  4518.4   254.2  4528.4   252.3
  4538.4   252.2  4724.4  252.53  4758.2  250.08  4798.4  245.31  4825.5  244.98
  4860.6  246.39  4984.8  247.69  4998.8  243.12  5017.6  244.85  5061.8  245.78
  5174.9   247.1  5204.7  246.58  5240.5  249.37  5270.2  252.57  5279.2   255.1
    5345   256.6  5559.2   261.8  5669.2   265.8  5809.2   268.3    5981   273.6
#Mann= 7 , 1 , 0
 3868.40     0.2       0  3868.4   0.105       0  4428.6    0.16       0
  4758.2   0.053       0  5240.5    0.16       0    5345   0.105       0
    5981     0.2       0
Bank Sta=4758.20,5240.50
Exp/Cntr=0.3,0.1

Type RM Length L Ch R = 1 ,392678.1,470.4,470.4,470.4
BEGIN DESCRIPTION:
Cross Section Little River 72.0
END DESCRIPTION:
#Sta/Elev= 30
  4022.5   261.9  4082.5   259.3  4212.5   255.3  4262.5   255.1  4342.5   252.9
  4378.1  251.33  4402.5   250.8  4522.5   250.3  4582.5   247.8  4702.5   247.8
  4742.5   247.3  4762.5   246.5  4772.5   245.4 4842.83  246.37 4853.88  243.67
 4868.96   241.6 4886.58  241.27 4909.39  242.68 4956.51  242.78 4990.12  243.98
 4999.22  239.41 5011.44  241.14 5040.17  242.07 5113.68  243.39 5133.06  242.87
 5156.33  245.66  5203.2   253.8  5266.3  256.26  5353.2     261  5414.6   266.1
#Mann= 7 , 1 , 0
 4022.50     0.2       0  4022.5   0.105       0  4378.1    0.16       0
 4842.83   0.053       0 5156.33    0.16       0  5266.3   0.105       0
  5414.6     0.2       0
Bank Sta=4842.83,5156.33
Exp/Cntr=0.3,0.1

Type RM Length L Ch R = 1 ,392207.7,411.9,411.9,411.9
BEGIN DESCRIPTION:
Cross Section Little River 71.5
END DESCRIPTION:
#Sta/Elev= 30
  3770.6   270.9  3820.6   270.3  3990.6   263.9  4210.6   257.3  4431.3  252.21
  4540.6   250.3  4600.6     248  4750.6   248.1 4842.83  246.37 4853.88  243.67
 4868.96   241.6 4886.58  241.27 4909.39  242.68 4990.12  243.98 4999.22  239.41
 5011.44  241.14 5040.17  242.07 5113.68  243.39 5133.06  242.87 5156.33  245.66
  5268.2   250.8  5338.2   252.8  5378.2   255.2  5418.2   259.9  5435.1  260.91
  5468.2   262.8  5525.2  263.31  5578.2   263.3  5668.2   269.3  5750.2   273.2
#Mann= 8 , 1 , 0
 3770.60     0.2       0  3770.6   0.105       0  4431.3    0.16       0
 4842.83   0.053       0 5156.33    0.16       0  5435.1   0.105       0
  5525.2    0.16       0  5750.2     0.2       0
Bank Sta=4842.83,5156.33
Exp/Cntr=0.3,0.1

Type RM Length L Ch R = 1 ,391795.8,830.3,830.3,830.3
BEGIN DESCRIPTION:
Cross Section Little River 71.0
END DESCRIPTION:
#Sta/Elev= 30
  3967.7   265.9  3997.7   264.1  4147.7   257.7  4257.7   250.1  4307.7   249.8
  4437.7   252.3  4497.7   250.9  4557.7   245.6  4567.7   245.4  4758.2  246.37
  4775.2  243.67  4798.4   241.6  4825.5  241.27  4860.6  242.68  4933.1  242.78
  4984.8  243.98  4998.8  239.41  5017.6  241.14  5061.8  242.07  5174.9  243.39
  5204.7  242.87  5240.5  245.66  5279.9   251.3  5439.9   252.5  5559.9   260.1
  5599.9   261.7  5659.9   262.8  5719.9   266.9  5779.9   272.6  5798.4   273.8
#Mann= 5 , 1 , 0
 3967.70     0.2       0  3967.7    0.16       0  4758.2   0.053       0
  5240.5    0.16       0  5798.4     0.2       0
Bank Sta=4758.20,5240.50
Exp/Cntr=0.3,0.1

Type RM Length L Ch R = 1 ,390965.5,755.4,755.4,755.4
BEGIN DESCRIPTION:
Cross Section Little River 70.0
END DESCRIPTION:
#Sta/Elev= 30
  4317.4   262.2  4327.4   261.3  4397.4   257.8  4477.4   249.5  4517.4   246.7
  4567.4   245.6 4797.68  243.71 4818.56  241.64 4842.95  241.31 4874.54  242.72
 4939.79  242.82 4986.32  244.02 4998.92  239.45 5015.84  241.18 5055.62  242.11
 5157.41  243.43 5184.23  242.91 5202.32  244.12 5216.45   245.7  5260.9   245.4
  5330.9   246.3  5560.9     246  5810.9   247.2  5890.9   246.8  6210.9   248.7
  6260.9     250  6350.9   255.9  6381.7  256.47  6410.9   259.2  6477.8   264.3
#Mann= 6 , 1 , 0
 4317.40     0.2       0  4317.4    0.16       0 4797.68   0.053       0
 5216.45    0.16       0  6381.7   0.105       0  6477.8     0.2       0
Bank Sta=4797.68,5216.45
Exp/Cntr=0.3,0.1

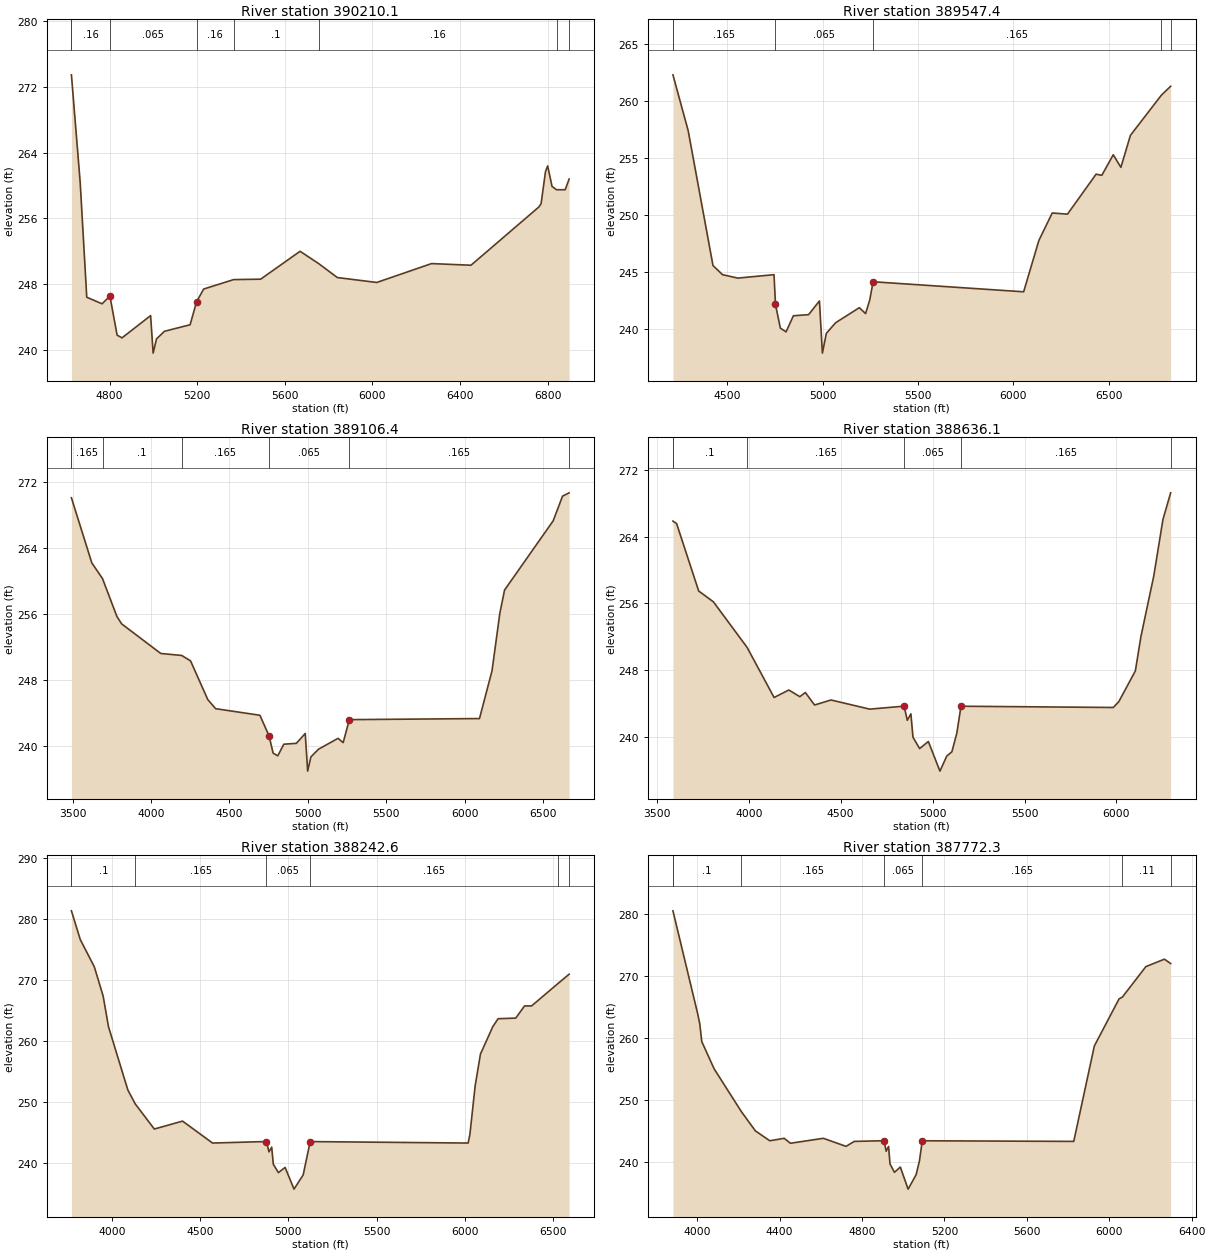
Type RM Length L Ch R = 1 ,390210.1,662.7,662.7,662.7
BEGIN DESCRIPTION:
Cross Section Little River 69.0
END DESCRIPTION:
#Sta/Elev= 30
  4626.1   273.5  4666.1   260.4  4696.1   246.4  4766.1   245.6 4801.72  246.55
 4834.69  241.78 4856.91  241.45 4987.54  244.16 4999.02  239.59 5014.43  241.32
 5050.68  242.25 5167.85  243.05 5197.21  245.84  5229.7   247.4  5366.7  248.55
  5489.7   248.6  5669.7     252  5754.6   250.5  5839.7   248.8  6019.7   248.2
  6269.7   250.5  6449.7   250.3  6759.7   257.4  6769.7   257.8  6789.7   261.7
  6799.7   262.4  6819.7   259.9  6840.1   259.5  6879.7   259.5  6897.6   260.8
#Mann= 8 , 1 , 0
 4626.10     0.2       0  4626.1    0.16       0 4801.72   0.065       0
 5197.21    0.16       0  5366.7     0.1       0  5754.6    0.16       0
  6840.1   0.105       0  6897.6     0.2       0
Bank Sta=4801.72,5197.21
Exp/Cntr=0.3,0.1

Type RM Length L Ch R = 1 ,389547.4,441,441,441
BEGIN DESCRIPTION:
Cross Section Little River 68.0
END DESCRIPTION:
#Sta/Elev= 30
    4215   262.3    4295   257.4    4425   245.6    4475   244.8    4555   244.5
    4745   244.8 4752.72  242.19 4778.24  240.12 4808.05  239.79 4846.66   241.2
 4926.41   241.3 4983.28   242.5 4998.68  237.93 5019.36  239.66 5067.98  240.59
 5192.39  241.91 5225.17  241.39 5247.28   242.6 5264.55  244.18    6054   243.3
    6134   247.8    6204   250.2    6284   250.1    6434   253.6    6464   253.5
    6524   255.3    6564   254.2    6614     257  6775.9  260.51  6824.9   261.3
#Mann= 6 , 1 , 0
 4215.00     0.2       0    4215   0.165       0 4752.72   0.065       0
 5264.55   0.165       0  6775.9   0.105       0  6824.9     0.2       0
Bank Sta=4752.72,5264.55
Exp/Cntr=0.3,0.1

Type RM Length L Ch R = 1 ,389106.4,470.3,470.3,470.3
BEGIN DESCRIPTION:
Cross Section Little River 66.7
END DESCRIPTION:
#Sta/Elev= 30
  3491.7   270.1  3621.7   262.2    3690  260.29  3781.7   255.7  3811.7   254.8
  4061.7   251.2  4195.3  250.96  4251.7   250.3  4361.7   245.6  4411.7   244.5
  4694.1   243.7 4752.72  241.18 4778.24  239.11 4808.05  238.78 4846.66  240.19
 4926.41  240.29 4983.28  241.49 4998.68  236.92 5019.36  238.65 5067.98  239.58
 5192.39   240.9 5225.17  240.38 5264.55  243.17  6094.7   243.3  6174.7   249.1
  6224.7   256.1  6254.7   258.9  6564.7   267.3  6624.7   270.3  6666.5   270.7
#Mann= 7 , 1 , 0
 3491.70     0.2       0  3491.7   0.165       0    3690     0.1       0
  4195.3   0.165       0 4752.72   0.065       0 5264.55   0.165       0
  6666.5     0.2       0
Bank Sta=4752.72,5264.55
Exp/Cntr=0.3,0.1

Type RM Length L Ch R = 1 ,388636.1,393.5,393.5,393.5
BEGIN DESCRIPTION:
Cross Section Little River 67.0
END DESCRIPTION:
#Sta/Elev= 30
  3588.1   265.9  3608.1   265.6  3728.1   257.5  3808.1   256.2  3991.4  250.72
  4138.1   244.7  4218.1   245.6  4278.1   244.8  4308.1   245.3  4358.1   243.8
  4448.1   244.4  4658.1   243.3    4845  243.66  4862.5  241.96    4882  242.74
  4893.5  239.92  4929.5  238.56    4977  239.41    5040  235.85    5077  237.66
    5105  238.18    5132  240.44  5154.5  243.65  5982.7   243.5  6012.7   244.2
  6102.7   247.9  6132.7     252  6202.7   259.3  6252.7   266.1  6294.5   269.3
#Mann= 6 , 1 , 0
 3588.10     0.2       0  3588.1     0.1       0  3991.4   0.165       0
    4845   0.065       0  5154.5   0.165       0  6294.5     0.2       0
Bank Sta=4845.00,5154.50
Exp/Cntr=0.3,0.1

Type RM Length L Ch R = 1 ,388242.6,470.3,470.3,470.3
BEGIN DESCRIPTION:
Cross Section Little River 66.5
END DESCRIPTION:
#Sta/Elev= 30
  3770.2   281.4  3820.2   276.7  3900.2   272.2  3950.2   267.4  3980.2   262.4
  4090.2     252  4132.3  249.71  4240.2   245.6  4400.2   246.9  4570.2   243.3
    4876  243.55    4890  241.85  4905.6  242.63  4914.8  239.81  4943.6  238.45
  4981.6   239.3    5032  235.74    5084  238.07  5123.6  243.54    6019   243.3
    6029   244.7    6059   252.7    6089   257.9    6159   262.4    6189   263.7
    6289   263.8    6339   265.8    6379   265.8  6528.3  269.47  6591.6     271
#Mann= 7 , 1 , 0
 3770.20     0.2       0  3770.2     0.1       0  4132.3   0.165       0
    4876   0.065       0  5123.6   0.165       0  6528.3    0.11       0
  6591.6     0.2       0
Bank Sta=4876.00,5123.60
Exp/Cntr=0.3,0.1

Type RM Length L Ch R = 1 ,387772.3,432.8,432.8,432.8
BEGIN DESCRIPTION:
Cross Section Little River 66.2
END DESCRIPTION:
#Sta/Elev= 30
  3882.8   280.5  4002.8   263.9  4012.8   262.3  4022.8   259.4  4082.8     255
  4215.1  248.09  4282.8     245  4352.8   243.4  4422.8   243.8  4452.8     243
  4612.8   243.8  4722.8   242.5  4762.8   243.3    4907  243.41  4917.5  241.71
  4929.2  242.49  4936.1  239.67  4957.7  238.31  4986.2  239.16    5024   235.6
    5063  237.93  5079.2  240.19  5092.7   243.4  5827.8   243.3  5927.8   258.7
  6047.8   266.3  6063.7  266.58  6177.8   271.5  6267.8   272.7    6298     272
#Mann= 7 , 1 , 0
 3882.80     0.2       0  3882.8     0.1       0  4215.1   0.165       0
    4907   0.065       0  5092.7   0.165       0  6063.7    0.11       0
    6298     0.2       0
Bank Sta=4907.00,5092.70
Exp/Cntr=0.3,0.1

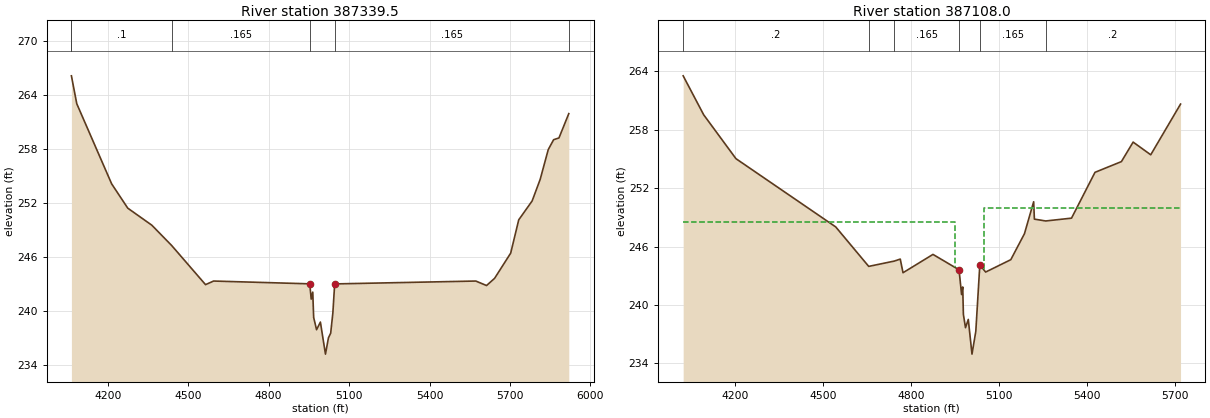
Type RM Length L Ch R = 1 ,387339.5,231.5,231.5,231.5
BEGIN DESCRIPTION:
Cross Section Little River 66.0
END DESCRIPTION:
#Sta/Elev= 30
  4064.9   266.1  4084.9     263  4214.9   254.1  4274.9   251.4  4364.9   249.5
  4438.9  247.24  4564.9   242.9  4594.9   243.3  4953.5  242.99 4958.75  241.29
  4964.6  242.07 4968.05  239.25 4978.85  237.89  4993.1  238.74    5012  235.18
  5023.1  236.99  5031.5  237.51  5039.6  239.77 5046.35  242.98  5572.5   243.3
  5612.5   242.8  5642.5   243.6  5702.5   246.4  5732.5   250.1  5782.5   252.2
  5812.5   254.6  5842.5   257.9  5862.5     259  5882.5   259.2  5919.1   261.9
#Mann= 6 , 1 , 0
 4064.90     0.2       0  4064.9     0.1       0  4438.9   0.165       0
  4953.5   0.065       0 5046.35   0.165       0  5919.1     0.2       0
Bank Sta=4953.50,5046.35
Exp/Cntr=0.5,0.3

Type RM Length L Ch R = 1 ,387108.0,41,41,41
BEGIN DESCRIPTION:
Upstream Section of Bridge/Culvert/Weir
END DESCRIPTION:
#Sta/Elev= 30
  4023.5  263.51  4093.5  259.51  4203.5  255.01  4543.5  248.01    4656  243.96
  4743.8  244.51  4763.5  244.71  4772.9  243.31    4875  245.19  4963.9  243.61
  4972.5  241.07  4976.4  241.85  4978.7  239.03  4985.9  237.67  4995.4  238.52
    5008  234.96    5021  237.29  5034.7  244.11  5054.6  243.38  5140.3  244.65
  5186.8  247.31  5218.2  250.59  5220.7  248.81  5259.3  248.62  5347.3  248.91
  5427.3  253.61  5517.3  254.71  5557.3  256.71  5617.3  255.41  5718.9  260.61
#Mann= 6 , 1 , 0
 4023.50     0.2       0    4656     0.1       0  4743.8   0.165       0
  4963.9   0.065       0  5034.7   0.165       0  5259.3     0.2       0
#XS Ineff= 2 , 0
       0  4949.9   248.5  5047.4       0   249.9
Bank Sta=4963.90,5034.70
Exp/Cntr=0.5,0.3