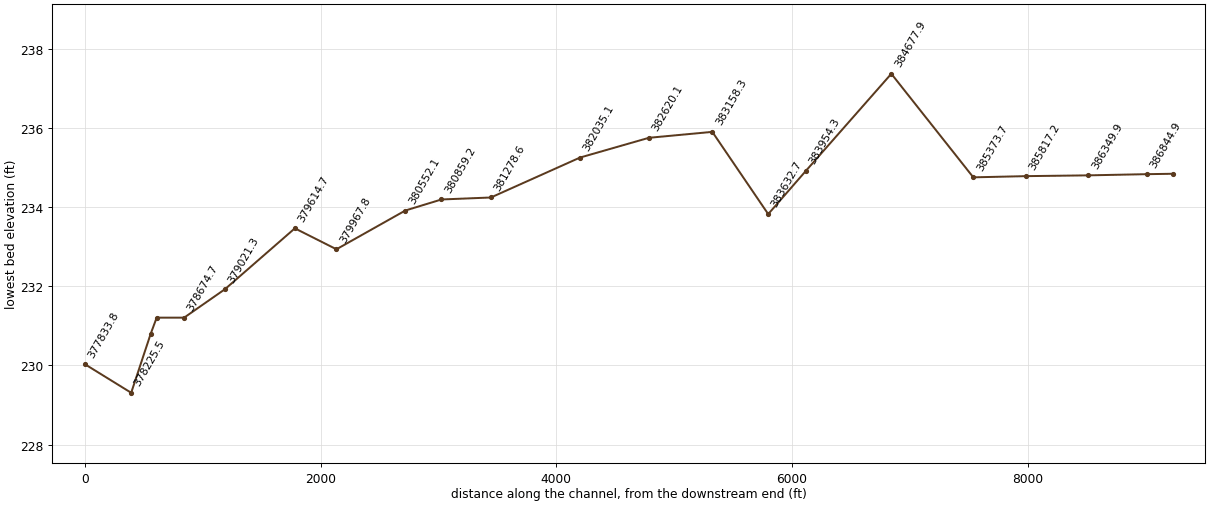
HEC-RAS study Little_River_FINAL.prj: Little River Detail Study

--- Little_River_FINAL.g01 (geometry) --- (continued)

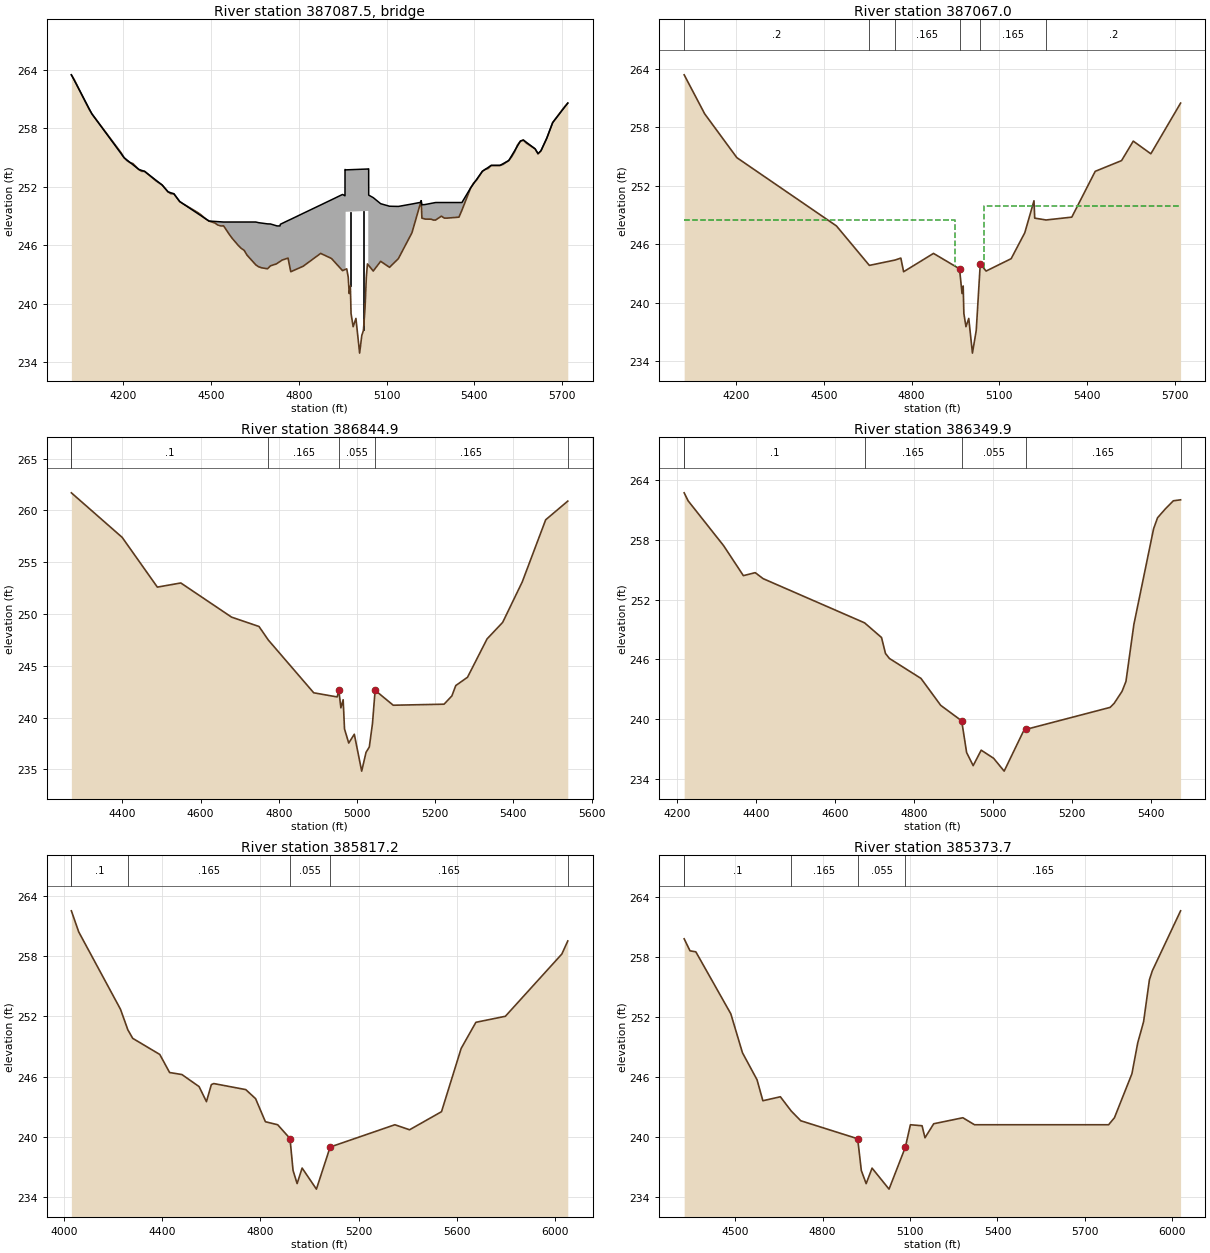
Type RM Length L Ch R = 3 ,387087.5,,,
BEGIN DESCRIPTION:
GLORY RD
Structure ID: WK_LITR9
END DESCRIPTION:
Bridge Culvert--1,0,-1,-1, 0
Deck Dist Width WeirC Skew NumUp NumDn MinLoCord MaxHiCord MaxSubmerge Is_Ogee
10,21,2.6,, 60, 60,,,0.95,0,1,1,,
  4023.5  4093.5  4203.5  4253.5  4273.5  4333.5  4353.5  4373.5  4393.5  4493.5
  4543.5  4573.5  4653.5  4663.5  4693.5  4703.5    4726    4736  4737.2  4763.5
  4772.9  4815.1    4875  4911.8  4949.7 4957.99  4958.1 4960.01  4960.1 5037.49
  5037.6  5038.9 5039.01  5054.6  5079.8  5110.1  5140.3  5186.8  5216.5  5218.2
  5220.7  5230.7  5267.3  5287.3  5297.3  5347.3  5357.3  5387.3  5427.3  5457.3
  5487.3  5517.3  5557.3  5567.3  5607.3  5617.3  5627.3  5647.3  5667.3  5718.9
   263.5   259.5     255   253.8   253.6   252.2   251.5   251.3   250.5   248.5
   248.4   248.4   248.4  248.33  248.21   248.2     248     248  248.17  248.55
  248.68  249.29  250.15  250.68  251.23  251.09  253.79  253.75  253.75  253.84
  253.84  253.86  251.16   250.9  250.28  250.02     250  250.25  250.42  250.59
  250.17  250.19   250.4   250.4   250.4   250.4   250.4  251.91  253.61  254.21
  254.21  254.71  256.71  256.81  255.91  255.41  255.71  257.01   258.6   260.6
   263.5   259.5     255   253.8   253.6   252.2   251.5   251.3   250.5   248.5
     248   246.7     244   243.8   243.6   243.9  244.15  244.35  244.37   244.7
   243.3  243.86  245.18  244.66  243.41  243.52  243.52  243.55  249.45  249.54
  243.99  243.95  243.94  243.37  244.37  243.75  244.64   247.3   250.4  250.58
   248.8   248.7   248.6     249   248.8   248.9   249.6   251.9   253.6   254.2
   254.2   254.7   256.7   256.8   255.9   255.4   255.7     257   258.6   260.6
  4023.5  4093.5  4203.5  4253.5  4273.5  4333.5  4353.5  4373.5  4393.5  4493.5
  4543.5  4573.5  4653.5  4663.5  4693.5  4703.5    4726    4736  4737.2  4763.5
  4772.9  4815.1    4875  4911.8  4949.7 4957.99  4958.1 4960.01  4960.1 5037.49
  5037.6  5038.9 5039.01  5054.6  5079.8  5110.1  5140.3  5186.8  5216.5  5218.2
  5220.7  5230.7  5267.3  5287.3  5297.3  5347.3  5357.3  5387.3  5427.3  5457.3
  5487.3  5517.3  5557.3  5567.3  5607.3  5617.3  5627.3  5647.3  5667.3  5718.9
   263.5   259.5     255   253.8   253.6   252.2   251.5   251.3   250.5   248.5
   248.4   248.4   248.4  248.33  248.21   248.2     248     248  248.17  248.55
  248.68  249.29  250.15  250.68  251.23  251.09  253.79  253.75  253.75  253.84
  253.84  253.86  251.16   250.9  250.28  250.02     250  250.25  250.42  250.59
  250.17  250.19   250.4   250.4   250.4   250.4   250.4  251.91  253.61  254.21
  254.21  254.71  256.71  256.81  255.91  255.41  255.71  257.01   258.6   260.6
   263.4   259.4   254.9   253.7   253.5   252.1   251.4   251.2   250.4   248.4
   247.9   246.6   243.9   243.7   243.5   243.8  244.05  244.25  244.27   244.6
   243.2  243.76  245.08  244.56  243.31  243.42  243.42  243.45  249.35  249.44
  243.89  243.85  243.84  243.27  244.27  243.65  244.54   247.2   250.3  250.48
   248.7   248.6   248.5   248.9   248.7   248.8   249.5   251.8   253.5   254.1
   254.1   254.6   256.6   256.7   255.8   255.3   255.6   256.9   258.5   260.5
Pier Skew, UpSta & Num, DnSta & Num=,4976.4, 2 ,4976.4, 2 , 0 , 0 , 0 ,,
     1.2     1.2
   240.1  250.47
     1.2     1.2
     240  250.37
Pier Skew, UpSta & Num, DnSta & Num=,5021.0, 2 ,5021.0, 2 , 0 , 0 , 0 ,,
     1.2     1.2
  236.22  250.52
     1.2     1.2
  236.12  250.42
BR Coef= 1 , 1 , 0 ,1.25, 0 ,,,0.8,0,2,0,
Wspro=,,,, 1 ,,,, 0 ,,,, 0 ,,,,-1 ,-1 ,-1 , 0 , 0 , 0 , 0 , 0
BC Design=,, 0 ,, 0 ,,,,,,
BR U #Sta/Elev= 153
  4023.5   263.5  4033.5     263  4043.5   262.4  4053.5   261.8  4063.5   261.2
  4073.5   260.6  4083.5     260  4093.5   259.5  4183.5   255.9  4193.5   255.5
  4203.5     255  4213.5   254.7  4223.5   254.5  4233.5   254.4  4253.5   253.8
  4263.5   253.6  4273.5   253.6  4313.5   252.6  4323.5   252.4  4333.5   252.2
  4353.5   251.5  4363.5   251.3  4373.5   251.3  4383.5   250.9  4393.5   250.5
  4403.5   250.3  4453.5   249.4  4463.5   249.2  4483.5   248.7  4493.5   248.5
    4506  248.38  4513.5   248.3  4523.5   248.1  4533.5     248  4543.5     248
  4563.5   247.1  4573.5   246.7  4593.5     246  4603.5   245.7  4613.5   245.5
  4623.5     245  4653.5     244    4656  243.95  4663.5   243.8    4666  243.78
  4673.5   243.7    4676  243.69  4693.5   243.6    4696  243.68  4703.5   243.9
    4706  243.93  4713.5     244    4716  244.03  4723.5   244.1    4726  244.15
    4736  244.35  4737.2  244.37  4743.5   244.5  4743.8   244.5  4753.5   244.6
  4763.5   244.7  4772.9   243.3  4815.1  243.86    4875  245.18  4911.8  244.66
  4949.7  243.41  4950.7  243.42 4957.99  243.52  4958.1  243.52 4958.21  243.52
  4959.9  243.55 4960.01  243.55  4960.1  243.55  4960.2  243.55  4963.9   243.6
    4969  242.76  4972.5  241.06  4976.4  241.84  4978.7  239.02  4985.9  237.66
  4995.4  238.51    5008  234.95  5015.4  236.76    5021  237.28  5026.4  239.54
  5030.9  242.75  5034.7   244.1  5037.4     244 5037.49     244  5037.6  243.99
  5037.7  243.99 5038.79  243.95  5038.9  243.95 5039.01  243.94  5041.7  243.84
  5054.6  243.37  5079.8  244.37  5086.5  244.23  5110.1  243.75  5129.7  244.33
  5140.3  244.64  5171.7  246.44  5186.8   247.3  5216.5   250.4  5218.2  250.58
  5220.7   248.8  5221.8  248.79  5230.7   248.7  5231.8   248.7  5241.8   248.7
  5250.7   248.7  5251.8  248.69  5259.3  248.61  5260.7   248.6  5267.3   248.6
  5287.3     249  5297.3   248.8  5307.3   248.8  5347.3   248.9  5357.3   249.6
  5387.3   251.9  5397.3   252.4  5407.3   252.7  5427.3   253.6  5437.3   253.8
  5447.3   253.9  5457.3   254.2  5467.3   254.2  5477.3   254.2  5487.3   254.2
  5497.3   254.3  5507.3   254.5  5517.3   254.7  5527.3   255.1  5537.3   255.6
  5547.3   256.3  5557.3   256.7  5567.3   256.8  5577.3   256.5  5587.3   256.3
  5597.3   256.1  5607.3   255.9  5617.3   255.4  5627.3   255.7  5647.3     257
    5656   257.7  5657.3   257.8  5667.3   258.6  5677.3     259  5687.3   259.4
  5697.3   259.8  5707.3   260.2  5718.9   260.6
BR U #Mann= 6
 4023.50     0.2    4656     0.1  4743.8   0.165  4963.9   0.065  5034.7   0.165
  5259.3     0.2
BR U Banks=4963.90,5034.70
BR D #Sta/Elev= 153
  4023.5   263.4  4033.5   262.9  4043.5   262.3  4053.5   261.7  4063.5   261.1
  4073.5   260.5  4083.5   259.9  4093.5   259.4  4183.5   255.8  4193.5   255.4
  4203.5   254.9  4213.5   254.6  4223.5   254.4  4233.5   254.3  4253.5   253.7
  4263.5   253.5  4273.5   253.5  4313.5   252.5  4323.5   252.3  4333.5   252.1
  4353.5   251.4  4363.5   251.2  4373.5   251.2  4383.5   250.8  4393.5   250.4
  4403.5   250.2  4453.5   249.3  4463.5   249.1  4483.5   248.6  4493.5   248.4
    4506  248.28  4513.5   248.2  4523.5     248  4533.5   247.9  4543.5   247.9
  4563.5     247  4573.5   246.6  4593.5   245.9  4603.5   245.6  4613.5   245.4
  4623.5   244.9  4653.5   243.9    4656  243.85  4663.5   243.7    4666  243.68
  4673.5   243.6    4676  243.59  4693.5   243.5    4696  243.58  4703.5   243.8
    4706  243.83  4713.5   243.9    4716  243.93  4723.5     244    4726  244.05
    4736  244.25  4737.2  244.27  4743.5   244.4  4743.8   244.4  4753.5   244.5
  4763.5   244.6  4772.9   243.2  4815.1  243.76    4875  245.08  4911.8  244.56
  4949.7  243.31  4950.7  243.32 4957.99  243.42  4958.1  243.42 4958.21  243.42
  4959.9  243.45 4960.01  243.45  4960.1  243.45  4960.2  243.45  4963.9   243.5
    4969  242.66  4972.5  240.96  4976.4  241.74  4978.7  238.92  4985.9  237.56
  4995.4  238.41    5008  234.85  5015.4  236.66    5021  237.18  5026.4  239.44
  5030.9  242.65  5034.7     244  5037.4   243.9 5037.49   243.9  5037.6  243.89
  5037.7  243.89 5038.79  243.85  5038.9  243.85 5039.01  243.84  5041.7  243.74
  5054.6  243.27  5079.8  244.27  5086.5  244.13  5110.1  243.65  5129.7  244.23
  5140.3  244.54  5171.7  246.34  5186.8   247.2  5216.5   250.3  5218.2  250.48
  5220.7   248.7  5221.8  248.69  5230.7   248.6  5231.8   248.6  5241.8   248.6
  5250.7   248.6  5251.8  248.59  5259.3  248.51  5260.7   248.5  5267.3   248.5
  5287.3   248.9  5297.3   248.7  5307.3   248.7  5347.3   248.8  5357.3   249.5
  5387.3   251.8  5397.3   252.3  5407.3   252.6  5427.3   253.5  5437.3   253.7
  5447.3   253.8  5457.3   254.1  5467.3   254.1  5477.3   254.1  5487.3   254.1
  5497.3   254.2  5507.3   254.4  5517.3   254.6  5527.3     255  5537.3   255.5
  5547.3   256.2  5557.3   256.6  5567.3   256.7  5577.3   256.4  5587.3   256.2
  5597.3     256  5607.3   255.8  5617.3   255.3  5627.3   255.6  5647.3   256.9
    5656   257.6  5657.3   257.7  5667.3   258.5  5677.3   258.9  5687.3   259.3
  5697.3   259.7  5707.3   260.1  5718.9   260.5
BR D #Mann= 6
 4023.50     0.2    4656     0.1  4743.8   0.165  4963.9   0.065  5034.7   0.165
  5259.3     0.2
BR D Banks=4963.90,5034.70

Type RM Length L Ch R = 1 ,387067.0,222.1,222.1,222.1
BEGIN DESCRIPTION:
Downstream Section of Bridge/Culvert/Weir
END DESCRIPTION:
#Sta/Elev= 30
  4023.5   263.4  4093.5   259.4  4203.5   254.9  4543.5   247.9    4656  243.85
  4743.8   244.4  4763.5   244.6  4772.9   243.2    4875  245.08  4963.9   243.5
  4972.5  240.96  4976.4  241.74  4978.7  238.92  4985.9  237.56  4995.4  238.41
    5008  234.85    5021  237.18  5034.7     244  5054.6  243.27  5140.3  244.54
  5186.8   247.2  5218.2  250.48  5220.7   248.7  5259.3  248.51  5347.3   248.8
  5427.3   253.5  5517.3   254.6  5557.3   256.6  5617.3   255.3  5718.9   260.5
#Mann= 6 , 1 , 0
 4023.50     0.2       0    4656     0.1       0  4743.8   0.165       0
  4963.9   0.065       0  5034.7   0.165       0  5259.3     0.2       0
#XS Ineff= 2 , 0
       0  4949.9   248.5  5047.4       0   249.9
Bank Sta=4963.90,5034.70
Exp/Cntr=0.5,0.3

Type RM Length L Ch R = 1 ,386844.9,495,495,495
BEGIN DESCRIPTION:
Cross Section Little River 65.0
END DESCRIPTION:
#Sta/Elev= 30
  4269.3   261.7  4399.3   257.4  4489.3   252.6  4549.3     253  4679.3   249.7
  4749.3   248.8  4773.2  247.49  4889.3   242.4  4949.3     242  4953.5  242.65
 4958.75  240.95  4964.6  241.73 4968.05  238.91 4978.85  237.55  4993.1   238.4
    5012  234.84  5023.1  236.65  5031.5  237.17  5039.6  239.43 5046.35  242.64
  5092.7   241.2  5222.7   241.3  5242.7   242.1  5252.7   243.1  5282.7   243.9
  5332.7   247.6  5372.7   249.2  5422.7   253.1  5482.7   259.1  5539.2   260.9
#Mann= 6 , 1 , 0
 4269.30     0.2       0  4269.3     0.1       0  4773.2   0.165       0
  4953.5   0.055       0 5046.35   0.165       0  5539.2     0.2       0
Bank Sta=4953.50,5046.35
Exp/Cntr=0.3,0.1

Type RM Length L Ch R = 1 ,386349.9,532.7,532.7,532.7
BEGIN DESCRIPTION:
Cross Section Little River 64.0
END DESCRIPTION:
#Sta/Elev= 30
  4217.3   262.7  4227.3   261.9  4317.3   257.4  4367.3   254.4  4397.3   254.7
  4417.3   254.1  4674.4  249.67  4717.3   248.2  4727.3   246.6  4737.3   246.1
  4817.3   244.1  4867.3   241.4  4920.4  239.85  4932.9  236.67  4949.5  235.36
  4969.8  236.91  5001.2   236.1    5028  234.81  5076.1  238.75  5083.9     239
  5296.6   241.2  5306.6   241.6  5326.6   242.8  5336.6   243.8  5356.6   249.5
  5406.6   259.1  5416.6   260.2  5436.6   261.1  5456.6   261.9    5475     262
#Mann= 6 , 1 , 0
 4217.30     0.2       0  4217.3     0.1       0  4674.4   0.165       0
  4920.4   0.055       0  5083.9   0.165       0    5475     0.2       0
Bank Sta=4920.40,5083.90
Exp/Cntr=0.3,0.1

Type RM Length L Ch R = 1 ,385817.2,443.5,443.5,443.5
BEGIN DESCRIPTION:
Cross Section Little River 63.0
END DESCRIPTION:
#Sta/Elev= 30
  4030.3   262.5  4060.3   260.4  4230.3   252.7  4260.5  250.64  4280.3   249.8
  4390.3   248.2  4430.3   246.4  4480.3   246.2  4550.3     245  4580.3   243.5
  4600.3   245.2  4610.3   245.3  4740.3   244.7  4780.3   243.8  4820.3   241.5
  4870.3   241.2  4920.4  239.83  4932.9  236.65  4949.5  235.34  4969.8  236.89
    5028  234.79  5083.9  238.98  5347.3   241.2  5407.3   240.7  5537.3   242.5
  5617.3   248.8  5677.3   251.4  5797.3     252  6027.3   258.2  6051.4   259.5
#Mann= 6 , 1 , 0
 4030.30     0.2       0  4030.3     0.1       0  4260.5   0.165       0
  4920.4   0.055       0  5083.9   0.165       0  6051.4     0.2       0
Bank Sta=4920.40,5083.90
Exp/Cntr=0.3,0.1

Type RM Length L Ch R = 1 ,385373.7,695.8,695.8,695.8
BEGIN DESCRIPTION:
Cross Section Little River 62.0
END DESCRIPTION:
#Sta/Elev= 30
  4325.1   259.8  4345.1   258.6  4365.1   258.5  4485.1   252.3  4525.1   248.4
  4575.1   245.7  4595.1   243.6  4655.1     244  4692.5  242.57  4725.1   241.6
  4920.4   239.8  4932.9  236.62  4949.5  235.31  4969.8  236.86    5028  234.76
  5083.9  238.95  5101.3   241.2  5141.3   241.1  5151.3   239.9  5181.3   241.3
  5281.3   241.9  5321.3   241.2  5781.3   241.2  5801.3   241.9  5861.3   246.3
  5881.3   249.4  5901.3   251.5  5921.3   255.7  5931.3   256.6  6028.3   262.6
#Mann= 5 , 1 , 0
 4325.10     0.2       0  4325.1     0.1       0  4692.5   0.165       0
  4920.4   0.055       0  5083.9   0.165       0
Bank Sta=4920.40,5083.90
Exp/Cntr=0.3,0.1

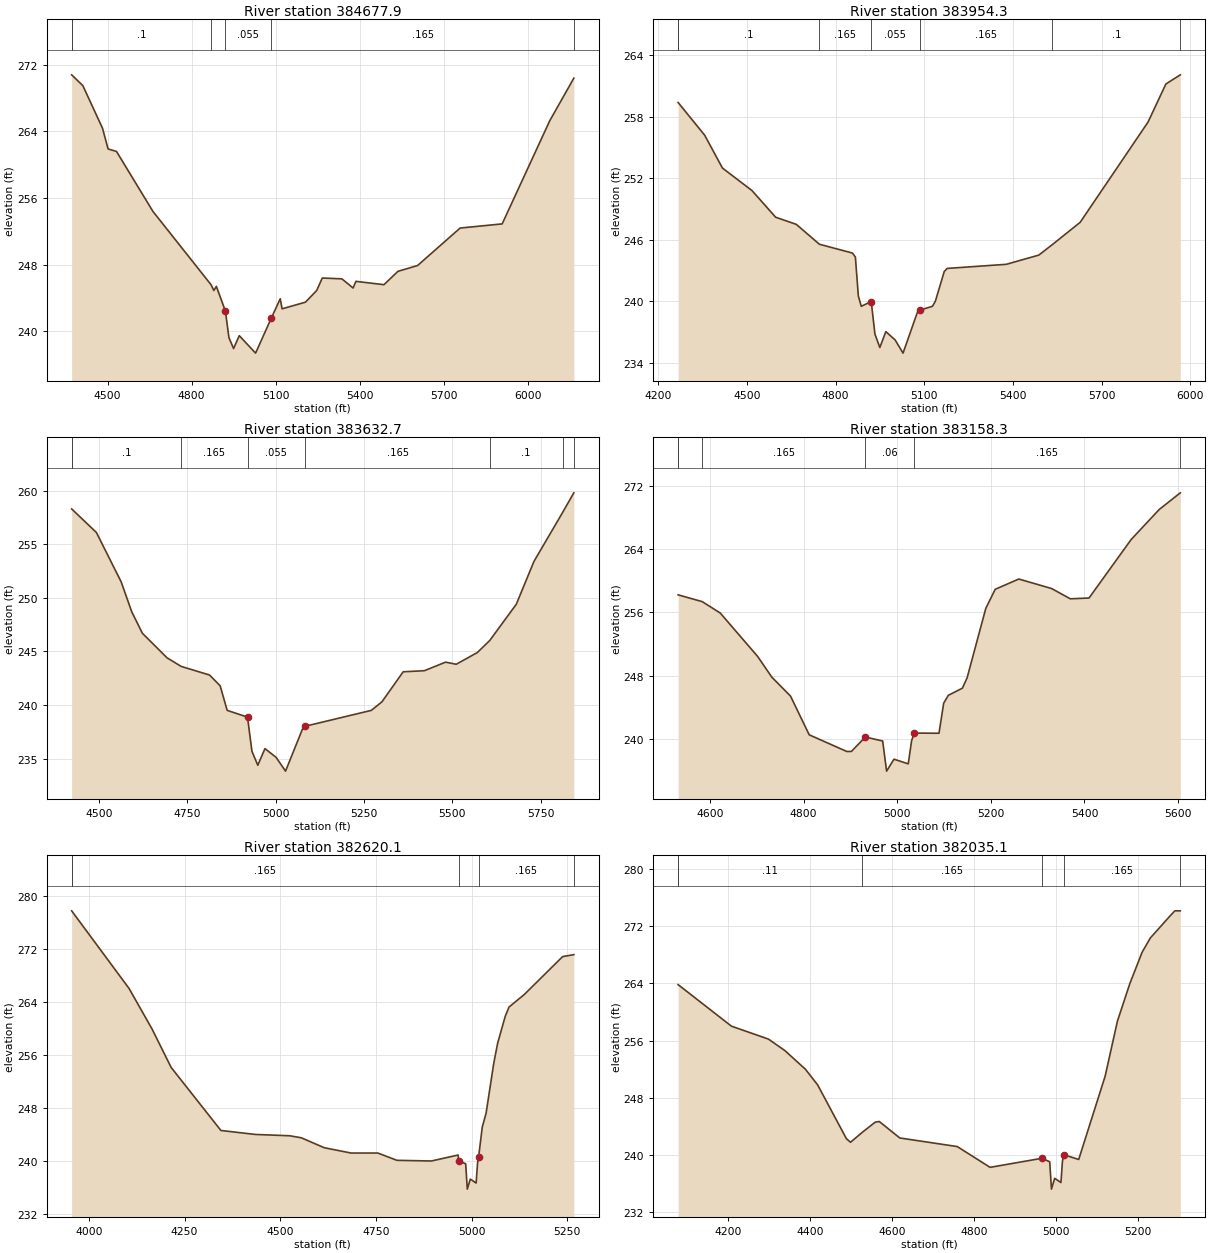
Type RM Length L Ch R = 1 ,384677.9,723.6,723.6,723.6
BEGIN DESCRIPTION:
Cross Section Little River 61.0 (CCX_WA175)
END DESCRIPTION:
#Sta/Elev= 30
  4371.7   270.8  4411.7   269.5  4481.7   264.4  4501.7   261.9  4531.7   261.6
  4661.7   254.4  4869.4  245.58  4879.1   244.9  4888.1   245.4  4920.4  242.42
  4932.9  239.24  4949.5  237.93  4969.8  239.48    5028  237.38  5083.9  241.57
    5116  243.91  5122.6   242.7    5206   243.5    5246   244.9    5266   246.4
    5336   246.3    5376   245.2    5386     246    5486   245.6    5536   247.2
    5606   247.9  5757.9   252.4  5907.9   252.9  6077.9   265.3  6163.6   270.4
#Mann= 6 , 1 , 0
 4371.70     0.2       0  4371.7     0.1       0  4869.4   0.165       0
  4920.4   0.055       0  5083.9   0.165       0  6163.6     0.2       0
Bank Sta=4920.40,5083.90
Exp/Cntr=0.3,0.1

Type RM Length L Ch R = 1 ,383954.3,321.6,321.6,321.6
BEGIN DESCRIPTION:
Cross Section Little River 60.0
END DESCRIPTION:
#Sta/Elev= 30
  4266.8   259.4  4356.8   256.2  4416.8     253  4516.8   250.8  4596.8   248.2
  4666.8   247.5    4745  245.56  4856.8   244.7  4866.8   244.3  4876.8   240.5
  4886.8   239.5  4920.4  239.97  4932.9  236.79  4949.5  235.48  4969.8  237.03
  5001.2  236.22    5028  234.93  5076.1  238.87  5083.9  239.12  5127.5   239.5
  5137.5     240  5167.5   242.9  5177.5   243.2  5377.5   243.6  5487.5   244.5
  5533.1  245.52  5627.5   247.7  5857.5   257.5  5917.5   261.2  5966.4   262.1
#Mann= 7 , 1 , 0
 4266.80     0.2       0  4266.8     0.1       0    4745   0.165       0
  4920.4   0.055       0  5083.9   0.165       0  5533.1     0.1       0
  5966.4     0.2       0
Bank Sta=4920.40,5083.90
Exp/Cntr=0.3,0.1

Type RM Length L Ch R = 1 ,383632.7,474.4,474.4,474.4
BEGIN DESCRIPTION:
Cross Section Little River 59.0
END DESCRIPTION:
#Sta/Elev= 30
  4422.9   258.3  4492.9   256.1  4562.9   251.5  4592.9   248.7  4622.9   246.7
  4692.9   244.4  4732.9   243.6  4812.9   242.8  4842.9   241.8  4862.9   239.5
  4920.4  238.87  4932.9  235.69  4949.5  234.38  4969.8  235.93  5001.2  235.12
    5028  233.83  5076.1  237.77  5083.9  238.02  5270.8   239.5  5300.8   240.3
  5360.8   243.1  5420.8   243.2  5480.8     244  5510.8   243.8  5570.8   244.9
  5605.7  246.02  5680.8   249.4  5730.8   253.4  5811.9  257.97  5843.6   259.8
#Mann= 8 , 1 , 0
 4422.90     0.2       0  4422.9     0.1       0  4732.9   0.165       0
  4920.4   0.055       0  5083.9   0.165       0  5605.7     0.1       0
  5811.9   0.165       0  5843.6     0.2       0
Bank Sta=4920.40,5083.90
Exp/Cntr=0.3,0.1

Type RM Length L Ch R = 1 ,383158.3,538.2,538.2,538.2
BEGIN DESCRIPTION:
Cross Section Little River 58.0
END DESCRIPTION:
#Sta/Elev= 30
  4532.2   258.2  4583.8  257.34  4622.2   255.9  4702.2   250.4  4732.2   247.8
  4772.2   245.4  4812.2   240.5  4892.2   238.4  4902.2   238.4    4932  240.22
    4969  239.72  4977.4  235.91  4993.2  237.42  5023.6  236.83  5030.8  239.75
  5036.4  240.72  5089.3   240.7  5099.3   244.5  5109.3   245.5  5139.3   246.4
  5149.3   247.7  5189.3   256.5  5209.3   258.9  5259.7   260.2  5329.7     259
  5369.7   257.7  5409.7   257.8  5499.7   265.2  5559.7     269  5604.6   271.1
#Mann= 6 , 1 , 0
 4532.20     0.2       0  4532.2     0.1       0  4583.8   0.165       0
    4932    0.06       0  5036.4   0.165       0  5604.6     0.2       0
Bank Sta=4932.00,5036.40
Exp/Cntr=0.3,0.1

Type RM Length L Ch R = 1 ,382620.1,585,585,585
BEGIN DESCRIPTION:
Cross Section Little River 57.0
END DESCRIPTION:
#Sta/Elev= 30
  3954.9   277.7  4104.9     266  4164.9   259.9  4214.9   254.1  4344.9   244.6
  4434.9     244  4524.9   243.8  4554.9   243.5  4614.9     242  4684.9   241.2
  4754.9   241.2  4804.9   240.1  4894.9     240  4964.9   240.9    4966  240.07
  4984.5  239.57  4988.7  235.76  4996.6  237.27  5011.8  236.68  5015.4   239.6
  5018.2  240.57  5027.8   245.1  5037.8   247.2  5057.8   254.7  5067.8   257.7
  5087.8   261.8  5097.8   263.2  5137.8   265.1  5237.8   270.8  5267.1   271.1
#Mann= 5 , 1 , 0
 3954.90     0.2       0  3954.9   0.165       0    4966    0.06       0
  5018.2   0.165       0  5267.1     0.2       0
Bank Sta=4966.00,5018.20
Exp/Cntr=0.3,0.1

Type RM Length L Ch R = 1 ,382035.1,756.5,756.5,756.5
BEGIN DESCRIPTION:
Cross Section Little River 56.0  CCX176
END DESCRIPTION:
#Sta/Elev= 30
  4079.2   263.8  4209.2     258  4299.2   256.2  4339.2   254.6  4389.2     252
  4419.2   249.8  4489.2   242.3  4499.2   241.8  4527.7  243.18  4559.2   244.6
  4569.2   244.7  4619.2   242.4  4759.2   241.2  4839.2   238.3    4966  239.57
  4984.5  239.07  4988.7  235.26  4996.6  236.77  5011.8  236.18  5015.4   239.1
  5018.2  240.07  5055.1   239.4  5119.4     251  5149.4   258.7  5179.4   263.9
  5209.4   268.3  5229.4   270.3  5279.4   273.5  5289.4   274.1  5302.6   274.1
#Mann= 6 , 1 , 0
 4079.20     0.2       0  4079.2    0.11       0  4527.7   0.165       0
    4966    0.06       0  5018.2   0.165       0  5302.6     0.2       0
Bank Sta=4966.00,5018.20
Exp/Cntr=0.3,0.1

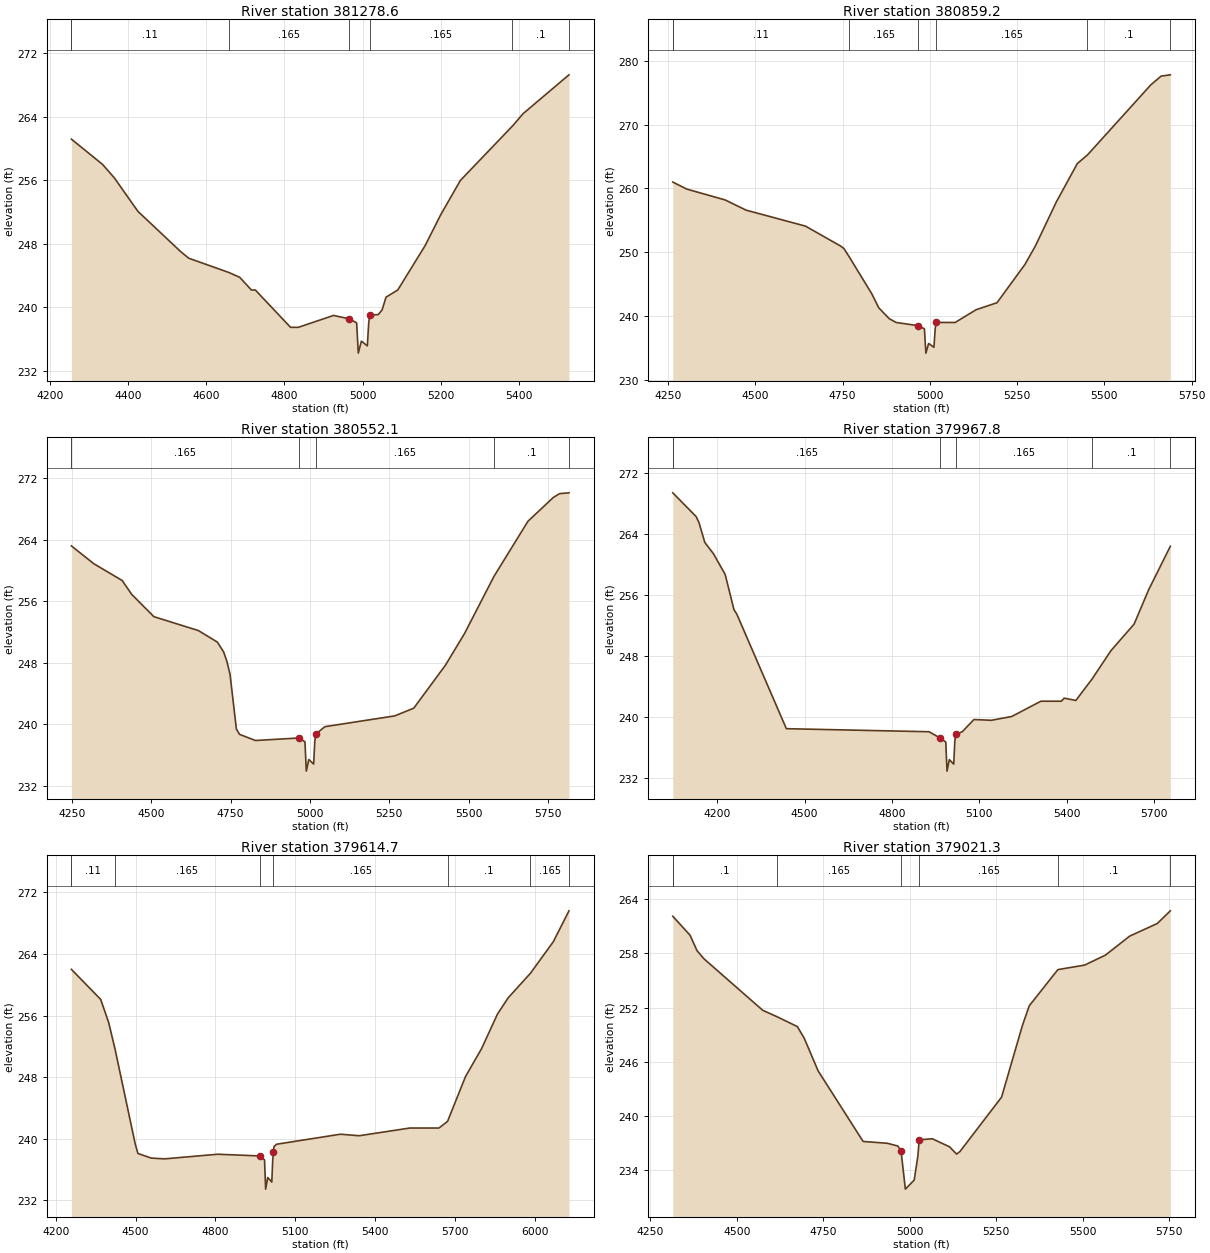
Type RM Length L Ch R = 1 ,381278.6,419.4,419.4,419.4
BEGIN DESCRIPTION:
Cross Section Little River 55.0
END DESCRIPTION:
#Sta/Elev= 30
  4255.6   261.2  4335.6     258  4365.6   256.3  4425.6   252.1  4535.6     247
  4555.6   246.2  4657.8  244.41  4685.6   243.8  4715.6   242.2  4725.6   242.2
  4815.6   237.5  4835.6   237.5  4925.6     239    4966  238.56  4984.5  238.06
  4988.7  234.25  4996.6  235.76  5011.8  235.17  5015.4  238.09  5018.2  239.06
  5039.6   239.1  5049.6   239.7  5059.6   241.3  5089.6   242.2  5159.6   247.8
  5199.6   251.7  5249.6     256  5382.7  262.85  5409.6   264.4  5527.1   269.3
#Mann= 7 , 1 , 0
 4255.60     0.2       0  4255.6    0.11       0  4657.8   0.165       0
    4966    0.06       0  5018.2   0.165       0  5382.7     0.1       0
  5527.1     0.2       0
Bank Sta=4966.00,5018.20
Exp/Cntr=0.3,0.1

Type RM Length L Ch R = 1 ,380859.2,307.1,307.1,307.1
BEGIN DESCRIPTION:
Cross Section Little River 54.0
END DESCRIPTION:
#Sta/Elev= 30
  4263.7     261  4303.7   259.9  4413.7   258.2  4473.7   256.6  4643.7   254.1
  4743.7     251  4753.7   250.6  4769.2  249.28  4833.7   243.5  4853.7   241.3
  4883.7   239.6  4903.7     239    4966  238.51  4984.5  238.01  4988.7   234.2
  4996.6  235.71  5011.8  235.12  5015.4  238.04  5018.2  239.01  5072.5     239
  5132.5     241  5192.5   242.1  5272.5   248.1  5302.5     251  5362.5   257.9
  5422.5   263.9  5451.6  265.25  5632.5   276.2  5662.5   277.6  5688.9   277.8
#Mann= 7 , 1 , 0
 4263.70     0.2       0  4263.7    0.11       0  4769.2   0.165       0
    4966    0.06       0  5018.2   0.165       0  5451.6     0.1       0
  5688.9     0.2       0
Bank Sta=4966.00,5018.20
Exp/Cntr=0.3,0.1

Type RM Length L Ch R = 1 ,380552.1,584.3,584.3,584.3
BEGIN DESCRIPTION:
Cross Section Little River 53.5
END DESCRIPTION:
#Sta/Elev= 30
  4248.3   263.2  4318.3   260.9  4408.3   258.7  4438.3   256.9  4508.3     254
  4648.3   252.2  4708.3   250.7  4728.3   249.4  4738.3   248.2  4748.3   246.5
  4768.3   239.4  4778.3   238.7  4828.5   237.9    4966  238.23  4984.5  237.73
  4988.7  233.92  4996.6  235.43  5011.8  234.84  5015.4  237.76  5018.2  238.73
  5047.4   239.7  5267.4   241.1  5327.4   242.1  5427.4   247.7  5487.4   251.8
  5580.5  259.25  5687.4   266.4  5767.4   269.5  5787.4     270  5816.7   270.1
#Mann= 6 , 1 , 0
 4248.30     0.2       0  4248.3   0.165       0    4966    0.06       0
  5018.2   0.165       0  5580.5     0.1       0  5816.7     0.2       0
Bank Sta=4966.00,5018.20
Exp/Cntr=0.3,0.1

Type RM Length L Ch R = 1 ,379967.8,353.1,353.1,353.1
BEGIN DESCRIPTION:
Cross Section Little River 53.0
END DESCRIPTION:
#Sta/Elev= 30
  4047.1   269.4  4127.1   266.3  4137.1   265.5  4157.1   262.9  4187.1   261.4
  4227.1   258.7  4257.1   254.1  4267.1   253.5  4437.1   238.5  4927.1   238.1
    4966  237.25  4984.5  236.75  4988.7  232.94  4996.6  234.45  5011.8  233.86
  5015.4  236.78  5018.2  237.75  5041.1   238.1  5081.1   239.7  5141.1   239.6
  5211.1   240.1  5311.1   242.1  5381.1   242.1  5391.1   242.5  5431.1   242.2
  5487.4  245.04  5551.1   248.7  5631.1   252.2  5681.1   256.7  5755.5   262.4
#Mann= 6 , 1 , 0
 4047.10     0.2       0  4047.1   0.165       0    4966    0.06       0
  5018.2   0.165       0  5487.4     0.1       0  5755.5     0.2       0
Bank Sta=4966.00,5018.20
Exp/Cntr=0.3,0.1

Type RM Length L Ch R = 1 ,379614.7,593.4,593.4,593.4
BEGIN DESCRIPTION:
Cross Section Little River 52.7
END DESCRIPTION:
#Sta/Elev= 30
  4258.8     262  4368.8   258.1  4398.8   255.1  4422.8  251.64  4498.8   239.3
  4508.8   238.1  4558.8   237.5  4608.8   237.4  4808.8     238    4966  237.78
  4984.5  237.28  4988.7  233.47  4996.6  234.98  5011.8  234.39  5015.4  237.31
  5018.2  238.28    5020     239    5030   239.3    5270   240.6    5340   240.4
    5530   241.4    5640   241.4  5672.4  242.27    5740   248.1    5800   251.7
    5860   256.2    5900   258.3  5983.7  261.49    6070   265.6  6128.6   269.6
#Mann= 8 , 1 , 0
 4258.80     0.2       0  4258.8    0.11       0  4422.8   0.165       0
    4966    0.06       0  5018.2   0.165       0  5672.4     0.1       0
  5983.7   0.165       0  6128.6     0.2       0
Bank Sta=4966.00,5018.20
Exp/Cntr=0.3,0.1

Type RM Length L Ch R = 1 ,379021.3,346.6,346.6,346.6
BEGIN DESCRIPTION:
Cross Section Little River 52.5
END DESCRIPTION:
#Sta/Elev= 30
  4315.2   262.1  4365.2     260  4385.2   258.3  4405.2   257.4  4575.2   251.7
  4616.5  250.99  4675.2   249.9  4695.2   248.6  4735.2     245  4865.2   237.2
  4935.2     237  4965.2   236.7  4974.8  236.16  4987.2  231.93  5012.8  232.93
  5023.3  235.57  5027.2  237.38  5065.2   237.5  5115.2   236.6  5135.2   235.8
  5145.2   236.1  5265.2   242.1  5325.2     250  5345.2   252.2  5427.9   256.2
  5505.2   256.7  5565.2   257.8  5635.2   259.9  5715.2   261.3  5752.8   262.7
#Mann= 7 , 1 , 0
 4315.20     0.2       0  4315.2     0.1       0  4616.5   0.165       0
  4974.8    0.06       0  5027.2   0.165       0  5427.9     0.1       0
  5752.8     0.2       0
Bank Sta=4974.80,5027.20
Exp/Cntr=0.3,0.1

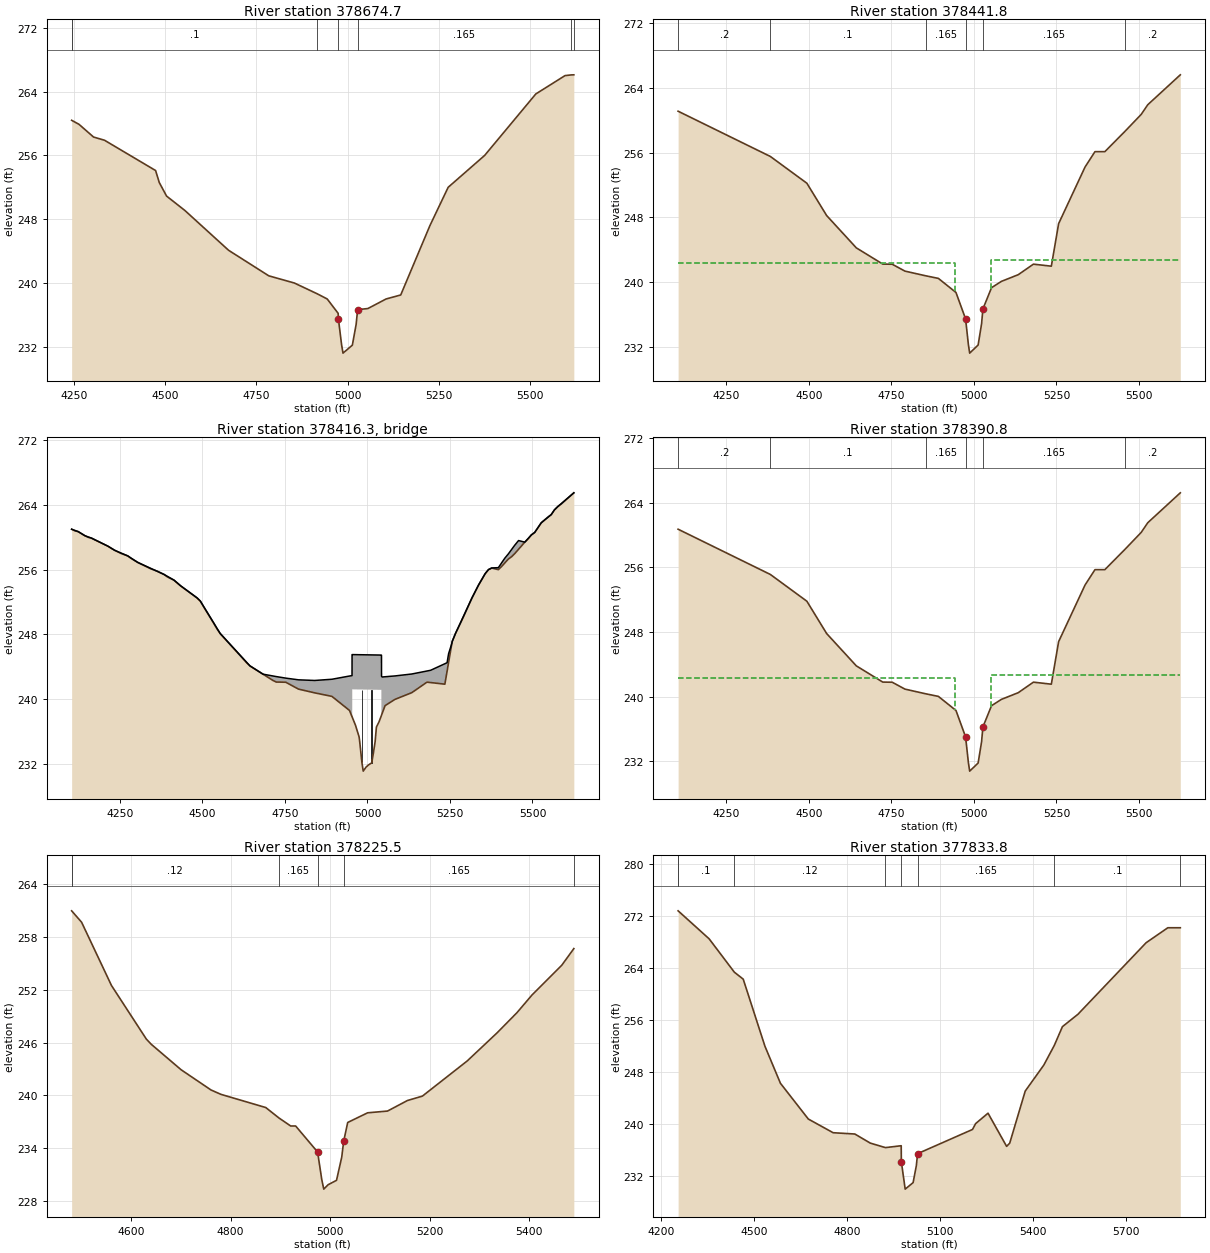
Type RM Length L Ch R = 1 ,378674.7,232.9,232.9,232.9
BEGIN DESCRIPTION:
Cross Section Little River 52.0
END DESCRIPTION:
#Sta/Elev= 30
  4243.9   260.4  4263.9   259.9  4303.9   258.3  4333.9   257.9  4473.9   254.1
  4483.9   252.6  4503.9   250.9  4553.9   249.1  4673.9   244.1  4783.9   240.9
  4853.9     240  4916.5  238.65  4943.9     238  4973.9   236.2  4974.8  235.44
  4983.2   232.3  4987.2  231.21  5012.8  232.21  5023.3  234.85  5027.2  236.66
  5055.3   236.8  5105.3     238  5145.3   238.5  5225.3   247.2  5275.3     252
  5375.3     256  5515.3   263.7  5595.3     266  5612.6  266.09  5619.5   266.1
#Mann= 7 , 1 , 0
 4243.90     0.2       0  4243.9     0.1       0  4916.5   0.165       0
  4974.8    0.06       0  5027.2   0.165       0  5612.6     0.1       0
  5619.5     0.2       0
Bank Sta=4974.80,5027.20
Exp/Cntr=0.5,0.3

Type RM Length L Ch R = 1 ,378441.8,51,51,51
BEGIN DESCRIPTION:
Upstream Section of Bridge/Culvert/Weir
END DESCRIPTION:
#Sta/Elev= 30
  4103.9  261.12  4383.2  255.53  4493.9  252.22  4553.9  248.22  4643.9  244.22
  4723.9  242.22  4752.6   242.2  4791.1  241.35  4854.2  240.77  4892.4  240.45
  4945.7  238.71  4974.8  235.44  4983.2   232.3  4987.2  231.21  5012.8  232.21
  5023.3  234.85  5027.2  236.66  5053.4   239.3  5083.3  240.08  5134.4  240.91
  5180.4  242.21  5234.6  241.96  5256.7  247.22  5336.7  254.22  5366.7  256.12
  5396.7  256.12  5457.8  258.64  5506.7  260.72  5526.7  261.92  5625.3  265.62
#Mann= 6 , 1 , 0
 4103.90     0.2       0  4383.2     0.1       0  4854.2   0.165       0
  4974.8    0.06       0  5027.2   0.165       0  5457.8     0.2       0
#XS Ineff= 2 , 0
       0  4943.3   242.3    5052       0   242.7
Bank Sta=4974.80,5027.20
Exp/Cntr=0.5,0.3

Type RM Length L Ch R = 3 ,378416.3,,,
BEGIN DESCRIPTION:
RILEY HILL RD
Structure ID: WK_LITR8
END DESCRIPTION:
Bridge Culvert--1,0,-1,-1, 0
Deck Dist Width WeirC Skew NumUp NumDn MinLoCord MaxHiCord MaxSubmerge Is_Ogee
10,31,2.6,, 60, 60,,,0.95,0,1,1,,
  4103.9  4123.9  4143.9  4163.9  4213.9  4233.9  4273.9  4303.9  4383.9  4413.9
  4433.9  4483.9  4493.9  4553.9  4643.9  4683.5  4723.9  4752.6  4791.1    4840
  4892.4  4945.7 4953.29  4953.4 4953.91    4954 5042.09  5042.2  5042.6 5042.71
  5044.6  5053.4  5083.3  5134.4  5180.4  5191.4  5234.6  5241.3  5245.8  5255.8
  5256.7  5266.7  5316.7  5336.7  5356.7  5366.7  5376.7  5396.7  5415.8  5426.7
  5445.8  5457.8  5476.7  5496.7  5506.7  5526.7  5556.7  5566.7  5576.7  5625.3
     261   260.7   260.2   259.9   258.9   258.4   257.7   256.9  255.41  254.71
  254.01  252.51  252.11  248.11  244.11  243.08  242.78  242.59  242.38   242.3
  242.45  242.85   242.9   245.5   245.5   245.5  245.44  245.44  245.42  242.82
  242.73  242.76  242.86   243.1  243.47  243.56  244.37   244.5   245.6   246.9
  247.11  248.11  252.51  254.11  255.51  256.01  256.21  256.25   257.4  257.94
     259   259.6   259.4   260.3   260.6   261.8   262.8   263.4   263.8   265.5
     261   260.7   260.2   259.9   258.9   258.4   257.7   256.9   255.4   254.7
     254   252.5   252.1   248.1   244.1  243.07   242.1  242.08  241.23  240.77
  240.33  238.59  237.83  237.82  237.76   241.2  241.14  237.96     238  238.01
  238.22  239.18  239.96  240.79  242.09  242.04  241.84  243.43  244.51  246.89
   247.1   248.1   252.5   254.1   255.5     256   256.2     256  256.81   257.3
  257.96  258.52   259.4   260.3   260.6   261.8   262.8   263.4   263.8   265.5
  4103.9  4123.9  4143.9  4163.9  4213.9  4233.9  4273.9  4303.9  4383.9  4413.9
  4433.9  4483.9  4493.9  4553.9  4643.9  4683.5  4723.9  4752.6  4791.1    4840
  4892.4  4945.7 4953.29  4953.4 4953.91    4954 5042.09  5042.2  5042.6 5042.71
  5044.6  5053.4  5083.3  5134.4  5180.4  5191.4  5234.6  5241.3  5245.8  5255.8
  5256.7  5266.7  5316.7  5336.7  5356.7  5366.7  5376.7  5396.7  5415.8  5426.7
  5445.8  5457.8  5476.7  5496.7  5506.7  5526.7  5556.7  5566.7  5576.7  5625.3
     261   260.7   260.2   259.9   258.9   258.4   257.7   256.9  255.41  254.71
  254.01  252.51  252.11  248.11  244.11  243.08  242.78  242.59  242.38   242.3
  242.45  242.85   242.9   245.5   245.5   245.5  245.44  245.44  245.42  242.82
  242.73  242.76  242.86   243.1  243.47  243.56  244.37   244.5   245.6   246.9
  247.11  248.11  252.51  254.11  255.51  256.01  256.21  256.25   257.4  257.94
     259   259.6   259.4   260.3   260.6   261.8   262.8   263.4   263.8   265.5
  260.91  260.61  260.11  259.81  258.81  258.31  257.61  256.81  255.31  254.61
  253.91  252.41  252.01  248.01  244.01  242.98  242.01  241.99  241.14  240.68
  240.24   238.5  237.74  237.73  237.67  241.11  241.05  237.87  237.91  237.92
  238.13  239.09  239.87   240.7     242  241.95  241.75  243.34  244.42   246.8
  247.01  248.01  252.41  254.01  255.41  255.91  256.11  255.91  256.72  257.21
  257.87  258.43  259.31  260.21  260.51  261.71  262.71  263.31  263.71  265.41
Pier Skew, UpSta & Num, DnSta & Num=,4983.2, 2 ,4983.2, 2 , 0 , 0 , 0 ,,
       1       1
  231.04  242.18
       1       1
  230.95  242.09
Pier Skew, UpSta & Num, DnSta & Num=,5012.8, 2 ,5012.8, 2 , 0 , 0 , 0 ,,
       1       1
  231.08  242.16
       1       1
  230.99  242.07
BR Coef= 1 , 1 , 0 ,1.25, 0 ,,,0.8,0,2,0,
Wspro=,,,, 1 ,,,, 0 ,,,, 0 ,,,,-1 ,-1 ,-1 , 0 , 0 , 0 , 0 , 0
BC Design=,, 0 ,, 0 ,,,,,,
BR U #Sta/Elev= 155
  4103.9     261  4113.9   260.8  4123.9   260.7  4143.9   260.2  4153.9     260
  4163.9   259.9  4173.9   259.7  4183.9   259.5  4193.9   259.3  4203.9   259.1
  4213.9   258.9  4233.9   258.4  4253.9     258  4273.9   257.7  4283.9   257.4
  4303.9   256.9  4313.9   256.7  4323.9   256.5  4333.9   256.3  4343.9   256.1
  4363.9   255.8  4373.9   255.6  4383.2  255.41  4383.9   255.4  4393.2  255.12
  4393.9   255.1  4403.9   254.9  4413.9   254.7  4433.9     254  4463.2  253.12
  4473.2  252.82  4483.2  252.52  4483.9   252.5  4493.2  252.13  4493.9   252.1
  4503.2  251.45  4503.9   251.4  4513.2  250.78  4523.2  250.11  4533.2  249.45
  4533.9   249.4  4543.2  248.75  4543.9   248.7  4553.2  248.14  4553.9   248.1
  4563.2  247.68  4593.9   246.3  4633.2  244.53  4633.9   244.5  4643.2  244.13
  4643.9   244.1  4653.2  243.86  4663.2   243.6  4683.5  243.07  4693.9   242.8
  4713.9   242.3  4723.9   242.1  4730.5   242.1  4752.6  242.08  4785.7  241.35
  4791.1  241.23  4835.8   240.8    4840  240.77  4854.2  240.65    4891  240.34
  4892.4  240.33  4944.9  238.62  4945.7  238.59 4953.29  237.83  4953.4  237.82
 4953.51   237.8  4953.8  237.78 4953.91  237.76    4954  237.76  4954.1  237.75
  4963.6  236.79  4974.8  235.32  4976.7  234.69  4980.7  233.07  4983.2  232.18
  4987.2  231.09  4995.9  231.59  5002.8  231.84  5008.9  232.01  5012.8  232.09
  5017.9  233.29  5023.3  234.73  5027.2  236.54  5035.2  237.19    5042  237.93
 5042.09  237.94  5042.2  237.96  5042.3  237.97 5042.49  237.99  5042.6     238
 5042.71  238.01  5044.6  238.22  5053.4  239.18  5083.3  239.96    5093  240.12
  5134.4  240.79  5141.6  240.99  5180.4  242.09  5191.4  242.04  5234.6  241.84
  5241.3  243.43  5245.8  244.51  5255.8  246.89  5256.7   247.1  5265.8  248.01
  5266.7   248.1  5275.8  248.87  5285.8  249.72  5286.7   249.8  5295.8  250.62
  5305.8  251.52  5306.7   251.6  5316.7   252.5  5325.8  253.23  5326.7   253.3
  5335.8  254.03  5336.7   254.1  5345.8  254.74  5346.7   254.8  5355.8  255.44
  5356.7   255.5  5365.8  255.96  5366.7     256  5375.8  256.18  5376.7   256.2
  5395.8  256.01  5396.7     256  5405.8  256.36  5406.7   256.4  5415.8  256.81
  5425.8  257.26  5426.7   257.3  5435.8  257.57  5436.7   257.6  5445.8  257.96
  5446.7     258  5457.8  258.52  5476.7   259.4  5486.7   259.8  5496.7   260.3
  5506.7   260.6  5516.7   261.2  5526.7   261.8  5546.7   262.5  5556.7   262.8
  5566.7   263.4  5576.7   263.8  5586.7   264.1  5616.7   265.2  5625.3   265.5
BR U #Mann= 6
 4103.90     0.2  4383.2     0.1  4854.2   0.165  4974.8    0.06  5027.2   0.165
  5457.8     0.2
BR U Banks=4974.80,5027.20
BR D #Sta/Elev= 155
  4103.9  260.91  4113.9  260.71  4123.9  260.61  4143.9  260.11  4153.9  259.91
  4163.9  259.81  4173.9  259.61  4183.9  259.41  4193.9  259.21  4203.9  259.01
  4213.9  258.81  4233.9  258.31  4253.9  257.91  4273.9  257.61  4283.9  257.31
  4303.9  256.81  4313.9  256.61  4323.9  256.41  4333.9  256.21  4343.9  256.01
  4363.9  255.71  4373.9  255.51  4383.2  255.32  4383.9  255.31  4393.2  255.03
  4393.9  255.01  4403.9  254.81  4413.9  254.61  4433.9  253.91  4463.2  253.03
  4473.2  252.73  4483.2  252.43  4483.9  252.41  4493.2  252.04  4493.9  252.01
  4503.2  251.36  4503.9  251.31  4513.2  250.69  4523.2  250.02  4533.2  249.36
  4533.9  249.31  4543.2  248.66  4543.9  248.61  4553.2  248.05  4553.9  248.01
  4563.2  247.59  4593.9  246.21  4633.2  244.44  4633.9  244.41  4643.2  244.04
  4643.9  244.01  4653.2  243.77  4663.2  243.51  4683.5  242.98  4693.9  242.71
  4713.9  242.21  4723.9  242.01  4730.5  242.01  4752.6  241.99  4785.7  241.26
  4791.1  241.14  4835.8  240.71    4840  240.68  4854.2  240.56    4891  240.25
  4892.4  240.24  4944.9  238.53  4945.7   238.5 4953.29  237.74  4953.4  237.73
 4953.51  237.71  4953.8  237.69 4953.91  237.67    4954  237.67  4954.1  237.66
  4963.6   236.7  4974.8  235.23  4976.7   234.6  4980.7  232.98  4983.2  232.09
  4987.2     231  4995.9   231.5  5002.8  231.75  5008.9  231.92  5012.8     232
  5017.9   233.2  5023.3  234.64  5027.2  236.45  5035.2   237.1    5042  237.84
 5042.09  237.85  5042.2  237.87  5042.3  237.88 5042.49   237.9  5042.6  237.91
 5042.71  237.92  5044.6  238.13  5053.4  239.09  5083.3  239.87    5093  240.03
  5134.4   240.7  5141.6   240.9  5180.4     242  5191.4  241.95  5234.6  241.75
  5241.3  243.34  5245.8  244.42  5255.8   246.8  5256.7  247.01  5265.8  247.92
  5266.7  248.01  5275.8  248.78  5285.8  249.63  5286.7  249.71  5295.8  250.53
  5305.8  251.43  5306.7  251.51  5316.7  252.41  5325.8  253.14  5326.7  253.21
  5335.8  253.94  5336.7  254.01  5345.8  254.65  5346.7  254.71  5355.8  255.35
  5356.7  255.41  5365.8  255.87  5366.7  255.91  5375.8  256.09  5376.7  256.11
  5395.8  255.92  5396.7  255.91  5405.8  256.27  5406.7  256.31  5415.8  256.72
  5425.8  257.17  5426.7  257.21  5435.8  257.48  5436.7  257.51  5445.8  257.87
  5446.7  257.91  5457.8  258.43  5476.7  259.31  5486.7  259.71  5496.7  260.21
  5506.7  260.51  5516.7  261.11  5526.7  261.71  5546.7  262.41  5556.7  262.71
  5566.7  263.31  5576.7  263.71  5586.7  264.01  5616.7  265.11  5625.3  265.41
BR D #Mann= 6
 4103.90     0.2  4383.2     0.1  4854.2   0.165  4974.8    0.06  5027.2   0.165
  5457.8     0.2
BR D Banks=4974.80,5027.20

Type RM Length L Ch R = 1 ,378390.8,165.3,165.3,165.3
BEGIN DESCRIPTION:
Downstream Section of Bridge/Culvert/Weir
END DESCRIPTION:
#Sta/Elev= 30
  4103.9  260.71  4383.2  255.12  4493.9  251.81  4553.9  247.81  4643.9  243.81
  4723.9  241.81  4752.6  241.79  4791.1  240.94  4854.2  240.36  4892.4  240.04
  4945.7   238.3  4974.8  235.03  4983.2  231.89  4987.2   230.8  5012.8   231.8
  5023.3  234.44  5027.2  236.25  5053.4  238.89  5083.3  239.67  5134.4   240.5
  5180.4   241.8  5234.6  241.55  5256.7  246.81  5336.7  253.81  5366.7  255.71
  5396.7  255.71  5457.8  258.23  5506.7  260.31  5526.7  261.51  5625.3  265.21
#Mann= 6 , 1 , 0
 4103.90     0.2       0  4383.2     0.1       0  4854.2   0.165       0
  4974.8    0.06       0  5027.2   0.165       0  5457.8     0.2       0
#XS Ineff= 2 , 0
       0  4943.3   242.3    5052       0   242.7
Bank Sta=4974.80,5027.20
Exp/Cntr=0.5,0.3

Type RM Length L Ch R = 1 ,378225.5,391.7,391.7,391.7
BEGIN DESCRIPTION:
Cross Section Little River 51.0
END DESCRIPTION:
#Sta/Elev= 30
  4480.7     261  4500.7   259.7  4560.7   252.5  4630.7   246.4  4640.7   245.8
  4700.7   242.9  4760.7   240.6  4780.7   240.1  4870.7   238.6    4897  237.42
  4920.7   236.5  4930.7   236.5  4974.8  233.54  4983.2   230.4  4987.2  229.31
  4995.9  229.81  5012.8  230.31  5023.3  232.95  5027.2  234.76  5035.3   236.9
  5075.3     238  5115.3   238.2  5155.3   239.4  5185.3   239.9  5275.3   243.9
  5335.3   247.1  5375.3   249.4  5405.3   251.4  5465.3   254.8  5489.6   256.7
#Mann= 6 , 1 , 0
 4480.70     0.2       0  4480.7    0.12       0    4897   0.165       0
  4974.8   0.058       0  5027.2   0.165       0  5489.6     0.2       0
Bank Sta=4974.80,5027.20
Exp/Cntr=0.3,0.1

Type RM Length L Ch R = 1 ,377833.8,677.3,677.3,677.3
BEGIN DESCRIPTION:
Cross Section Little River 50.5
END DESCRIPTION:
#Sta/Elev= 30
  4254.8   272.8  4354.8   268.5  4436.2  263.37  4464.8   262.3  4534.8     252
  4584.8   246.3  4674.8   240.8  4754.8   238.7  4824.8   238.5  4874.8   237.1
  4923.6  236.41  4974.4   236.7  4974.8  234.26  4987.2  230.03  5012.8  231.03
  5023.3  233.67  5027.2  235.48  5204.4   239.2  5214.4   240.1  5254.4   241.7
  5314.4   236.6  5324.4   237.1  5374.4   245.1  5434.4   249.1  5468.2  252.12
  5494.4     255  5544.4   256.9  5764.4   267.9  5834.4   270.2  5874.6   270.2
#Mann= 8 , 1 , 0
 4254.80     0.2       0  4254.8     0.1       0  4436.2    0.12       0
  4923.6   0.165       0  4974.8   0.058       0  5027.2   0.165       0
  5468.2     0.1       0  5874.6     0.2       0
Bank Sta=4974.80,5027.20
Exp/Cntr=0.3,0.1