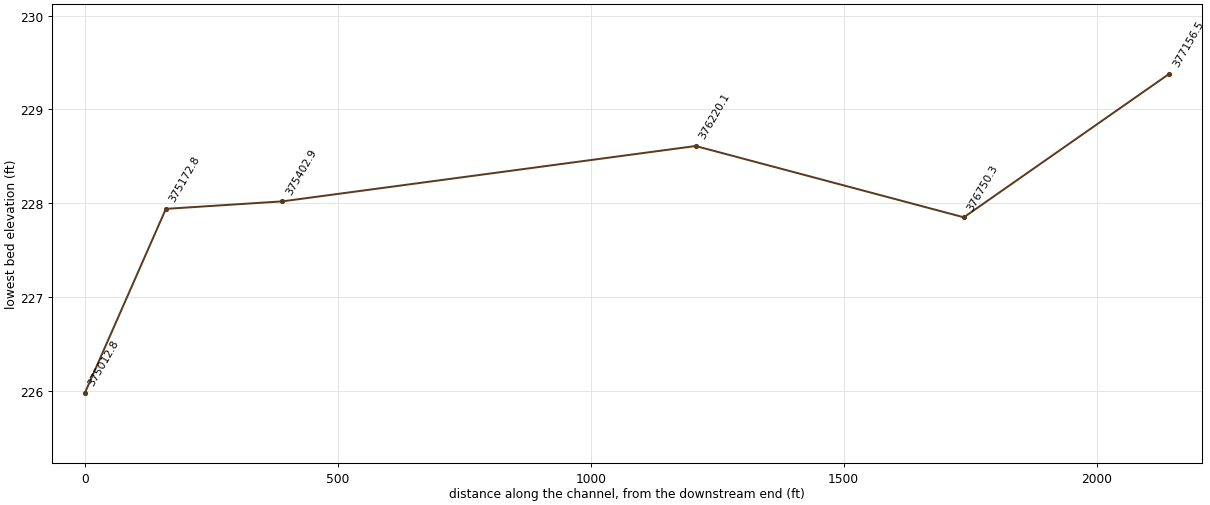
HEC-RAS study Little_River_FINAL.prj: Little River Detail Study

--- Little_River_FINAL.g01 (geometry) --- (continued)

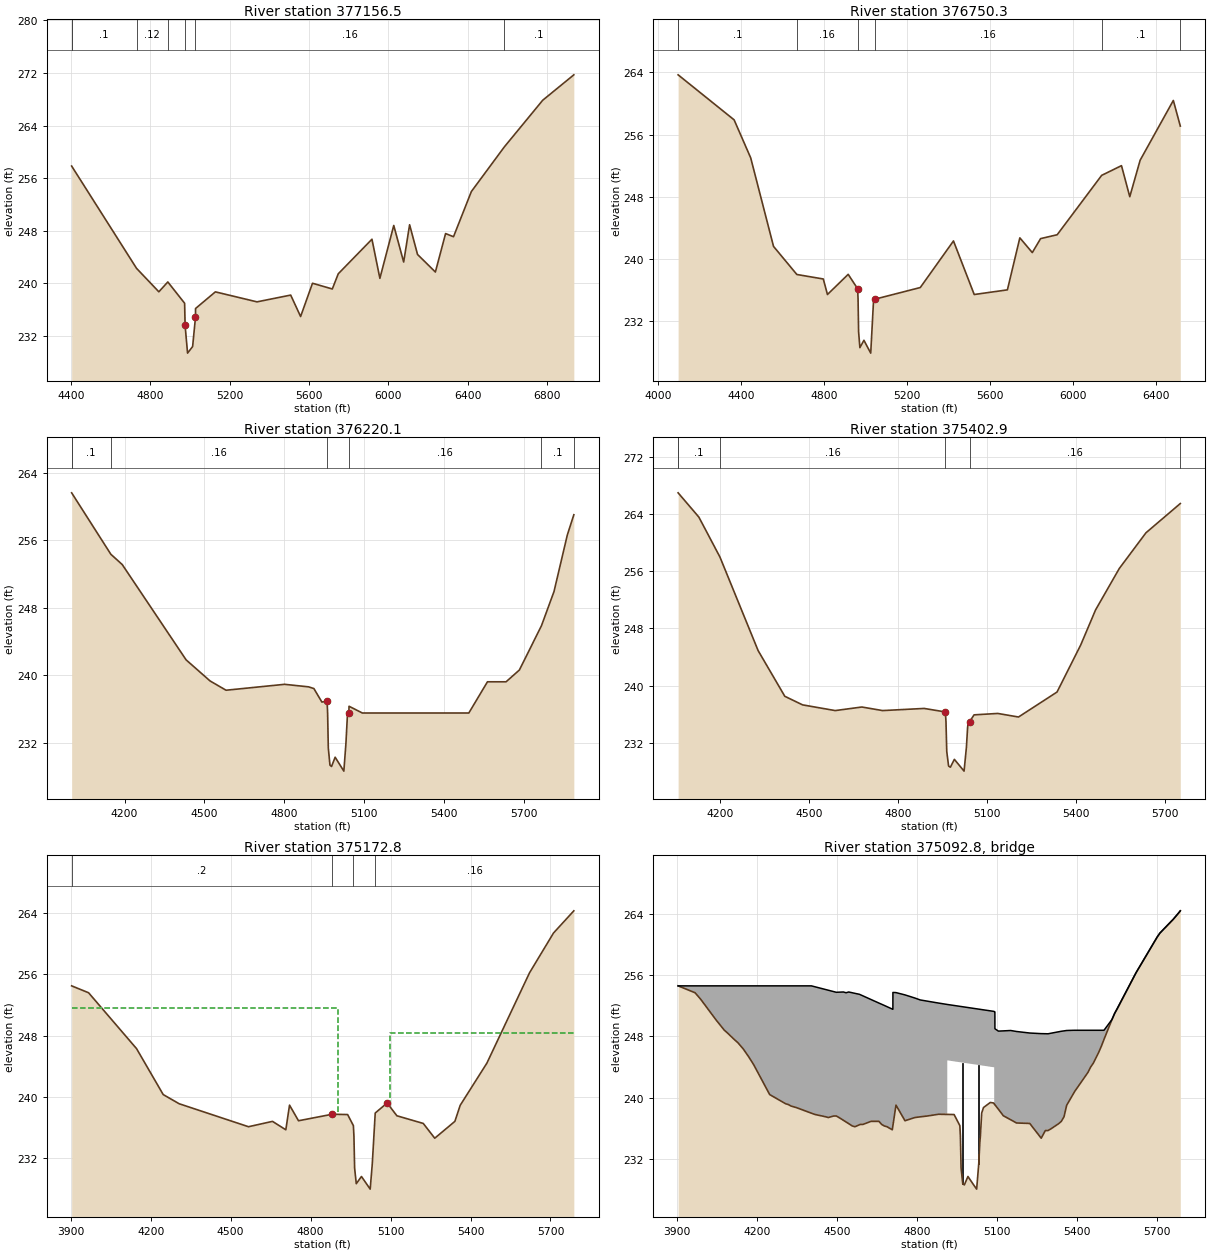
Type RM Length L Ch R = 1 ,377156.5,406.2,406.2,406.2
BEGIN DESCRIPTION:
Cross Section Little River 50.0
END DESCRIPTION:
#Sta/Elev= 30
  4402.4  257.84  4729.8  242.28  4842.4  238.71  4887.6  240.21  4972.4  236.97
  4974.8  233.61  4987.2  229.38  5012.8  230.38  5027.2  234.83  5027.6  236.17
  5127.6   238.7  5337.6  237.18  5507.6  238.21  5557.6  234.95  5617.6  240.01
  5717.6  239.14  5747.6  241.45  5917.6  246.71  5957.6  240.76  6027.6   248.8
  6077.6  243.24  6107.6  248.91  6147.6  244.39  6237.6  241.72  6289.1  247.57
  6329.1  247.09  6419.1  253.96  6585.4  260.75  6779.1  267.85  6936.2  271.72
#Mann= 7 , 1 , 0
 4402.40     0.2       0  4402.4     0.1       0  4729.8    0.12       0
  4887.6    0.16       0  4974.8   0.058       0  5027.2    0.16       0
  6585.4     0.1       0
Bank Sta=4974.80,5027.20
Exp/Cntr=0.3,0.1

Type RM Length L Ch R = 1 ,376750.3,530.2,530.2,530.2
BEGIN DESCRIPTION:
Cross Section Little River 49.5
END DESCRIPTION:
#Sta/Elev= 30
    4095   263.7    4365   257.9    4445     253    4555   241.6  4667.4  237.98
    4795   237.4    4815   235.4    4915     238  4960.6  236.14  4962.6  234.76
  4965.2  230.59  4971.4  228.56  4990.9   229.5  5023.6  227.85  5037.4  234.72
  5042.5  234.79  5262.6   236.3  5422.6   242.3  5522.6   235.4  5682.6     236
  5742.6   242.7  5802.6   240.8  5842.6   242.6  5922.6   243.1  6137.1  250.75
  6232.6     252  6272.6     248  6322.6   252.7  6482.6   260.4  6516.2   257.1
#Mann= 7 , 1 , 0
 4095.00     0.2       0    4095     0.1       0  4667.4    0.16       0
  4960.6   0.045       0  5042.5    0.16       0  6137.1     0.1       0
  6516.2     0.2       0
Bank Sta=4960.60,5042.50
Exp/Cntr=0.3,0.1

Type RM Length L Ch R = 1 ,376220.1,817.2,817.2,817.2
BEGIN DESCRIPTION:
Cross Section Little River 49.0
END DESCRIPTION:
#Sta/Elev= 30
    4001   261.6  4148.2  254.32    4191   253.1    4431   241.8    4521   239.3
    4581   238.2    4801   238.9    4891   238.6    4911   238.4    4941   236.8
  4960.6   236.9  4962.6  235.52  4965.2  231.35  4971.4  229.32  4977.4  229.16
  4990.9  230.26  5023.6  228.61  5031.5  231.94  5037.4  235.48  5042.5  235.55
  5043.1   236.3  5093.1   235.5  5493.1   235.5  5563.1   239.2  5633.1   239.2
  5683.1   240.6  5765.9  245.84  5813.1   249.9  5863.1   256.6  5887.6     259
#Mann= 7 , 1 , 0
 4001.00     0.2       0    4001     0.1       0  4148.2    0.16       0
  4960.6   0.045       0  5042.5    0.16       0  5765.9     0.1       0
  5887.6     0.2       0
Bank Sta=4960.60,5042.50
Exp/Cntr=0.3,0.1

Type RM Length L Ch R = 1 ,375402.9,230.1,230.1,230.1
BEGIN DESCRIPTION:
Cross Section Little River 48.0
END DESCRIPTION:
#Sta/Elev= 30
  4058.8     267  4128.8   263.6  4199.9  258.01  4328.8   244.9  4418.8   238.5
  4478.8   237.3  4588.8   236.5  4678.8     237  4748.8   236.5  4888.8   236.8
  4960.6  236.31  4962.6  234.93  4965.2  230.76  4971.4  228.73  4977.4  228.57
  4990.9  229.67  5023.6  228.02  5031.5  231.35  5035.6  234.15  5037.4  234.89
  5042.5  234.96  5057.3   235.9  5137.3   236.1  5207.3   235.6  5337.3   239.1
  5417.3   245.7  5467.3   250.6  5547.3   256.4  5637.3   261.4  5753.2   265.5
#Mann= 6 , 1 , 0
 4058.80     0.2       0  4058.8     0.1       0  4199.9    0.16       0
  4960.6   0.045       0  5042.5    0.16       0  5753.2     0.2       0
Bank Sta=4960.60,5042.50
Exp/Cntr=0.5,0.3

Type RM Length L Ch R = 1 ,375172.8,160,160,160
BEGIN DESCRIPTION:
Upstream Section of Bridge/Culvert/Weir
END DESCRIPTION:
#Sta/Elev= 30
  3903.6  254.49  3967.1  253.59  4147.1  246.29  4247.1  240.29  4307.1  239.09
  4567.1  236.09  4657.1  236.79  4707.1  235.69    4721  238.91  4754.7  236.87
  4881.1  237.72    4939  237.68  4960.6  236.23  4962.6  234.85  4965.2  230.68
  4971.4  228.65  4990.9  229.59  5023.6  227.94  5031.5  231.27  5042.5  237.88
  5087.1  239.19  5123.8  237.52  5222.7  236.52  5265.8  234.59  5341.3  236.79
  5361.3  238.89  5461.3  244.39  5621.3  256.19  5711.3  261.39  5787.6  264.29
#Mann= 4 , 1 , 0
 3903.60     0.2       0  4881.1    0.16       0  4960.6   0.045       0
  5042.5    0.16       0
#XS Ineff= 2 , 0
       0  4903.2   251.6  5097.1       0   248.3
Bank Sta=4881.10,5087.10
Exp/Cntr=0.5,0.3

Type RM Length L Ch R = 3 ,375092.8,,,
BEGIN DESCRIPTION:
US-64
Structure ID: WK_LITR7
END DESCRIPTION:
Bridge Culvert--1,0,-1,-1, 0
Deck Dist Width WeirC Skew NumUp NumDn MinLoCord MaxHiCord MaxSubmerge Is_Ogee
10,140,2.6,, 60, 60,,,0.95,0,1,1,,
  3903.6  3967.1  3987.1  4077.1  4127.1  4147.1  4187.1  4247.1  4327.1  4403.6
  4467.1  4497.1  4523.6  4533.6  4543.6  4567.1  4583.6  4597.1  4627.1  4657.1
  4667.1  4707.1 4709.29  4709.4    4721  4754.7  4791.8  4811.9  4881.1 4913.31
  4913.4  4913.5 5089.39  5089.5    5092 5092.11    5105  5123.8  5151.3  5173.1
  5222.7  5265.8  5281.3  5291.3  5341.3  5351.3  5361.3  5391.3  5441.3  5451.3
  5461.3  5481.3  5501.3  5531.3  5541.3  5621.3  5701.3  5711.3  5761.3  5787.6
   254.6   254.6   254.6   254.6   254.6   254.6   254.6   254.6   254.6   254.6
  254.03  253.76   253.8   253.7   253.8  253.62   253.5  253.29  252.82  252.35
   252.2  251.57  251.54  253.74  253.72  253.42  253.01  252.76  252.35  252.17
  252.17  252.17  251.26  251.25   251.2     249  248.69  248.72  248.77  248.64
  248.44  248.36  248.35  248.34  248.67  248.72  248.77   248.8   248.8   248.8
   248.8   248.8   248.8  250.21  251.01   256.3     261   261.5   263.3   264.4
   254.6   253.7   252.9   248.8   247.2   246.4   244.3   240.4   238.9  237.97
   237.4   237.6  237.04  236.82   236.6   236.2  236.45   236.5   236.9   236.9
   236.5   235.8  236.31  236.33  239.02  236.98   237.4  237.49  237.83  237.81
  244.87  244.87  243.96  239.19  239.08  239.07  238.49  237.63  237.11  236.69
  236.63   234.7   235.7   235.7   236.9   237.5     239   240.8   243.3     244
   244.5   245.9   247.6   250.2     251   256.3     261   261.5   263.3   264.4
  3903.6  3967.1  3987.1  4077.1  4127.1  4147.1  4187.1  4247.1  4327.1  4403.6
  4467.1  4497.1  4523.6  4533.6  4543.6  4567.1  4583.6  4597.1  4627.1  4657.1
  4667.1  4707.1 4709.29  4709.4    4721  4754.7  4791.8  4811.9  4881.1 4913.31
  4913.4  4913.5 5089.39  5089.5    5092 5092.11    5105  5123.8  5151.3  5173.1
  5222.7  5265.8  5281.3  5291.3  5341.3  5351.3  5361.3  5391.3  5441.3  5451.3
  5461.3  5481.3  5501.3  5531.3  5541.3  5621.3  5701.3  5711.3  5761.3  5787.6
   254.6   254.6   254.6   254.6   254.6   254.6   254.6   254.6   254.6   254.6
  254.03  253.76   253.8   253.7   253.8  253.62   253.5  253.29  252.82  252.35
   252.2  251.57  251.54  253.74  253.72  253.42  253.01  252.76  252.35  252.17
  252.17  252.17  251.26  251.25   251.2     249  248.69  248.72  248.77  248.64
  248.44  248.36  248.35  248.34  248.67  248.72  248.77   248.8   248.8   248.8
   248.8   248.8   248.8  250.21  251.01   256.3     261   261.5   263.3   264.4
  252.51  251.61  250.81  246.71  245.11  244.31  242.21  238.31  236.81  235.88
  235.31  235.51  234.95  234.73  234.51  234.11  234.36  234.41  234.81  234.81
  234.41  233.71  234.22  234.24  236.93  234.89  235.31   235.4  235.74  235.72
  242.78  242.78  241.87   237.1  236.99  236.98   236.4  235.54  235.02   234.6
  234.54  232.61  233.61  233.61  234.81  235.41  236.91  238.71  241.21  241.91
  242.41  243.81  245.51  248.11  248.91  254.21  258.91  259.41  261.21  262.31
Pier Skew, UpSta & Num, DnSta & Num=,4971.4, 2 ,4971.4, 2 , 0 , 0 , 0 ,,
       3       3
  227.72  245.58
       3       3
  225.63  243.49
Pier Skew, UpSta & Num, DnSta & Num=,5031.5, 2 ,5031.5, 2 , 0 , 0 , 0 ,,
       3       3
  229.75  245.27
       3       3
  227.66  243.18
BR Coef= 1 , 1 , 0 ,1.25, 0 ,,,0.8,0,2,0,
Wspro=,,,, 1 ,,,, 0 ,,,, 0 ,,,,-1 ,-1 ,-1 , 0 , 0 , 0 , 0 , 0
BC Design=,, 0 ,, 0 ,,,,,,
BR U #Sta/Elev= 122
  3903.6   254.6  3967.1   253.7  3977.1   253.3  3987.1   252.9  4047.1   250.1
  4077.1   248.8  4087.1   248.5  4117.1   247.5  4127.1   247.2  4137.1   246.8
  4147.1   246.4  4157.1   245.9  4167.1   245.4  4187.1   244.3  4247.1   240.4
  4257.1   240.2  4307.1   239.2  4317.1   239.1  4327.1   238.9  4347.1   238.7
  4403.6  237.97  4417.1   237.8  4457.1   237.5  4467.1   237.4  4487.1   237.6
  4497.1   237.6  4503.6  237.47  4507.1   237.4  4513.6  237.26  4523.6  237.04
  4533.6  236.82  4543.6   236.6  4557.1   236.3  4567.1   236.2  4583.6  236.45
  4587.1   236.5  4597.1   236.5  4627.1   236.9  4637.1   236.9  4657.1   236.9
  4667.1   236.5  4677.1   236.3  4687.1   236.2  4707.1   235.8 4709.29  236.31
  4709.4  236.33 4709.51  236.36    4719  238.56    4721  239.02  4754.7  236.98
  4765.2   237.1  4791.8   237.4  4811.9  237.49  4836.2  237.59    4859  237.71
  4881.1  237.83  4907.6  237.81  4913.2  237.81 4913.31  237.81  4913.4  237.81
  4913.5  237.81    4939  237.79  4960.6  236.34  4962.6  234.96  4965.2  230.79
  4971.4  228.76  4977.4   228.6  4990.9   229.7  5011.4  228.65  5023.6  228.05
  5031.5  231.38  5035.6  234.18  5037.4  234.92  5042.5  237.99  5049.4  238.71
  5074.8  239.37  5087.1   239.3  5089.2   239.2  5089.3   239.2 5089.39   239.2
  5089.5  239.19 5091.89  239.08    5092  239.08 5092.11  239.07    5105  238.49
  5123.8  237.63  5151.3  237.11  5173.1  236.69  5196.7  236.66  5222.7  236.63
  5245.3  235.62  5265.8   234.7  5281.3   235.7  5291.3   235.7  5292.2  235.72
  5301.3   235.9  5326.6  236.49  5331.3   236.6  5341.3   236.9  5351.3   237.5
  5361.3     239  5366.8  239.33  5391.3   240.8  5401.3   241.3  5431.3   242.8
  5441.3   243.3  5451.3     244  5461.3   244.5  5471.3   245.2  5481.3   245.9
  5491.3   246.7  5501.3   247.6  5531.3   250.2  5541.3     251  5551.3   251.6
  5566.8  252.64  5621.3   256.3  5701.3     261  5711.3   261.5  5761.3   263.3
  5781.3   264.1  5787.6   264.4
BR U #Mann= 4
 3903.60     0.2  4881.1    0.16  4960.6   0.045  5042.5    0.16
BR U Banks=4881.10,5087.10
BR D #Sta/Elev= 122
  3903.6  252.51  3967.1  251.61  3977.1  251.21  3987.1  250.81  4047.1  248.01
  4077.1  246.71  4087.1  246.41  4117.1  245.41  4127.1  245.11  4137.1  244.71
  4147.1  244.31  4157.1  243.81  4167.1  243.31  4187.1  242.21  4247.1  238.31
  4257.1  238.11  4307.1  237.11  4317.1  237.01  4327.1  236.81  4347.1  236.61
  4403.6  235.88  4417.1  235.71  4457.1  235.41  4467.1  235.31  4487.1  235.51
  4497.1  235.51  4503.6  235.38  4507.1  235.31  4513.6  235.17  4523.6  234.95
  4533.6  234.73  4543.6  234.51  4557.1  234.21  4567.1  234.11  4583.6  234.36
  4587.1  234.41  4597.1  234.41  4627.1  234.81  4637.1  234.81  4657.1  234.81
  4667.1  234.41  4677.1  234.21  4687.1  234.11  4707.1  233.71 4709.29  234.22
  4709.4  234.24 4709.51  234.27    4719  236.47    4721  236.93  4754.7  234.89
  4765.2  235.01  4791.8  235.31  4811.9   235.4  4836.2   235.5    4859  235.62
  4881.1  235.74  4907.6  235.72  4913.2  235.72 4913.31  235.72  4913.4  235.72
  4913.5  235.72    4939   235.7  4960.6  234.25  4962.6  232.87  4965.2   228.7
  4971.4  226.67  4977.4  226.51  4990.9  227.61  5011.4  226.56  5023.6  225.96
  5031.5  229.29  5035.6  232.09  5037.4  232.83  5042.5   235.9  5049.4  236.62
  5074.8  237.28  5087.1  237.21  5089.2  237.11  5089.3  237.11 5089.39  237.11
  5089.5   237.1 5091.89  236.99    5092  236.99 5092.11  236.98    5105   236.4
  5123.8  235.54  5151.3  235.02  5173.1   234.6  5196.7  234.57  5222.7  234.54
  5245.3  233.53  5265.8  232.61  5281.3  233.61  5291.3  233.61  5292.2  233.63
  5301.3  233.81  5326.6   234.4  5331.3  234.51  5341.3  234.81  5351.3  235.41
  5361.3  236.91  5366.8  237.24  5391.3  238.71  5401.3  239.21  5431.3  240.71
  5441.3  241.21  5451.3  241.91  5461.3  242.41  5471.3  243.11  5481.3  243.81
  5491.3  244.61  5501.3  245.51  5531.3  248.11  5541.3  248.91  5551.3  249.51
  5566.8  250.55  5621.3  254.21  5701.3  258.91  5711.3  259.41  5761.3  261.21
  5781.3  262.01  5787.6  262.31
BR D #Mann= 4
 3903.60     0.2  4881.1    0.16  4960.6   0.045  5042.5    0.16
BR D Banks=4881.10,5087.10

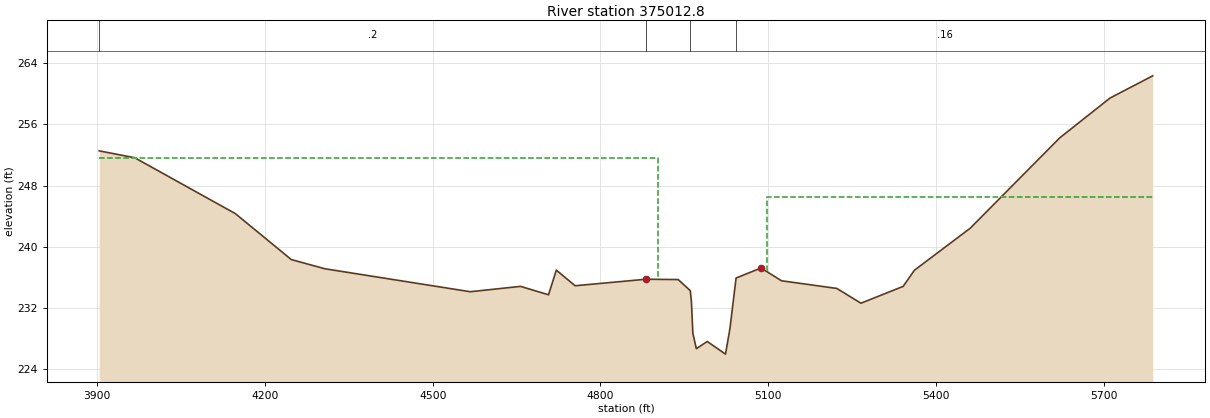
Type RM Length L Ch R = 1 ,375012.8,55.4,55.4,55.4
BEGIN DESCRIPTION:
Downstream Section of Bridge/Culvert/Weir
END DESCRIPTION:
#Sta/Elev= 30
  3903.6  252.53  3967.1  251.63  4147.1  244.33  4247.1  238.33  4307.1  237.13
  4567.1  234.13  4657.1  234.83  4707.1  233.73    4721  236.95  4754.7  234.91
  4881.1  235.76    4939  235.72  4960.6  234.27  4962.6  232.89  4965.2  228.72
  4971.4  226.69  4990.9  227.63  5023.6  225.98  5031.5  229.31  5042.5  235.92
  5087.1  237.23  5123.8  235.56  5222.7  234.56  5265.8  232.63  5341.3  234.83
  5361.3  236.93  5461.3  242.43  5621.3  254.23  5711.3  259.43  5787.6  262.33
#Mann= 4 , 1 , 0
 3903.60     0.2       0  4881.1    0.16       0  4960.6   0.045       0
  5042.5    0.16       0
#XS Ineff= 2 , 0
       0  4903.2   251.6  5097.1       0   246.5
Bank Sta=4881.10,5087.10
Exp/Cntr=0.5,0.3