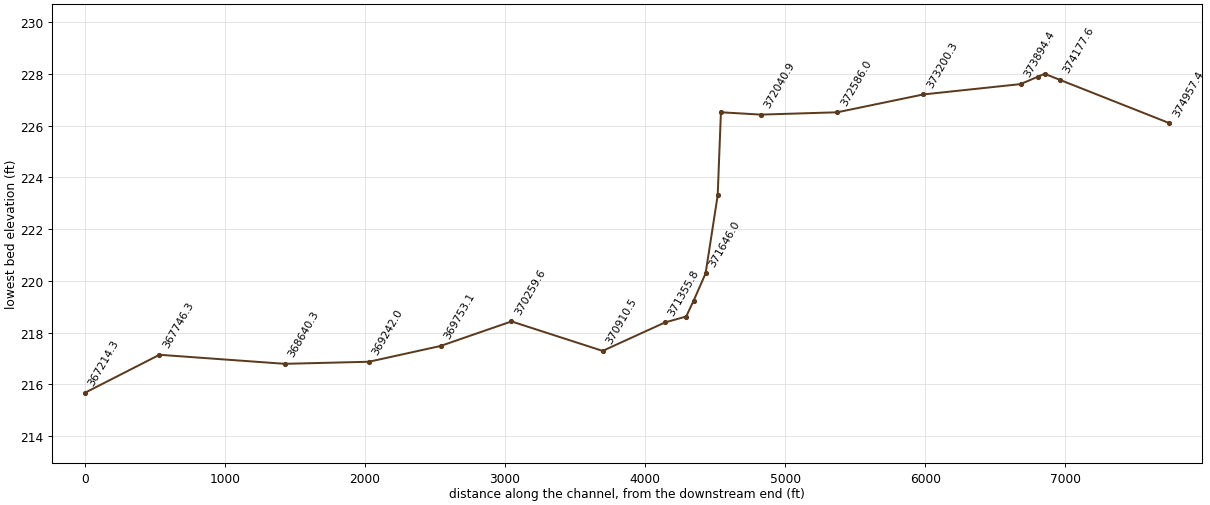
HEC-RAS study Little_River_FINAL.prj: Little River Detail Study

--- Little_River_FINAL.g01 (geometry) --- (continued)

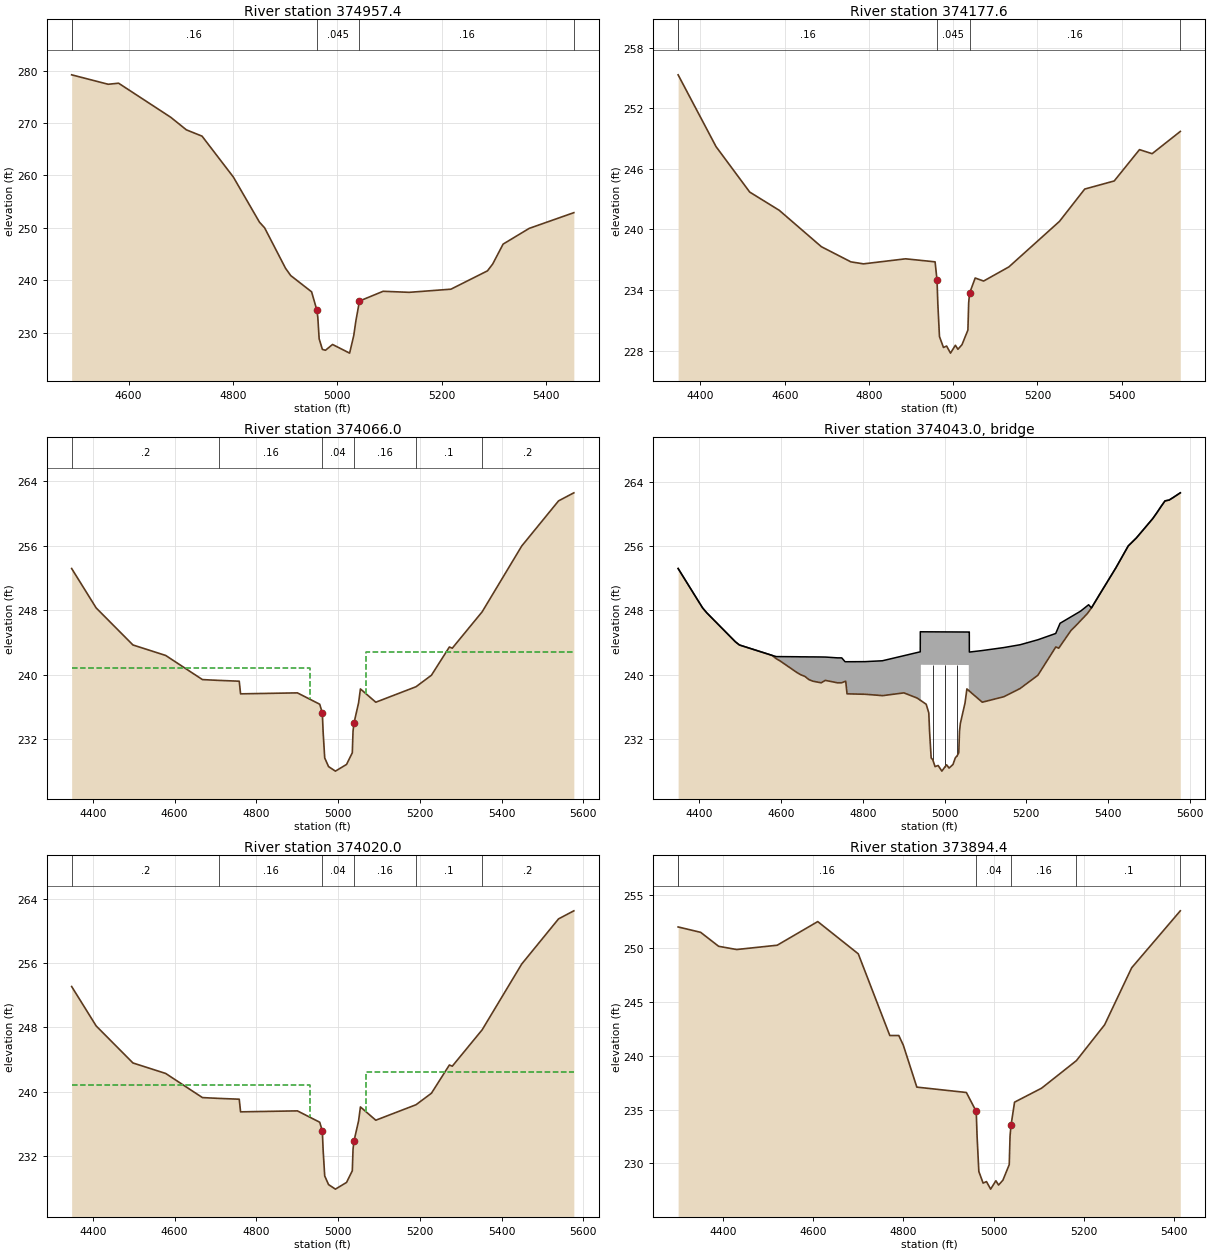
Type RM Length L Ch R = 1 ,374957.4,779.8,779.8,779.8
BEGIN DESCRIPTION:
Cross Section Little River 47.5
END DESCRIPTION:
#Sta/Elev= 30
  4490.7   279.2  4560.7   277.4  4580.7   277.6  4680.7   271.1  4710.7   268.7
  4740.7   267.5  4800.7   259.7  4850.7   251.1  4860.7     250  4900.7   242.3
  4910.7   240.9  4950.7   237.8  4960.6  234.39  4962.6  233.01  4965.2  228.84
  4971.4  226.81  4977.4  226.65  4990.9  227.75  5023.6   226.1  5031.5  229.43
  5035.6  232.23  5042.5  236.04  5087.9   237.9  5137.9   237.7  5217.9   238.3
  5287.9   241.8  5297.9   243.1  5317.9   246.9  5367.9   249.9  5453.5   252.9
#Mann= 5 , 1 , 0
 4490.70     0.2       0  4490.7    0.16       0  4960.6   0.045       0
  5042.5    0.16       0  5453.5     0.2       0
Bank Sta=4960.60,5042.50
Exp/Cntr=0.3,0.1

Type RM Length L Ch R = 1 ,374177.6,111.6,111.6,111.6
BEGIN DESCRIPTION:
Cross Section Little River 47.0
END DESCRIPTION:
#Sta/Elev= 30
  4346.9   255.3  4436.9   248.2  4516.9   243.7  4586.9   241.9  4686.9   238.3
  4756.9   236.8  4786.9   236.6  4886.9   237.1  4956.9   236.8  4961.5     235
  4963.4  232.68  4967.3  229.41  4976.8  228.33  4984.3  228.47  4993.5  227.77
  5005.1  228.55  5011.1  228.15  5020.7   228.6  5034.8  230.05  5036.6  232.72
  5038.7  233.69  5052.1   235.2  5072.1   234.9  5132.1   236.3  5252.1   240.8
  5312.1     244  5382.1   244.8  5442.1   247.9  5472.1   247.5    5539   249.7
#Mann= 5 , 1 , 0
 4346.90     0.2       0  4346.9    0.16       0  4961.5   0.045       0
  5038.7    0.16       0    5539     0.2       0
Bank Sta=4961.50,5038.70
Exp/Cntr=0.5,0.3

Type RM Length L Ch R = 1 ,374066.0,46,46,46
BEGIN DESCRIPTION:
Upstream Section of Bridge/Culvert/Weir
END DESCRIPTION:
#Sta/Elev= 30
  4348.2  253.18  4408.2  248.28  4498.2  243.68  4578.2  242.38  4668.2  239.38
  4708.5  239.28  4758.2  239.18  4761.5  237.61  4900.5  237.73  4955.1  236.32
  4961.5  235.24  4963.4  232.92  4967.3  229.65  4976.8  228.57  4993.5  228.01
  5020.7  228.84  5034.8  230.29  5036.6  232.96  5038.7  233.93  5050.1  236.47
  5054.7  238.22  5092.3  236.57  5190.6  238.49  5228.4  239.92  5272.3  243.43
  5279.4  243.28  5352.5   247.8  5449.4  255.98  5539.4  261.58  5576.8  262.58
#Mann= 6 , 1 , 0
 4348.20     0.2       0  4708.5    0.16       0  4961.5    0.04       0
  5038.7    0.16       0  5190.6     0.1       0  5352.5     0.2       0
#XS Ineff= 2 , 0
       0  4932.1   240.8  5069.2       0   242.8
Bank Sta=4961.50,5038.70
Exp/Cntr=0.5,0.3

Type RM Length L Ch R = 3 ,374043.0,,,
BEGIN DESCRIPTION:
GREEN PACE RD
Structure ID: WK_LITR5
END DESCRIPTION:
Bridge Culvert--1,0,-1,-1, 0
Deck Dist Width WeirC Skew NumUp NumDn MinLoCord MaxHiCord MaxSubmerge Is_Ogee
10,26,2.6,, 49, 49,,,0.95,0,1,1,,
  4348.2  4408.2  4418.2  4488.2  4498.2  4578.2  4588.2  4638.2  4648.2  4658.2
  4668.2  4678.2  4698.2  4708.5  4738.2  4748.5  4756.6  4758.2  4761.5  4804.8
  4847.9  4900.5  4932.8 4940.59  4940.7 4942.01  4942.1 5059.29  5059.4  5060.6
 5060.71  5092.3    5145  5184.9  5228.4    5272  5279.4  5282.7  5309.4  5332.7
  5352.5  5359.4  5419.4  5449.4  5469.4  5509.4  5539.4  5549.4  5576.8
   253.2   248.3   247.7   244.1   243.7  242.41  242.26  242.24  242.23  242.23
  242.22  242.22  242.21   242.2   242.1   242.1  241.62  241.62  241.62  241.63
  241.74  242.37  242.76  242.85  245.35  245.34  245.34  245.31  245.31  245.32
  242.82  243.01  243.38  243.73  244.35  245.13  246.01   246.4   247.2   247.9
   248.7   248.3   253.3     256     257   259.4   261.6   261.7   262.6
   253.2   248.3   247.7   244.1   243.7   242.4     242   240.3     240   239.8
   239.4   239.2     239   239.3     239  239.01  239.17   239.2  237.63  237.58
  237.41  237.75  237.11  236.84  236.84  236.79  241.24  241.21  238.03  237.98
  237.98  236.59  237.27  238.29  239.94  243.43   243.3  243.54   245.5  246.71
  247.82   248.3   253.3     256     257   259.4   261.6   261.7   262.6
  4348.2  4408.2  4418.2  4488.2  4498.2  4578.2  4588.2  4638.2  4648.2  4658.2
  4668.2  4678.2  4698.2  4708.5  4738.2  4748.5  4756.6  4758.2  4761.5  4804.8
  4847.9  4900.5  4932.8 4940.59  4940.7 4942.01  4942.1 5059.29  5059.4  5060.6
 5060.71  5092.3    5145  5184.9  5228.4    5272  5279.4  5282.7  5309.4  5332.7
  5352.5  5359.4  5419.4  5449.4  5469.4  5509.4  5539.4  5549.4  5576.8
   253.2   248.3   247.7   244.1   243.7  242.41  242.26  242.24  242.23  242.23
  242.22  242.22  242.21   242.2   242.1   242.1  241.62  241.62  241.62  241.63
  241.74  242.37  242.76  242.85  245.35  245.34  245.34  245.31  245.31  245.32
  242.82  243.01  243.38  243.73  244.35  245.13  246.01   246.4   247.2   247.9
   248.7   248.3   253.3     256     257   259.4   261.6   261.7   262.6
  253.09  248.19  247.59  243.99  243.59  242.29  241.89  240.19  239.89  239.69
  239.29  239.09  238.89  239.19  238.89   238.9  239.06  239.09  237.52  237.47
   237.3  237.64     237  236.73  236.73  236.68  241.13   241.1  237.92  237.87
  237.87  236.48  237.16  238.18  239.83  243.32  243.19  243.43  245.39   246.6
  247.71  248.19  253.19  255.89  256.89  259.29  261.49  261.59  262.49
Pier Skew, UpSta & Num, DnSta & Num=,4971.1, 2 ,4971.1, 2 , 0 , 0 , 0 ,,
       1       1
  228.38  242.23
       1       1
  228.27  242.12
Pier Skew, UpSta & Num, DnSta & Num=,5000.6, 2 ,5000.6, 2 , 0 , 0 , 0 ,,
       1       1
  227.49  242.23
       1       1
  227.38  242.12
Pier Skew, UpSta & Num, DnSta & Num=,5031.2, 2 ,5031.2, 2 , 0 , 0 , 0 ,,
       1       1
  228.94  242.22
       1       1
  228.83  242.11
BR Coef= 1 , 1 , 0 ,1.25, 0 ,,,0.8,0,2,0,
Wspro=,,,, 1 ,,,, 0 ,,,, 0 ,,,,-1 ,-1 ,-1 , 0 , 0 , 0 , 0 , 0
BC Design=,, 0 ,, 0 ,,,,,,
BR U #Sta/Elev= 107
  4348.2   253.2  4398.2   249.1  4408.2   248.3  4418.2   247.7  4488.2   244.1
  4498.2   243.7  4508.5  243.53  4578.2   242.4  4588.2     242  4598.2   241.7
  4638.2   240.3  4648.2     240  4658.2   239.8  4668.2   239.4  4678.2   239.2
  4688.2   239.1  4698.2     239  4708.2   239.3  4708.5   239.3  4718.2   239.2
  4718.5   239.2  4728.2   239.1  4738.2     239  4738.5     239  4748.2     239
  4748.5  239.01  4756.6  239.17  4758.2   239.2  4761.5  237.63  4802.1  237.58
  4804.8  237.58  4847.9  237.41    4849  237.41  4893.2   237.7  4900.5  237.75
  4932.8  237.11  4939.8  236.87 4940.59  236.84  4940.7  236.84 4940.81  236.83
  4941.9   236.8 4942.01  236.79  4942.1  236.79  4942.2  236.79  4955.1  236.34
  4961.5  235.26  4963.4  232.94  4967.3  229.67  4971.1  229.46  4976.8  228.59
  4984.3  228.73  4993.5  228.03  5000.6  228.53  5005.1  228.81  5011.1  228.41
  5020.7  228.86  5026.3  229.67  5031.2  229.97  5034.8  230.31  5036.6  232.98
  5038.7  233.95  5050.1  236.49  5054.7  238.24  5059.2  238.04 5059.29  238.04
  5059.4  238.03  5059.5  238.03 5060.49  237.99  5060.6  237.98 5060.71  237.98
  5061.9  237.92  5073.8   237.4  5092.3  236.59  5128.7  237.06    5145  237.27
  5177.1  238.09  5184.9  238.29  5190.6  238.51  5223.5  239.75  5228.4  239.94
    5272  243.43  5272.3  243.45  5279.4   243.3  5282.7  243.54  5292.7  244.28
  5309.4   245.5  5312.7  245.67  5319.4     246  5332.7  246.71  5342.7  247.24
  5349.4   247.6  5352.5  247.82  5359.4   248.3  5379.4     250  5419.4   253.3
  5429.4   254.2  5449.4     256  5459.4   256.5  5469.4     257  5479.4   257.6
  5509.4   259.4  5519.4   260.1  5529.4   260.9  5539.4   261.6  5549.4   261.7
  5559.4     262  5576.8   262.6
BR U #Mann= 6
 4348.20     0.2  4708.5    0.16  4961.5    0.04  5038.7    0.16  5190.6     0.1
  5352.5     0.2
BR U Banks=4961.50,5038.70
BR D #Sta/Elev= 107
  4348.2  253.09  4398.2  248.99  4408.2  248.19  4418.2  247.59  4488.2  243.99
  4498.2  243.59  4508.5  243.42  4578.2  242.29  4588.2  241.89  4598.2  241.59
  4638.2  240.19  4648.2  239.89  4658.2  239.69  4668.2  239.29  4678.2  239.09
  4688.2  238.99  4698.2  238.89  4708.2  239.19  4708.5  239.19  4718.2  239.09
  4718.5  239.09  4728.2  238.99  4738.2  238.89  4738.5  238.89  4748.2  238.89
  4748.5   238.9  4756.6  239.06  4758.2  239.09  4761.5  237.52  4802.1  237.47
  4804.8  237.47  4847.9   237.3    4849   237.3  4893.2  237.59  4900.5  237.64
  4932.8     237  4939.8  236.76 4940.59  236.73  4940.7  236.73 4940.81  236.72
  4941.9  236.69 4942.01  236.68  4942.1  236.68  4942.2  236.68  4955.1  236.23
  4961.5  235.15  4963.4  232.83  4967.3  229.56  4971.1  229.35  4976.8  228.48
  4984.3  228.62  4993.5  227.92  5000.6  228.42  5005.1   228.7  5011.1   228.3
  5020.7  228.75  5026.3  229.56  5031.2  229.86  5034.8   230.2  5036.6  232.87
  5038.7  233.84  5050.1  236.38  5054.7  238.13  5059.2  237.93 5059.29  237.93
  5059.4  237.92  5059.5  237.92 5060.49  237.88  5060.6  237.87 5060.71  237.87
  5061.9  237.81  5073.8  237.29  5092.3  236.48  5128.7  236.95    5145  237.16
  5177.1  237.98  5184.9  238.18  5190.6   238.4  5223.5  239.64  5228.4  239.83
    5272  243.32  5272.3  243.34  5279.4  243.19  5282.7  243.43  5292.7  244.17
  5309.4  245.39  5312.7  245.56  5319.4  245.89  5332.7   246.6  5342.7  247.13
  5349.4  247.49  5352.5  247.71  5359.4  248.19  5379.4  249.89  5419.4  253.19
  5429.4  254.09  5449.4  255.89  5459.4  256.39  5469.4  256.89  5479.4  257.49
  5509.4  259.29  5519.4  259.99  5529.4  260.79  5539.4  261.49  5549.4  261.59
  5559.4  261.89  5576.8  262.49
BR D #Mann= 6
 4348.20     0.2  4708.5    0.16  4961.5    0.04  5038.7    0.16  5190.6     0.1
  5352.5     0.2
BR D Banks=4961.50,5038.70

Type RM Length L Ch R = 1 ,374020.0,125.6,125.6,125.6
BEGIN DESCRIPTION:
Downstream Section of Bridge/Culvert/Weir
END DESCRIPTION:
#Sta/Elev= 30
  4348.2  253.07  4408.2  248.17  4498.2  243.57  4578.2  242.27  4668.2  239.27
  4708.5  239.17  4758.2  239.07  4761.5   237.5  4900.5  237.62  4955.1  236.21
  4961.5  235.13  4963.4  232.81  4967.3  229.54  4976.8  228.46  4993.5   227.9
  5020.7  228.73  5034.8  230.18  5036.6  232.85  5038.7  233.82  5050.1  236.36
  5054.7  238.11  5092.3  236.46  5190.6  238.38  5228.4  239.81  5272.3  243.32
  5279.4  243.17  5352.5  247.69  5449.4  255.87  5539.4  261.47  5576.8  262.47
#Mann= 6 , 1 , 0
 4348.20     0.2       0  4708.5    0.16       0  4961.5    0.04       0
  5038.7    0.16       0  5190.6     0.1       0  5352.5     0.2       0
#XS Ineff= 2 , 0
       0  4932.1   240.8  5069.2       0   242.5
Bank Sta=4961.50,5038.70
Exp/Cntr=0.5,0.3

Type RM Length L Ch R = 1 ,373894.4,694.1,694.1,694.1
BEGIN DESCRIPTION:
Cross Section Little River 46.0
END DESCRIPTION:
#Sta/Elev= 30
  4299.6     252  4349.6   251.5  4389.6   250.2  4429.6   249.9  4519.6   250.3
  4609.6   252.5  4699.6   249.5  4769.6   241.9  4789.6   241.9  4799.6     241
  4829.6   237.1  4939.6   236.6  4961.5  234.84  4963.4  232.52  4967.3  229.25
  4976.8  228.17  4984.3  228.31  4993.5  227.61  5005.1  228.39  5011.1  227.99
  5020.7  228.44  5034.8  229.89  5036.6  232.56  5038.7  233.53  5046.6   235.7
  5106.6     237  5183.8  239.56  5246.6   242.9  5306.6   248.2  5414.6   253.5
#Mann= 6 , 1 , 0
 4299.60     0.2       0  4299.6    0.16       0  4961.5    0.04       0
  5038.7    0.16       0  5183.8     0.1       0  5414.6     0.2       0
Bank Sta=4961.50,5038.70
Exp/Cntr=0.3,0.1

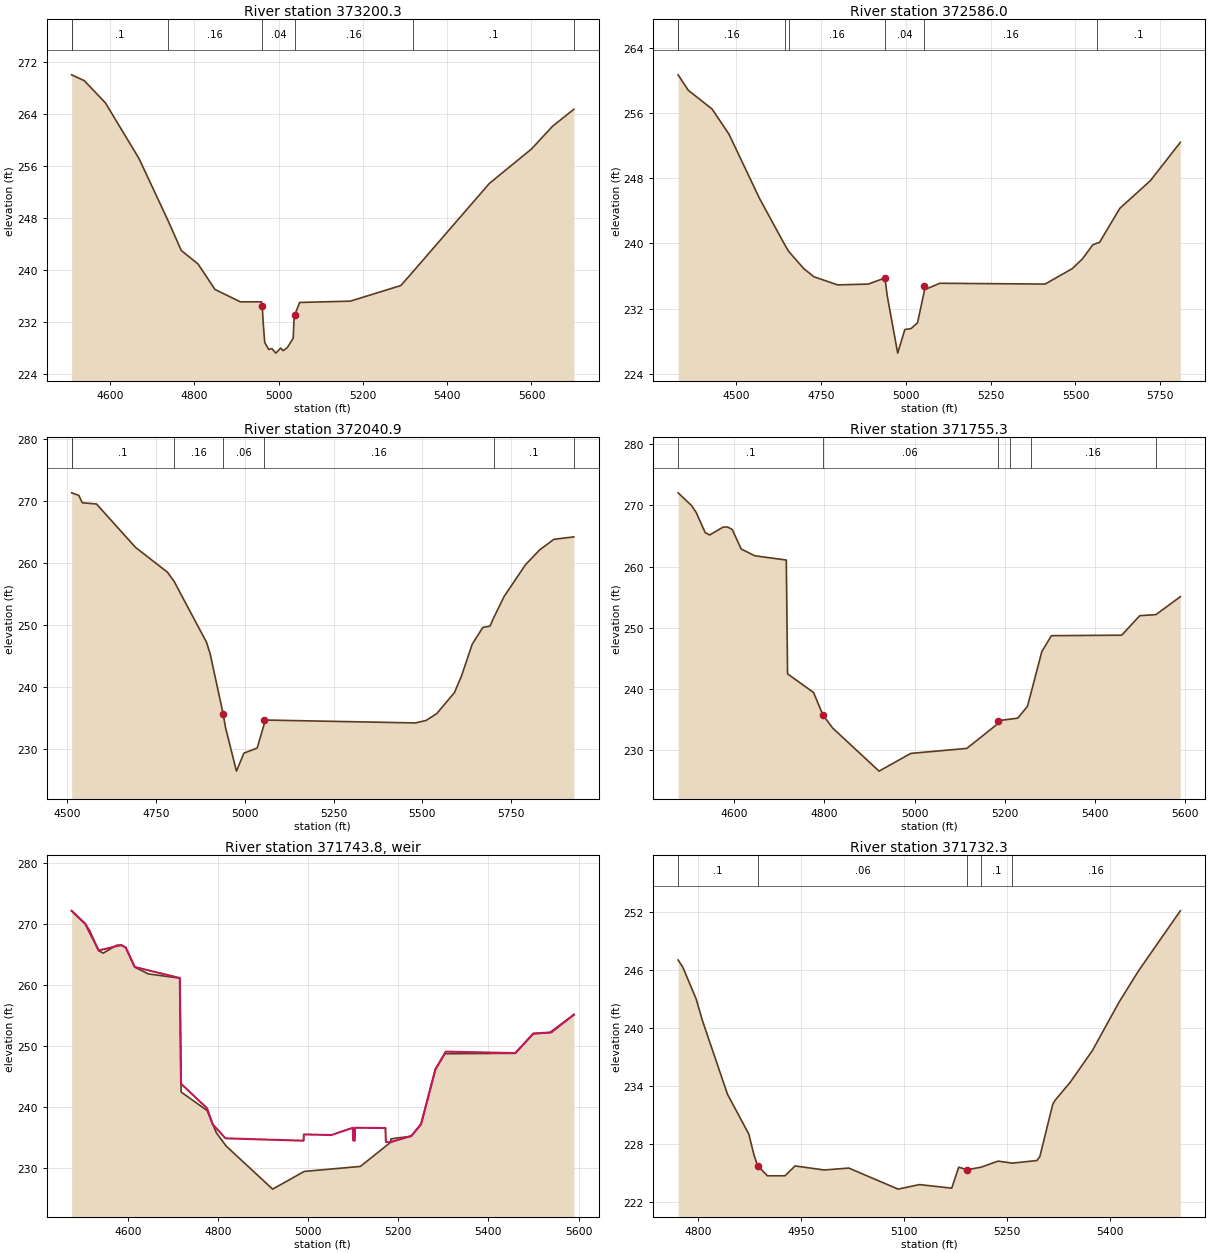
Type RM Length L Ch R = 1 ,373200.3,614.3,614.3,614.3
BEGIN DESCRIPTION:
Cross Section Little River 45.0
END DESCRIPTION:
#Sta/Elev= 30
  4509.3     270  4539.3   269.1  4589.3   265.7  4669.3   257.1  4738.3  247.54
  4769.3     243  4809.3   240.9  4849.3     237  4909.3   235.1  4959.3   235.1
  4961.5  234.44  4963.4  232.12  4967.3  228.85  4976.8  227.77  4984.3  227.91
  4993.5  227.21  5005.1  227.99  5011.1  227.59  5020.7  228.04  5034.8  229.49
  5036.6  232.16  5038.7  233.13  5050.1     235  5170.1   235.2  5290.1   237.6
  5318.4  239.69  5500.1   253.3  5600.1   258.6  5650.1   262.1  5700.5   264.7
#Mann= 7 , 1 , 0
 4509.30     0.2       0  4509.3     0.1       0  4738.3    0.16       0
  4961.5    0.04       0  5038.7    0.16       0  5318.4     0.1       0
  5700.5     0.2       0
Bank Sta=4961.50,5038.70
Exp/Cntr=0.3,0.1

Type RM Length L Ch R = 1 ,372586.0,545.1,545.1,545.1
BEGIN DESCRIPTION:
Cross Section Little River 44.0
END DESCRIPTION:
#Sta/Elev= 30
  4329.6   260.7  4359.6   258.8  4429.6   256.5  4479.6   253.4  4569.6   245.5
  4644.2  239.79  4655.2  239.02  4699.6   236.9  4729.6   235.9  4799.6   234.9
  4889.6     235 4938.95  235.75 4945.46  233.58 4976.39  226.52 4997.45  229.42
 5015.81  229.54  5034.8  230.24 5054.54  234.11 5055.26  234.76  5060.6   234.4
  5100.6   235.1  5410.6     235  5490.6   236.9  5520.6   238.1  5550.6   239.8
  5562.9  240.02  5570.6   240.1  5630.6   244.3  5720.6   247.7  5808.8   252.4
#Mann= 7 , 1 , 0
 4329.60     0.2       0  4329.6    0.16       0  4644.2     0.1       0
  4655.2    0.16       0 4938.95    0.04       0 5055.26    0.16       0
  5562.9     0.1       0
Bank Sta=4938.95,5055.26
Exp/Cntr=0.3,0.1

Type RM Length L Ch R = 1 ,372040.9,285.6,285.6,285.6
BEGIN DESCRIPTION:
Cross Section Little River 43.0
END DESCRIPTION:
#Sta/Elev= 30
  4512.1   271.3  4532.1   270.9  4542.1   269.7  4582.1   269.5  4692.1   262.5
  4782.1   258.5  4800.9  257.01  4892.1   247.2  4902.1   245.4 4938.95  235.66
 4945.46  233.49 4976.39  226.43 4997.45  229.33  5034.8  230.15 5054.54  234.02
 5055.26  234.67  5480.6   234.2  5510.6   234.6  5540.6   235.7  5590.6   239.1
  5610.6   241.8  5640.6   246.9  5670.6   249.6  5690.6   249.8  5700.7  251.11
  5730.6   254.6  5790.6   259.7  5830.6   262.1  5870.6   263.8  5926.9   264.2
#Mann= 7 , 1 , 0
 4512.10     0.2       0  4512.1     0.1       0  4800.9    0.16       0
 4938.95    0.06       0 5055.26    0.16       0  5700.7     0.1       0
  5926.9     0.2       0
Bank Sta=4938.95,5055.26
Exp/Cntr=0.5,0.3

Type RM Length L Ch R = 1 ,371755.3,23,23,23
BEGIN DESCRIPTION:
Upstream Section of Bridge/Culvert/Weir
END DESCRIPTION:
#Sta/Elev= 30
  4475.5  272.07  4505.5  269.97  4515.5  268.87  4535.5  265.57  4545.5  265.17
  4575.5  266.47  4585.5  266.47  4595.5  266.07  4615.5  262.87  4645.5  261.77
  4715.5  261.07  4718.3  242.43  4775.9   239.4  4796.5  235.75  4818.2  233.58
  4921.3  226.52  4991.5  229.42    5116  230.24  5181.8  234.11  5184.2  234.76
  5212.3  235.03  5228.9  235.19  5250.2   237.1  5257.8  239.17  5282.3  246.09
  5303.6  248.69  5459.6  248.77  5499.6  251.97  5535.3  252.13  5589.5  255.07
#Mann= 6 , 1 , 0
 4475.50     0.1       0  4796.5    0.06       0  5184.2    0.06       0
  5212.3     0.1       0  5257.8    0.16       0  5535.3     0.2       0
#XS Ineff= 2 , 0
       0  4785.8   234.3  5194.9       0   234.2
Bank Sta=4796.50,5184.20
Exp/Cntr=0.5,0.3

Type RM Length L Ch R = 5 ,371743.8,,,
BEGIN DESCRIPTION:
HIGHWAY 97 DAM
Structure ID: WK_LITR4B
END DESCRIPTION:
#Inline Weir SE= 30
  4475.5   272.1  4505.5     270  4535.5   265.6  4585.5   266.5  4595.5   266.1
  4615.5   262.9  4715.5   261.1    4718  244.47  4718.3  243.77  4775.9  239.76
  4788.3  237.14  4816.7  234.84    4990  234.45  4990.6  235.48  5051.8  235.38
  5099.3  236.57  5099.9   234.5  5103.6  234.44  5104.1  236.57  5171.6  236.53
  5172.5  234.26  5181.8  234.19  5228.9  235.23  5250.6  237.18  5282.3  246.13
  5305.3  249.04  5459.6   248.8  5499.6     252  5539.6   252.2  5589.5   255.1
IW Dist,WD,Coef,Skew,MaxSub,Min_El,Is_Ogee,SpillHt,DesHd
10.0,3.0,3.0,,0.95,, 0 ,,,1.0,1.0,

Type RM Length L Ch R = 1 ,371732.3,86.3,86.3,86.3
BEGIN DESCRIPTION:
Cross Section FIELD_DS
Located At: HIGHWAY 97 DAM
END DESCRIPTION:
#Sta/Elev= 30
  4770.9  247.02  4777.7  246.29  4797.3  242.97  4806.3  240.76  4842.9  233.12
  4873.9  229.01  4881.2  226.92  4886.6  225.74  4901.1  224.69  4926.7  224.69
  4941.3  225.71  4983.9  225.29  5019.6  225.49  5091.5  223.31  5122.5  223.78
  5169.6  223.41  5179.8  225.58  5192.1  225.32  5212.3  225.58  5237.2  226.21
  5257.8     226  5293.7  226.27    5298  226.67  5316.7  232.06  5320.3  232.51
  5342.7  234.41  5374.5  237.64  5413.2  242.63    5442  245.92  5502.7  252.11
#Mann= 5 , 1 , 0
 4770.90     0.1       0  4886.6    0.06       0  5192.1    0.06       0
  5212.3     0.1       0  5257.8    0.16       0
Bank Sta=4886.60,5192.10
Exp/Cntr=0.3,0.1

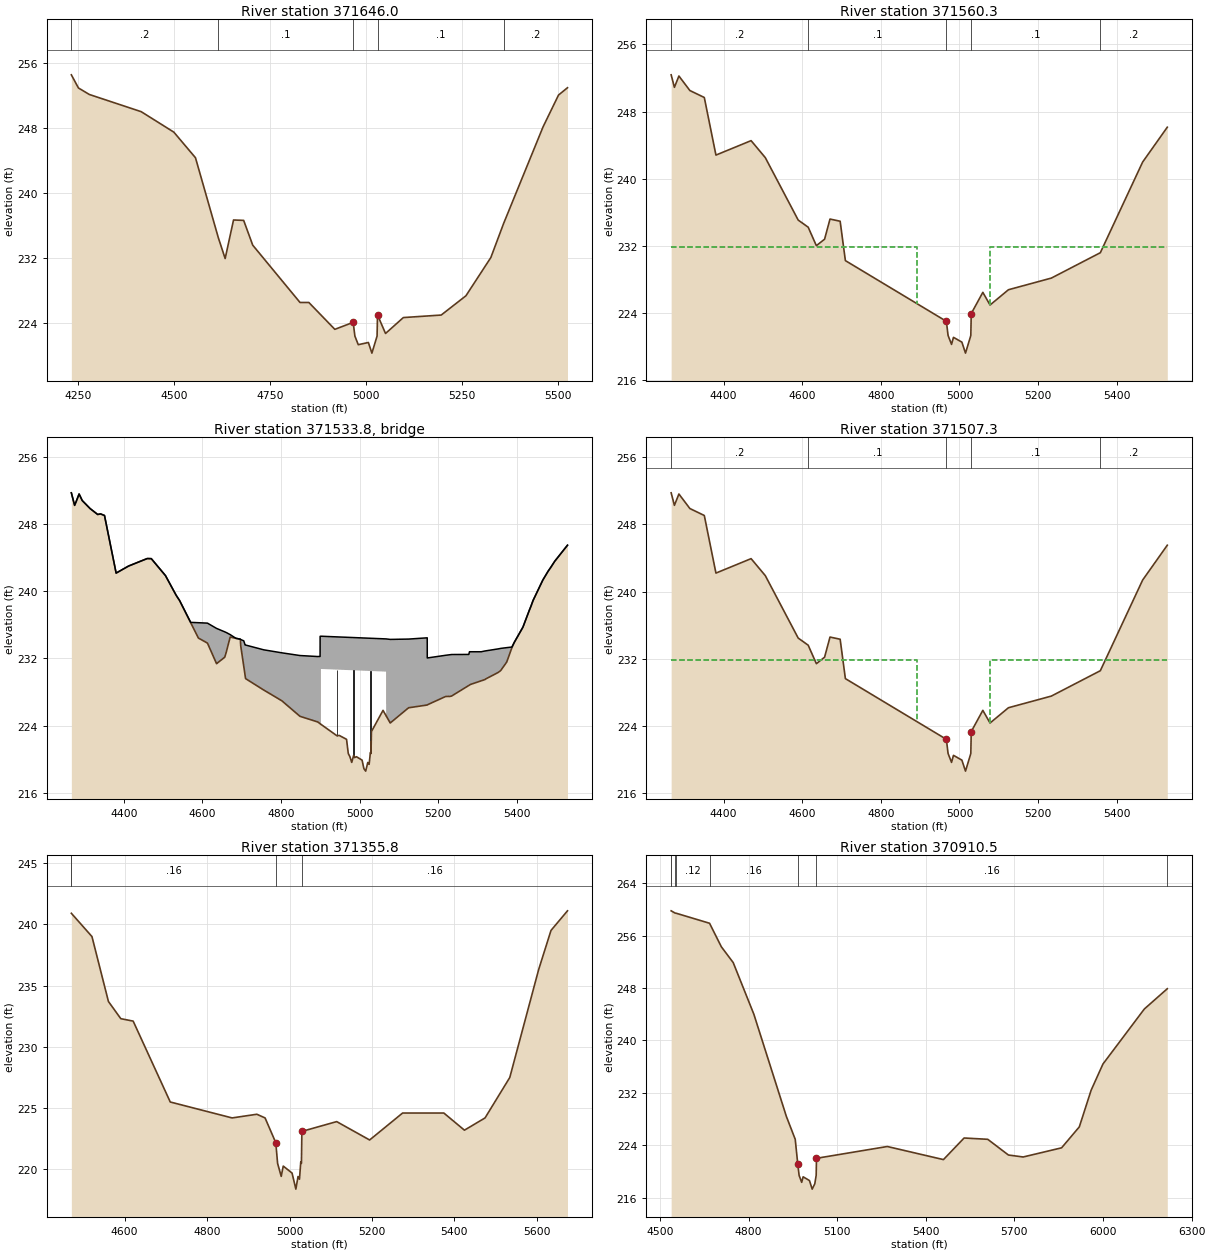
Type RM Length L Ch R = 1 ,371646.0,85.7,85.7,85.7
BEGIN DESCRIPTION:
Cross Section Little River 42.8
END DESCRIPTION:
#Sta/Elev= 30
  4232.8  254.57  4251.3  252.95  4279.6  252.15  4414.7  250.03  4499.7  247.51
    4556  244.36  4615.3  234.54  4633.3  231.94  4655.1  236.69  4681.5  236.64
  4705.1  233.59  4828.2  226.53  4851.2  226.53  4918.9  223.22  4966.7  224.08
  4971.1  222.39  4979.9  221.33  5006.2   221.6  5015.4  220.29  5028.9  222.39
    5030     225  5050.9  222.71  5097.3  224.67  5195.9  224.98  5260.2  227.35
  5325.1  232.06  5358.3  236.25  5461.2  248.17  5501.4  252.08  5524.7  252.98
#Mann= 5 , 1 , 0
 4232.80     0.2       0  4615.3     0.1       0  4966.7   0.035       0
    5030     0.1       0  5358.3     0.2       0
Bank Sta=4966.70,5030.00
Exp/Cntr=0.5,0.3

Type RM Length L Ch R = 1 ,371560.3,53,53,53
BEGIN DESCRIPTION:
Upstream Section of Bridge/Culvert/Weir
END DESCRIPTION:
#Sta/Elev= 30
  4266.8  252.38  4275.1  250.89  4286.5  252.24  4314.4  250.51  4351.1  249.68
  4380.7  242.82  4470.1  244.54  4506.2  242.52  4589.9  235.08  4615.3  234.23
  4636.1  232.03    4657   232.8  4670.8   235.2  4696.6  234.94  4709.9  230.25
  4966.7  223.02  4971.1  221.33  4979.9  220.27  4984.8  221.11  5006.2  220.54
  5015.4  219.23  5028.9  221.33    5030  223.94  5059.5  226.47  5077.8  224.96
  5124.6  226.78  5233.8  228.17  5358.3  231.19  5465.9  241.99  5528.6  246.14
#Mann= 5 , 1 , 0
 4266.80     0.2       0  4615.3     0.1       0  4966.7   0.035       0
    5030     0.1       0  5358.3     0.2       0
#XS Ineff= 2 , 0
       0  4891.4   231.9  5077.1       0   231.9
Bank Sta=4966.70,5030.00
Exp/Cntr=0.5,0.3

Type RM Length L Ch R = 3 ,371533.8,,,
BEGIN DESCRIPTION:
NC-97
Structure ID: WK_LITR4
END DESCRIPTION:
Bridge Culvert--1,0,-1,-1, 0
Deck Dist Width WeirC Skew NumUp NumDn MinLoCord MaxHiCord MaxSubmerge Is_Ogee
10,33,2.6,, 60, 60,,,0.95,0,1,1,,
  4266.8  4275.1  4286.5  4294.5  4314.4  4333.8    4341  4351.1  4380.7  4412.4
  4459.7  4470.1  4506.2  4533.2  4541.9  4570.3  4589.9  4612.9  4636.1    4657
  4660.9  4670.8  4685.3  4696.6  4697.5  4705.3  4708.7  4709.9  4756.1  4802.4
  4848.2  4893.2 4899.39  4899.5 4901.51  4901.6 5067.19  5067.3  5077.8  5124.6
  5171.9 5172.01  5218.8  5233.8  5277.6  5279.3  5281.7  5309.3  5318.4  5352.2
  5358.8  5374.1  5387.1  5393.3  5415.3  5441.1  5465.9  5479.3  5496.2  5528.6
  251.73  250.24  251.59  250.81  249.86  249.15  249.22  249.03  242.17  243.01
   243.9  243.89  241.87  239.54  238.92   236.3  236.26  236.21  235.58  235.17
  235.09  234.84   234.4   234.3  234.26   234.1  233.61   233.6  233.03  232.67
  232.35  232.23  232.24  234.64  234.65  234.65  234.33  234.33  234.27  234.31
  234.46  232.06  232.38  232.47  232.48   232.8   232.8   232.8  232.89  233.14
   233.2  233.29  233.36  233.92  235.73  238.91  241.34  242.39  243.58  245.49
  251.73  250.24  251.59  250.81  249.86  249.15  249.22  249.03  242.17  243.01
   243.9  243.89  241.87  239.54  238.92  236.26  234.43  233.83  231.38  232.15
  232.76  234.55   234.4  234.29  233.53  231.06  229.98   229.6  228.24  226.95
  225.11  224.44  224.23  224.23  224.16  230.75  230.43  225.18  224.31  226.13
  226.47  226.47  227.47  227.52  228.78  228.83   228.9  229.34  229.48  230.33
  230.56  231.57  233.26  233.91  235.73  238.91  241.34  242.39  243.58  245.49
  4266.8  4275.1  4286.5  4294.5  4314.4  4333.8    4341  4351.1  4380.7  4412.4
  4459.7  4470.1  4506.2  4533.2  4541.9  4570.3  4589.9  4612.9  4636.1    4657
  4660.9  4670.8  4685.3  4696.6  4697.5  4705.3  4708.7  4709.9  4756.1  4802.4
  4848.2  4893.2 4899.39  4899.5 4901.51  4901.6 5067.19  5067.3  5077.8  5124.6
  5171.9 5172.01  5218.8  5233.8  5277.6  5279.3  5281.7  5309.3  5318.4  5352.2
  5358.8  5374.1  5387.1  5393.3  5415.3  5441.1  5465.9  5479.3  5496.2  5528.6
  251.73  250.24  251.59  250.81  249.86  249.15  249.22  249.03  242.17  243.01
   243.9  243.89  241.87  239.54  238.92   236.3  236.26  236.21  235.58  235.17
  235.09  234.84   234.4   234.3  234.26   234.1  233.61   233.6  233.03  232.67
  232.35  232.23  232.24  234.64  234.65  234.65  234.33  234.33  234.27  234.31
  234.46  232.06  232.38  232.47  232.48   232.8   232.8   232.8  232.89  233.14
   233.2  233.29  233.36  233.92  235.73  238.91  241.34  242.39  243.58  245.49
  251.63  250.14  251.49  250.71  249.76  249.05  249.12  248.93  242.07  242.91
   243.8  243.79  241.77  239.44  238.82  236.16  234.33  233.73  231.28  232.05
  232.66  234.45   234.3  234.19  233.43  230.96  229.88   229.5  228.14  226.85
  225.01  224.34  224.13  224.13  224.06  230.65  230.33  225.08  224.21  226.03
  226.37  226.37  227.37  227.42  228.68  228.73   228.8  229.24  229.38  230.23
  230.46  231.47  233.16  233.81  235.63  238.81  241.24  242.29  243.48  245.39
Pier Skew, UpSta & Num, DnSta & Num=,4942.1, 2 ,4942.1, 2 , 0 , 0 , 0 ,,
       1       1
   221.8  231.67
       1       1
   221.7  231.57
Pier Skew, UpSta & Num, DnSta & Num=,4984.8, 2 ,4984.8, 2 , 0 , 0 , 0 ,,
       1       1
  219.37  231.59
       1       1
  219.27  231.49
Pier Skew, UpSta & Num, DnSta & Num=,5027.3, 2 ,5027.3, 2 , 0 , 0 , 0 ,,
       1       1
  219.57  231.51
       1       1
  219.47  231.41
BR Coef= 1 , 1 , 0 ,1.25, 0 ,,,0.8,0,2,0,
Wspro=,,,, 1 ,,,, 0 ,,,, 0 ,,,,-1 ,-1 ,-1 , 0 , 0 , 0 , 0 , 0
BC Design=,, 0 ,, 0 ,,,,,,
BR U #Sta/Elev= 113
  4266.8  251.73  4275.1  250.24  4279.4   250.7  4286.5  251.59  4294.5  250.81
  4314.4  249.86  4333.8  249.15    4341  249.22  4351.1  249.03  4380.7  242.17
  4412.4  243.01  4459.7   243.9  4470.1  243.89  4506.2  241.87  4533.2  239.54
  4540.2  239.02  4541.9  238.92  4570.3  236.26  4589.9  234.43  4612.9  233.83
  4615.3  233.58  4625.3  232.52  4635.3  231.46  4636.1  231.38  4645.3  231.72
    4657  232.15  4660.9  232.76  4665.3  233.56  4670.8  234.55  4675.3   234.5
  4685.3   234.4  4695.3   234.3  4696.6  234.29  4697.5  233.53  4705.3  231.06
  4708.7  229.98  4709.9   229.6  4755.3  228.26  4756.1  228.24  4802.4  226.95
  4805.3  226.83  4848.2  225.11  4850.1  225.08  4893.2  224.44  4895.4  224.37
 4899.39  224.23  4899.5  224.23 4899.61  224.23  4901.4  224.16 4901.51  224.16
  4901.6  224.16  4901.7  224.15  4942.1   222.8  4948.1  222.83  4966.7  222.37
  4971.1  220.68  4975.3  220.29  4979.9  219.62  4984.8  220.46  4987.1  220.19
  4991.7   220.3  5006.2  219.89  5010.8  218.88  5015.4  218.58  5020.7  219.61
  5024.2  219.39  5027.3   220.8  5028.9  220.68    5030  223.29  5059.5  225.82
  5067.1  225.19 5067.19  225.19  5067.3  225.18  5067.4  225.17  5077.8  224.31
  5079.3  224.37  5124.6  226.13  5125.3  226.13  5171.1  226.45 5171.79  226.46
  5171.9  226.47 5172.01  226.47  5184.9  226.75  5218.8  227.47  5225.9  227.48
  5227.9  227.47  5230.5  227.49  5233.8  227.52  5277.6  228.78  5279.3  228.83
  5281.7   228.9  5309.3  229.34  5318.4  229.48  5319.3  229.51  5321.5  229.58
  5329.3  229.77  5339.3  230.01  5352.2  230.33  5358.3  230.54  5358.8  230.56
  5374.1  231.57  5387.1  233.26  5393.3  233.91  5395.3  234.08  5415.3  235.73
  5431.4  237.73  5435.6  238.18  5441.1  238.91  5465.9  241.34  5479.3  242.39
  5485.9  242.81  5496.2  243.58  5528.6  245.49
BR U #Mann= 5
 4266.80     0.2  4615.3     0.1  4966.7   0.035    5030     0.1  5358.3     0.2
BR U Banks=4966.70,5030.00
BR D #Sta/Elev= 113
  4266.8  251.63  4275.1  250.14  4279.4   250.6  4286.5  251.49  4294.5  250.71
  4314.4  249.76  4333.8  249.05    4341  249.12  4351.1  248.93  4380.7  242.07
  4412.4  242.91  4459.7   243.8  4470.1  243.79  4506.2  241.77  4533.2  239.44
  4540.2  238.92  4541.9  238.82  4570.3  236.16  4589.9  234.33  4612.9  233.73
  4615.3  233.48  4625.3  232.42  4635.3  231.36  4636.1  231.28  4645.3  231.62
    4657  232.05  4660.9  232.66  4665.3  233.46  4670.8  234.45  4675.3   234.4
  4685.3   234.3  4695.3   234.2  4696.6  234.19  4697.5  233.43  4705.3  230.96
  4708.7  229.88  4709.9   229.5  4755.3  228.16  4756.1  228.14  4802.4  226.85
  4805.3  226.73  4848.2  225.01  4850.1  224.98  4893.2  224.34  4895.4  224.27
 4899.39  224.13  4899.5  224.13 4899.61  224.13  4901.4  224.06 4901.51  224.06
  4901.6  224.06  4901.7  224.05  4942.1   222.7  4948.1  222.73  4966.7  222.27
  4971.1  220.58  4975.3  220.19  4979.9  219.52  4984.8  220.36  4987.1  220.09
  4991.7   220.2  5006.2  219.79  5010.8  218.78  5015.4  218.48  5020.7  219.51
  5024.2  219.29  5027.3   220.7  5028.9  220.58    5030  223.19  5059.5  225.72
  5067.1  225.09 5067.19  225.09  5067.3  225.08  5067.4  225.07  5077.8  224.21
  5079.3  224.27  5124.6  226.03  5125.3  226.03  5171.1  226.35 5171.79  226.36
  5171.9  226.37 5172.01  226.37  5184.9  226.65  5218.8  227.37  5225.9  227.38
  5227.9  227.37  5230.5  227.39  5233.8  227.42  5277.6  228.68  5279.3  228.73
  5281.7   228.8  5309.3  229.24  5318.4  229.38  5319.3  229.41  5321.5  229.48
  5329.3  229.67  5339.3  229.91  5352.2  230.23  5358.3  230.44  5358.8  230.46
  5374.1  231.47  5387.1  233.16  5393.3  233.81  5395.3  233.98  5415.3  235.63
  5431.4  237.63  5435.6  238.08  5441.1  238.81  5465.9  241.24  5479.3  242.29
  5485.9  242.71  5496.2  243.48  5528.6  245.39
BR D #Mann= 5
 4266.80     0.2  4615.3     0.1  4966.7   0.035    5030     0.1  5358.3     0.2
BR D Banks=4966.70,5030.00

Type RM Length L Ch R = 1 ,371507.3,151.5,151.5,151.5
BEGIN DESCRIPTION:
Downstream Section of Bridge/Culvert/Weir
END DESCRIPTION:
#Sta/Elev= 30
  4266.8  251.77  4275.1  250.28  4286.5  251.63  4314.4   249.9  4351.1  249.07
  4380.7  242.21  4470.1  243.93  4506.2  241.91  4589.9  234.47  4615.3  233.62
  4636.1  231.42    4657  232.19  4670.8  234.59  4696.6  234.33  4709.9  229.64
  4966.7  222.41  4971.1  220.72  4979.9  219.66  4984.8   220.5  5006.2  219.93
  5015.4  218.62  5028.9  220.72    5030  223.33  5059.5  225.86  5077.8  224.35
  5124.6  226.17  5233.8  227.56  5358.3  230.58  5465.9  241.38  5528.6  245.53
#Mann= 5 , 1 , 0
 4266.80     0.2       0  4615.3     0.1       0  4966.7   0.035       0
    5030     0.1       0  5358.3     0.2       0
#XS Ineff= 2 , 0
       0  4891.4   231.9  5077.1       0   231.9
Bank Sta=4966.70,5030.00
Exp/Cntr=0.5,0.3

Type RM Length L Ch R = 1 ,371355.8,445.3,445.3,445.3
BEGIN DESCRIPTION:
Cross Section Little River 42.0
END DESCRIPTION:
#Sta/Elev= 30
  4470.7   240.9  4520.7     239  4560.7   233.7  4590.7   232.3  4620.7   232.1
  4710.7   225.5  4860.7   224.2  4920.7   224.5  4940.7   224.2  4966.7  222.18
  4971.1  220.49  4979.9  219.43  4984.8  220.27  5006.2   219.7  5015.4  218.39
  5020.7  219.42  5024.2   219.2  5027.3  220.61  5028.9  220.49    5030   223.1
  5114.4   223.9  5194.4   222.4  5274.4   224.6  5374.4   224.6  5424.4   223.2
  5474.4   224.2  5534.4   227.5  5604.4   236.3  5634.4   239.5  5674.4   241.1
#Mann= 4 , 1 , 0
 4470.70     0.2       0  4470.7    0.16       0  4966.7   0.045       0
    5030    0.16       0
Bank Sta=4966.70,5030.00
Exp/Cntr=0.3,0.1

Type RM Length L Ch R = 1 ,370910.5,650.9,650.9,650.9
BEGIN DESCRIPTION:
Cross Section Little River 42.5
END DESCRIPTION:
#Sta/Elev= 30
    4538   259.8  4550.8  259.47  4555.8  259.42    4668   257.9    4708   254.3
    4748   251.9    4818     244    4928   228.4    4958   224.9  4966.7  221.08
  4971.1  219.39  4979.9  218.33  4984.8  219.17  5006.2   218.6  5015.4  217.29
  5024.2   218.1  5028.9  219.39    5030     222  5269.7   223.8  5459.7   221.8
  5529.7   225.1  5609.7   224.9  5679.7   222.5  5729.7   222.2  5859.7   223.6
  5919.7   226.8  5959.7   232.4  5999.7   236.4  6139.7   244.8  6217.5   247.9
#Mann= 8 , 1 , 0
 4538.00     0.2       0    4538    0.12       0  4550.8    0.16       0
  4555.8    0.12       0    4668    0.16       0  4966.7   0.045       0
    5030    0.16       0  6217.5     0.2       0
Bank Sta=4966.70,5030.00
Exp/Cntr=0.3,0.1

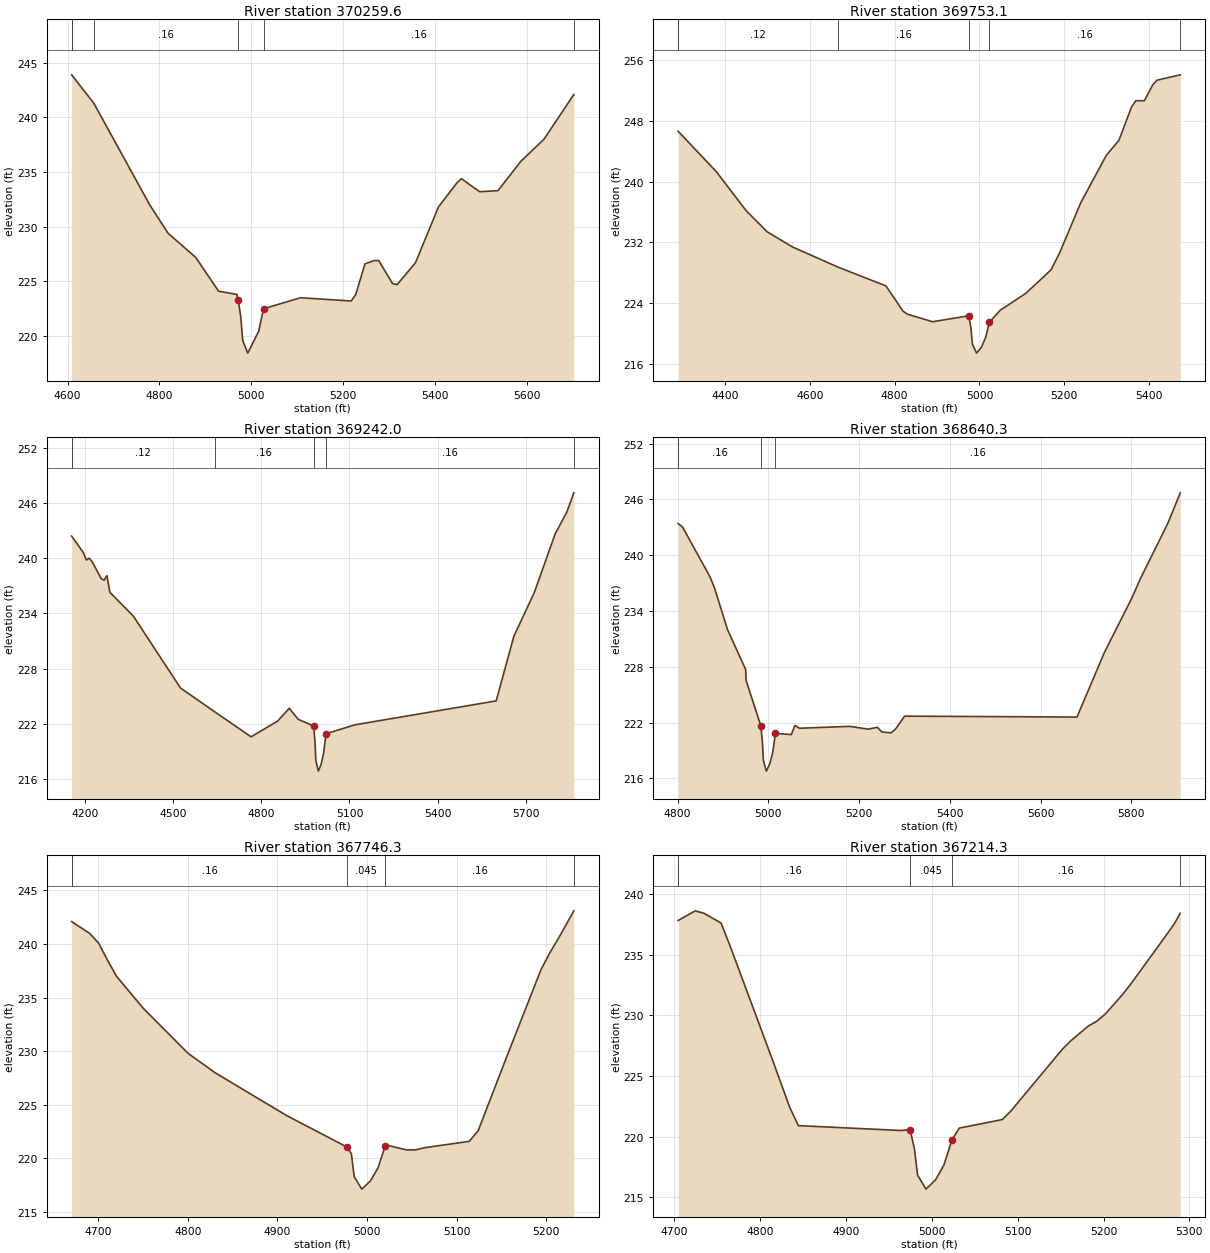
Type RM Length L Ch R = 1 ,370259.6,506.5,506.5,506.5
BEGIN DESCRIPTION:
Cross Section Little River 41.0
END DESCRIPTION:
#Sta/Elev= 30
  4608.8   243.9  4657.1   241.3  4778.8     232  4818.8   229.4  4878.8   227.2
  4928.8   224.1  4968.8   223.8 4971.44  223.33 4977.22  221.72  4981.3  219.59
 4992.35  218.43 5016.15  220.43 5026.69  222.49  5107.6   223.5  5217.6   223.2
  5227.6   223.8  5247.6   226.6  5267.6   226.9  5277.6   226.9  5307.6   224.8
  5317.6   224.7  5357.6   226.7  5407.6   231.8  5447.6     234  5457.6   234.4
  5497.4   233.2  5537.4   233.3  5587.4     236  5637.4     238  5702.5   242.1
#Mann= 6 , 1 , 0
 4608.80     0.2       0  4608.8    0.12       0  4657.1    0.16       0
 4971.44   0.045       0 5026.69    0.16       0  5702.5     0.2       0
Bank Sta=4971.44,5026.69
Exp/Cntr=0.3,0.1

Type RM Length L Ch R = 1 ,369753.1,511.1,511.1,511.1
BEGIN DESCRIPTION:
Cross Section Little River 40.0
END DESCRIPTION:
#Sta/Elev= 30
  4289.6   246.6  4379.6   241.3  4449.6   236.2  4499.6   233.4  4559.6   231.4
  4667.4  228.75  4779.6   226.3  4819.6     223  4829.6   222.6  4889.6   221.6
  4974.8  222.38  4979.9  220.77  4983.5  218.64 4993.25  217.48  5004.5  218.25
 5014.25  219.48 5023.55  221.54  5048.7   223.1  5108.7   225.3  5168.7   228.4
  5188.7   230.6  5238.7   237.2  5298.7   243.4  5328.7   245.4  5358.7   249.8
  5368.7   250.6  5388.7   250.6  5408.7   252.7  5418.7   253.3  5473.5     254
#Mann= 6 , 1 , 0
 4289.60     0.2       0  4289.6    0.12       0  4667.4    0.16       0
  4974.8   0.045       0 5023.55    0.16       0  5473.5     0.2       0
Bank Sta=4974.80,5023.55
Exp/Cntr=0.3,0.1

Type RM Length L Ch R = 1 ,369242.0,601.7,601.7,601.7
BEGIN DESCRIPTION:
Cross Section Little River 39.0
END DESCRIPTION:
#Sta/Elev= 30
  4155.5   242.4  4195.5   240.6  4205.5   239.8  4215.5     240  4225.5   239.6
  4255.5   237.8  4265.5   237.6  4275.5   238.1  4285.5   236.3  4365.5   233.7
  4525.5   225.9    4643  223.29  4765.5   220.6  4855.5   222.3  4895.5   223.7
  4925.5   222.5 4978.16  221.77 4982.58  220.16  4985.7  218.03 4994.15  216.87
  5003.9  217.64 5012.35  218.87 5020.41  220.93  5118.8   221.9  5598.8   224.5
  5658.8   231.5  5728.8   236.3  5798.8   242.6  5838.8     245  5862.8   247.1
#Mann= 6 , 1 , 0
 4155.50     0.2       0  4155.5    0.12       0    4643    0.16       0
 4978.16   0.045       0 5020.41    0.16       0  5862.8     0.2       0
Bank Sta=4978.16,5020.41
Exp/Cntr=0.3,0.1

Type RM Length L Ch R = 1 ,368640.3,894,894,894
BEGIN DESCRIPTION:
Cross Section Little River 38.0 CCX173
END DESCRIPTION:
#Sta/Elev= 30
  4801.1   243.4  4811.1     243  4871.1   237.7  4881.1   236.5    4910     232
    4950   227.7  4950.8  226.55  4983.2  221.69  4986.6  220.08    4989  217.95
  4995.5  216.79    5003  217.56  5009.5  218.79  5015.7  220.85  5050.6  220.72
  5058.6   221.7  5068.6   221.4  5180.1   221.6  5220.1   221.3  5240.1   221.5
  5250.1     221  5270.1   220.9  5280.1   221.3  5300.1   222.7  5680.1   222.6
  5740.1   229.5  5800.1   235.3  5820.1   237.5  5880.1   243.4  5907.8   246.7
#Mann= 4 , 1 , 0
 4801.10     0.2       0  4801.1    0.16       0  4983.2   0.045       0
  5015.7    0.16       0
Bank Sta=4983.20,5015.70
Exp/Cntr=0.3,0.1

Type RM Length L Ch R = 1 ,367746.3,532,532,532
BEGIN DESCRIPTION:
Cross Section Little River 37.0
END DESCRIPTION:
#Sta/Elev= 27
  4670.4   242.1  4690.4     241  4700.4   240.1  4710.4   238.5  4720.4     237
  4750.4     234  4800.4   229.8  4830.4     228  4910.4     224 4978.16  221.04
 4982.58  220.43  4985.7   218.3 4994.15  217.14  5003.9  217.91 5012.35  219.14
 5020.41   221.2  5024.1   221.2  5044.1   220.8  5054.1   220.8  5064.1     221
  5114.1   221.6  5124.1   222.6  5154.1   229.1  5194.1   237.6  5204.1   239.2
  5214.1   240.6  5230.8   243.1
#Mann= 5 , 1 , 0
 4670.40     0.2       0  4670.4    0.16       0 4978.16   0.045       0
 5020.41    0.16       0  5230.8     0.2       0
Bank Sta=4978.16,5020.41
Exp/Cntr=0.3,0.1

Type RM Length L Ch R = 1 ,367214.3,370.1,370.1,370.1
BEGIN DESCRIPTION:
Cross Section Little River 36.0
END DESCRIPTION:
#Sta/Elev= 29
  4704.7   237.8  4724.7   238.6  4734.7   238.4  4754.7   237.6  4764.7   235.8
  4814.7   226.3  4834.7   222.4  4844.7   220.9  4964.7   220.5  4974.8  220.57
  4979.9  218.96  4983.5  216.83 4993.25  215.67  5004.5  216.44 5014.25  217.67
 5023.55  219.73  5032.1   220.7  5082.1   221.4  5092.1   222.1  5152.1   227.2
  5162.1   227.9  5182.1   229.1  5192.1   229.5  5202.1   230.1  5222.1   231.7
  5232.1   232.6  5272.1   236.5  5282.1   237.5  5289.4   238.4
#Mann= 5 , 1 , 0
 4704.70     0.2       0  4704.7    0.16       0  4974.8   0.045       0
 5023.55    0.16       0  5289.4     0.2       0
Bank Sta=4974.80,5023.55
Exp/Cntr=0.3,0.1