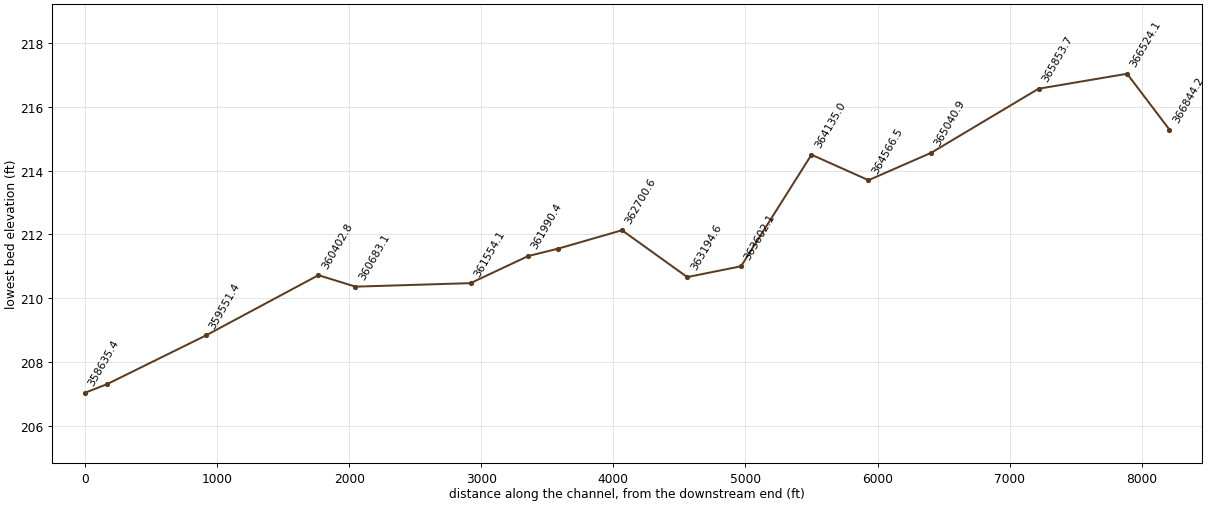
HEC-RAS study Little_River_FINAL.prj: Little River Detail Study

--- Little_River_FINAL.g01 (geometry) --- (continued)

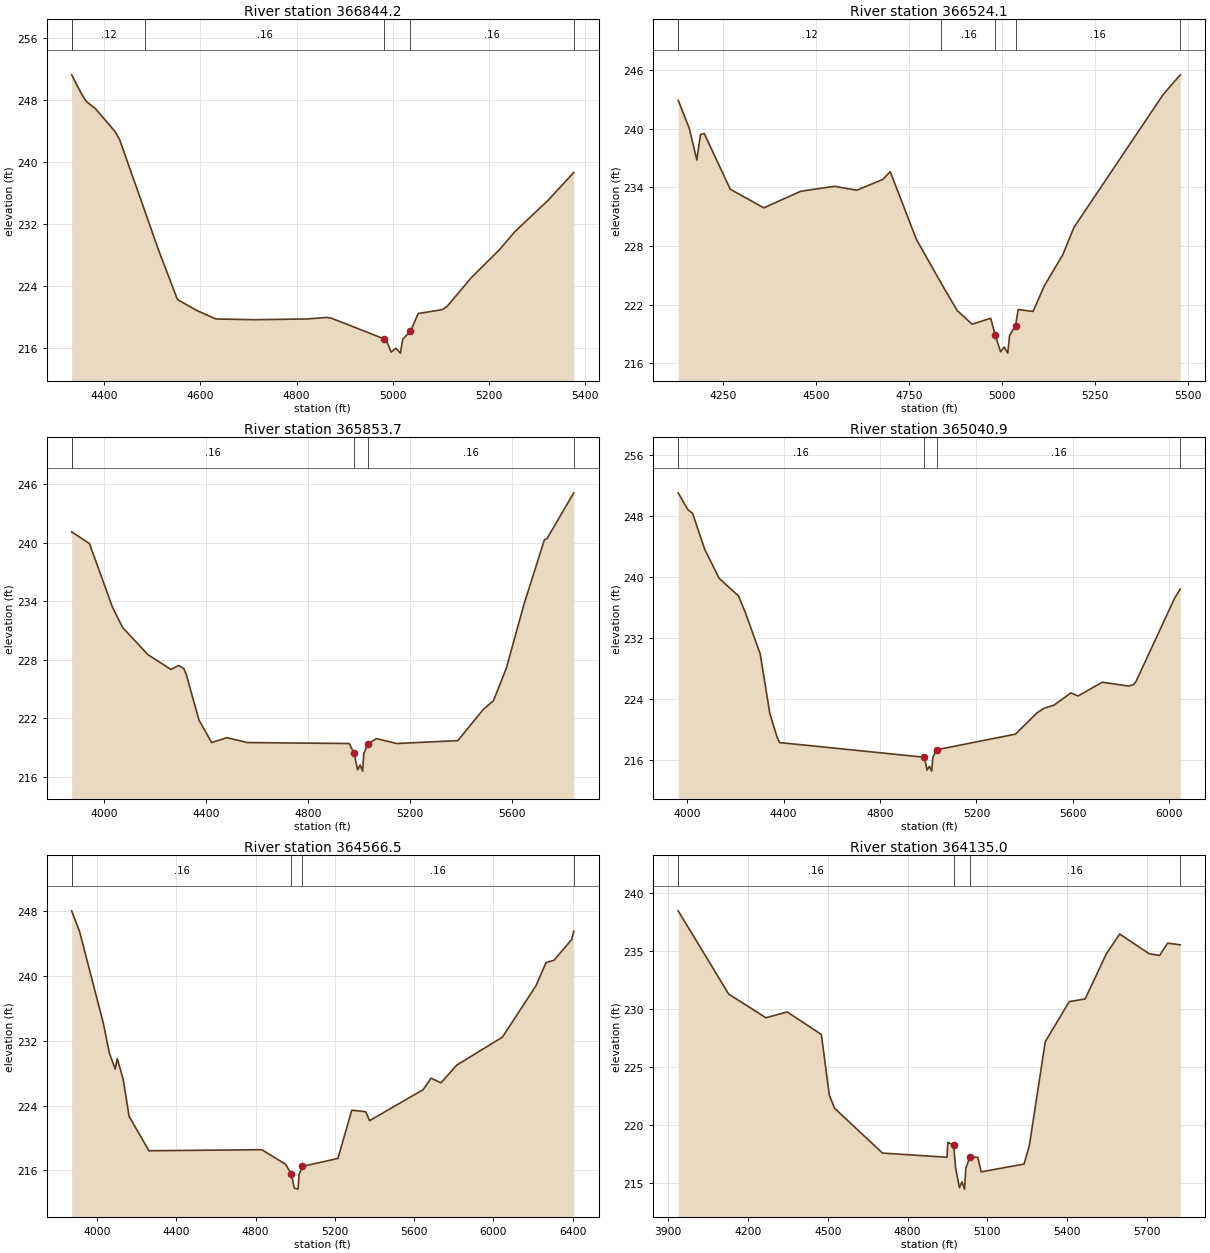
Type RM Length L Ch R = 1 ,366844.2,320.1,320.1,320.1
BEGIN DESCRIPTION:
Cross Section Little River 35.0
END DESCRIPTION:
#Sta/Elev= 30
  4332.2   251.2  4352.2   248.8  4362.2   247.8  4382.2   246.8  4422.2   243.9
  4432.2   242.8  4485.5  233.43  4512.2   228.7  4552.2   222.2  4592.2   220.8
  4632.2   219.7  4712.2   219.6  4822.2   219.7  4862.2   219.9  4872.2   219.8
  4982.2  217.12  4988.7  216.61  4996.5  215.42  5006.2  215.92  5015.7  215.29
  5020.6  217.09  5036.6  218.09  5052.6   220.4  5102.6   220.9  5112.6   221.3
  5162.6     225  5222.6   228.7  5252.6   230.9  5322.6     235  5376.1   238.6
#Mann= 6 , 1 , 0
 4332.20     0.2       0  4332.2    0.12       0  4485.5    0.16       0
  4982.2   0.045       0  5036.6    0.16       0  5376.1     0.2       0
Bank Sta=4982.20,5036.60
Exp/Cntr=0.3,0.1

Type RM Length L Ch R = 1 ,366524.1,670.4,670.4,670.4
BEGIN DESCRIPTION:
Cross Section Little River 34.0
END DESCRIPTION:
#Sta/Elev= 30
  4129.8   242.9  4159.8     240  4179.8   236.8  4189.8   239.4  4199.8   239.5
  4269.8   233.8  4359.8   231.9  4459.8   233.6  4549.8   234.1  4609.8   233.7
  4679.8   234.8  4699.8   235.6  4769.8   228.7  4837.6  224.13  4879.8   221.4
  4919.8     220  4969.8   220.6  4982.2  218.87  4996.5  217.17  5006.2  217.67
  5015.7  217.04  5020.6  218.84  5036.6  219.84  5043.7   221.5  5083.7   221.3
  5113.7   223.9  5163.7   227.1  5193.7   229.9  5433.7   243.5  5479.6   245.5
#Mann= 6 , 1 , 0
 4129.80     0.2       0  4129.8    0.12       0  4837.6    0.16       0
  4982.2   0.045       0  5036.6    0.16       0  5479.6     0.2       0
Bank Sta=4982.20,5036.60
Exp/Cntr=0.3,0.1

Type RM Length L Ch R = 1 ,365853.7,812.8,812.8,812.8
BEGIN DESCRIPTION:
Cross Section Little River 33.0
END DESCRIPTION:
#Sta/Elev= 30
  3871.8   241.1  3941.8   239.9  4031.8   233.4  4071.8   231.3  4171.8   228.5
  4261.8     227  4291.8   227.4  4311.8   227.1  4321.8   226.5  4371.8   221.8
  4421.8   219.5  4481.8     220  4561.8   219.5  4961.8   219.4  4980.8   218.4
  4995.1   216.7  5004.8   217.2  5014.3  216.57  5019.2  218.37  5035.2  219.37
  5068.5   219.9  5148.5   219.4  5388.5   219.7  5488.5   222.9  5528.5   223.8
  5578.5   227.1  5648.5   233.7  5728.5   240.3  5738.5   240.4  5843.6   245.1
#Mann= 5 , 1 , 0
 3871.80     0.2       0  3871.8    0.16       0  4980.8   0.045       0
  5035.2    0.16       0  5843.6     0.2       0
Bank Sta=4980.80,5035.20
Exp/Cntr=0.3,0.1

Type RM Length L Ch R = 1 ,365040.9,474.4,474.4,474.4
BEGIN DESCRIPTION:
Cross Section Little River 32.0
END DESCRIPTION:
#Sta/Elev= 30
  3963.3     251  4003.3   248.8  4023.3   248.3  4073.3   243.6  4133.3   239.8
  4213.3   237.5  4243.3   235.2  4303.3   229.9  4343.3   222.1  4373.3     219
  4383.3   218.3  4980.8  216.39  4987.3  215.88  4995.1  214.69  5004.8  215.19
  5014.3  214.56  5019.2  216.36  5035.2  217.36  5361.4   219.4  5451.4   222.2
  5481.4   222.8  5521.4   223.2  5591.4   224.8  5621.4   224.4  5721.4   226.2
  5831.4   225.7  5851.4   225.9  5861.4   226.3  6021.4   237.2  6045.1   238.4
#Mann= 5 , 1 , 0
 3963.30     0.2       0  3963.3    0.16       0  4980.8   0.045       0
  5035.2    0.16       0  6045.1     0.2       0
Bank Sta=4980.80,5035.20
Exp/Cntr=0.3,0.1

Type RM Length L Ch R = 1 ,364566.5,431.5,431.5,431.5
BEGIN DESCRIPTION:
Cross Section Little River 31.0
END DESCRIPTION:
#Sta/Elev= 30
  3871.5     248  3911.5  245.45  4031.5  234.14  4061.5   230.5  4091.5  228.49
  4101.5   229.8  4131.5  227.27  4161.5  222.67  4261.5  218.43  4831.5  218.56
  4951.5  216.76  4980.8  215.53  4995.1  213.83  5014.3   213.7  5019.2   215.5
  5035.2   216.5  5215.4  217.48  5285.4  223.43  5355.4  223.24  5375.4  222.14
  5645.4  225.96  5685.4  227.37  5735.4   226.8  5815.4  228.99  6045.4  232.43
  6215.4  238.78  6265.4  241.62  6305.4  241.91  6395.4  244.46  6405.6   245.5
#Mann= 5 , 1 , 0
 3871.50     0.2       0  3871.5    0.16       0  4980.8   0.045       0
  5035.2    0.16       0  6405.6     0.2       0
Bank Sta=4980.80,5035.20
Exp/Cntr=0.3,0.1

Type RM Length L Ch R = 1 ,364135.0,532.9,532.9,532.9
BEGIN DESCRIPTION:
Cross Section Little River 30.0 CCX172
END DESCRIPTION:
#Sta/Elev= 30
  3937.3   238.5  4127.3  231.32  4267.3  229.28  4347.3  229.78  4475.8  227.84
  4505.8   222.6  4525.8  221.47  4705.8  217.61  4948.6  217.25  4951.5  218.54
  4973.5  218.28  4980.8  216.33  4995.1  214.63  5004.8  215.13  5014.3   214.5
  5019.2   216.3  5035.2   217.3  5064.6  217.23  5076.9  215.99  5238.1  216.66
  5258.1  218.24  5318.1  227.21  5408.1  230.67  5468.1   230.9  5548.1   234.8
  5598.1   236.5  5708.1  234.81  5748.1  234.65  5778.1  235.71  5826.1  235.57
#Mann= 5 , 1 , 0
 3937.30     0.2       0  3937.3    0.16       0  4973.5   0.045       0
  5035.2    0.16       0  5826.1     0.2       0
Bank Sta=4973.50,5035.20
Exp/Cntr=0.3,0.1

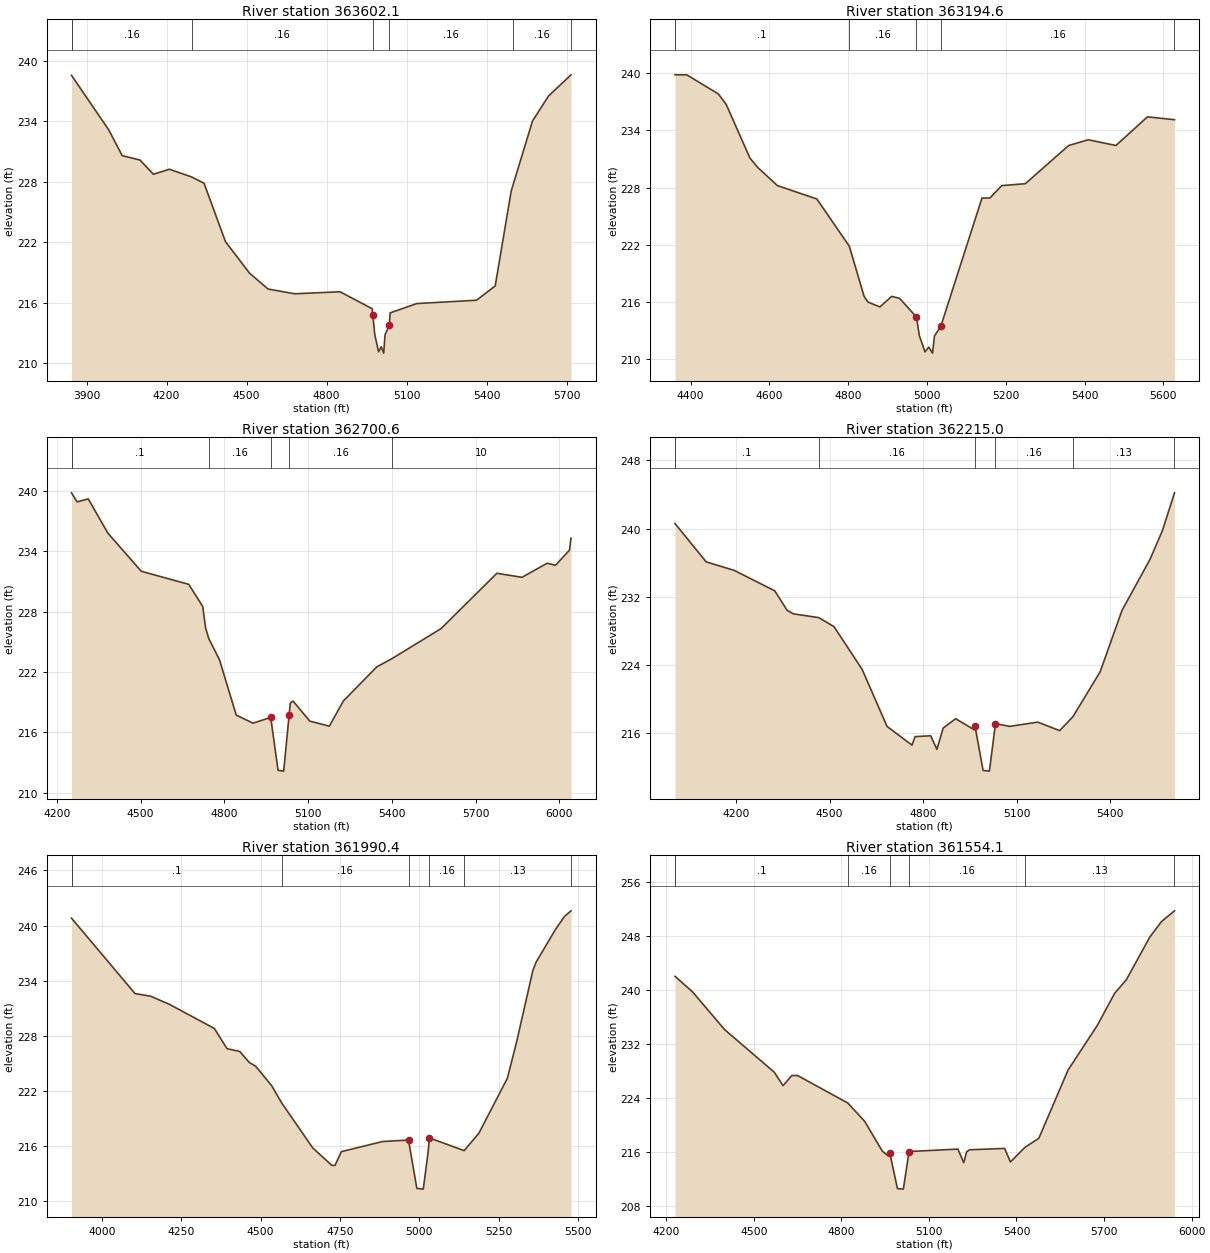
Type RM Length L Ch R = 1 ,363602.1,407.5,407.5,407.5
BEGIN DESCRIPTION:
Cross Section Little River 29.0
END DESCRIPTION:
#Sta/Elev= 30
  3843.7  238.57  3983.7  233.14  4033.7   230.6  4100.7  230.16  4150.7  228.75
  4210.7  229.25  4293.7  228.49  4340.7  227.86  4420.7  222.08  4510.7  218.95
  4580.7  217.36  4680.7  216.89  4850.7  217.09  4970.7  215.41  4973.5  214.78
  4980.8  212.83  4995.1  211.13  5004.8  211.63  5014.3     211  5019.2   212.8
  5035.2   213.8  5038.3  214.99  5138.3  215.92  5362.3  216.25  5432.3  217.67
  5492.3  227.08  5500.2  227.78  5572.3  234.04  5632.3  236.52  5716.5  238.62
#Mann= 7 , 1 , 0
 3843.70     0.2       0  3843.7    0.16       0  4293.7    0.16       0
  4973.5   0.045       0  5035.2    0.16       0  5500.2    0.16       0
  5716.5     0.2       0
Bank Sta=4973.50,5035.20
Exp/Cntr=0.3,0.1

Type RM Length L Ch R = 1 ,363194.6,494,494,494
BEGIN DESCRIPTION:
Cross Section Little River 28.0
END DESCRIPTION:
#Sta/Elev= 30
  4360.6   239.8  4390.6   239.8  4470.6   237.8  4490.6   236.7  4550.6   231.1
  4570.6   230.1  4620.6   228.2  4720.6   226.8    4803  221.86  4840.6   216.6
  4850.6     216  4880.6   215.5  4910.6   216.6  4930.6   216.4  4973.5  214.44
  4980.8  212.49  4995.1  210.79  5004.8  211.29  5014.3  210.66  5019.2  212.46
  5035.2  213.46  5139.8   226.9  5159.8   226.9  5189.8   228.2  5249.8   228.4
  5359.8   232.4  5409.8     233  5479.8   232.4  5559.8   235.4  5628.4   235.1
#Mann= 6 , 1 , 0
 4360.60     0.2       0  4360.6     0.1       0    4803    0.16       0
  4973.5   0.045       0  5035.2    0.16       0  5628.4     0.2       0
Bank Sta=4973.50,5035.20
Exp/Cntr=0.3,0.1

Type RM Length L Ch R = 1 ,362700.6,485.6,485.6,485.6
BEGIN DESCRIPTION:
Cross Section Little River 27.0
END DESCRIPTION:
#Sta/Elev= 30
  4252.6   239.8  4272.6   238.9  4312.6   239.2  4382.6   235.8  4502.6     232
  4672.6   230.7  4722.6   228.5  4732.6   226.4  4743.9  225.33  4782.6   223.2
  4842.6   217.7  4902.6   216.9  4966.1  217.47  4992.3  212.21  5012.5  212.13
    5032   217.7  5036.1   218.9  5046.1   219.1  5106.1   217.1  5176.1   216.6
  5226.1   219.1  5346.1   222.5    5400  223.31  5576.1   226.3  5776.1   231.8
  5866.1   231.4  5956.1   232.8  5986.1   232.6  6036.1   234.1  6041.5   235.3
#Mann= 6 , 1 , 0
 4252.60     0.2       0  4252.6     0.1       0  4743.9    0.16       0
  4966.1   0.045       0    5032    0.16       0    5400      10       0
Bank Sta=4966.10,5032.00
Exp/Cntr=0.3,0.1

Type RM Length L Ch R = 1 ,362215.0,224.6,224.6,224.6
BEGIN DESCRIPTION:
Cross Section Little River 26.0
END DESCRIPTION:
#Sta/Elev= 30
  4004.2   240.6  4104.2   236.1  4194.2   235.1  4324.2   232.7  4364.2   230.4
  4384.2     230  4465.3  229.56  4514.2   228.5  4604.2   223.5  4684.2   216.8
  4764.2   214.6  4774.2   215.6  4824.2   215.7  4844.2   214.1  4864.2   216.6
  4904.2   217.7  4964.2   216.4  4966.1  216.89  4992.3  211.63  5012.5  211.55
    5032  217.12  5077.7   216.8  5167.7   217.3  5237.7   216.3  5279.9  217.91
  5367.7   223.2  5437.7   230.4  5527.7   236.4  5567.7   239.8  5606.1   244.2
#Mann= 7 , 1 , 0
 4004.20     0.2       0  4004.2     0.1       0  4465.3    0.16       0
  4966.1    0.05       0    5032    0.16       0  5279.9    0.13       0
  5606.1     0.2       0
Bank Sta=4966.10,5032.00
Exp/Cntr=0.3,0.1

Type RM Length L Ch R = 1 ,361990.4,436.3,436.3,436.3
BEGIN DESCRIPTION:
Cross Section Little River 25.0
END DESCRIPTION:
#Sta/Elev= 30
  3904.5   240.8  4104.5   232.6  4154.5   232.3  4214.5   231.4  4354.5   228.8
  4394.5   226.6  4434.5   226.3  4464.5   225.1  4484.5   224.7  4534.5   222.6
  4566.6   220.7  4664.5   215.8  4724.5   213.9  4734.5   213.9  4754.5   215.4
  4884.5   216.5  4966.1  216.66  4992.3   211.4  5012.5  211.32  5027.8  215.34
    5032  216.89  5141.3  215.51  5187.7   217.4  5277.7   223.4  5307.7   227.5
  5357.7   235.1  5367.7     236  5427.7   239.5  5457.7     241  5477.9   241.6
#Mann= 7 , 1 , 0
 3904.50     0.2       0  3904.5     0.1       0  4566.6    0.16       0
  4966.1    0.05       0    5032    0.16       0  5141.3    0.13       0
  5477.9     0.2       0
Bank Sta=4966.10,5032.00
Exp/Cntr=0.3,0.1

Type RM Length L Ch R = 1 ,361554.1,871,871,871
BEGIN DESCRIPTION:
Cross Section Little River 24.0
END DESCRIPTION:
#Sta/Elev= 30
  4230.3     242  4290.3   239.7  4400.3   234.1  4570.3   227.8  4600.3   225.8
  4630.3   227.3  4650.3   227.3  4822.1  223.23  4880.3   220.5  4940.3   216.1
  4960.3   215.4  4966.1  215.81  4992.3  210.55  5012.5  210.47    5032  216.04
  5199.3   216.4  5219.3   214.4  5229.3     216  5239.3   216.3  5359.3   216.5
  5379.3   214.5    5429  216.66  5476.5     218  5576.5   228.1  5676.5   234.7
  5736.5   239.5  5776.5   241.5  5856.5   247.8  5896.5   250.1  5941.2   251.7
#Mann= 7 , 1 , 0
 4230.30     0.2       0  4230.3     0.1       0  4822.1    0.16       0
  4966.1    0.05       0    5032    0.16       0    5429    0.13       0
  5941.2     0.2       0
Bank Sta=4966.10,5032.00
Exp/Cntr=0.3,0.1

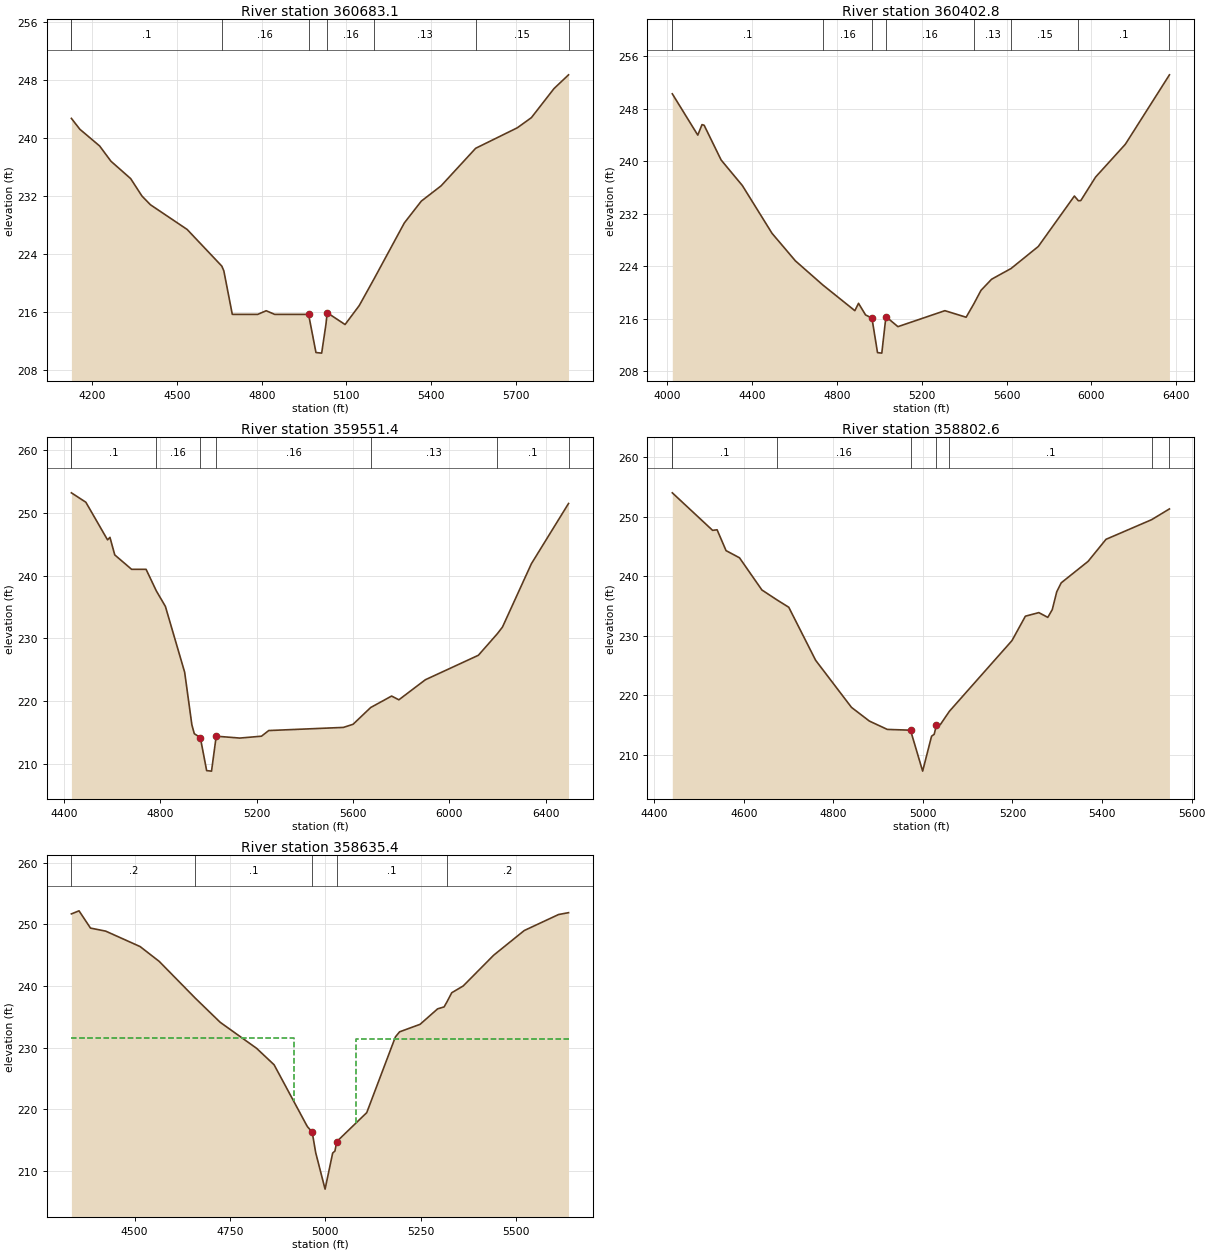
Type RM Length L Ch R = 1 ,360683.1,280.3,280.3,280.3
BEGIN DESCRIPTION:
Cross Section Little River 23.0
END DESCRIPTION:
#Sta/Elev= 30
  4125.9   242.7  4155.9   241.2  4225.9   238.9  4265.9   236.8  4335.9   234.4
  4375.9     232  4405.9   230.8  4535.9   227.4  4658.7  222.35  4665.9   221.7
  4695.9   215.7  4785.9   215.7  4815.9   216.2  4845.9   215.7  4966.1   215.7
  4992.3  210.44  5012.5  210.36  5027.8  214.38    5032  215.93  5095.4   214.3
  5145.4   216.9  5197.9  220.58  5305.4   228.3  5365.4   231.3  5435.4   233.4
    5558  238.58  5705.4   241.4  5755.4   242.8  5835.4   246.8    5887   248.7
#Mann= 8 , 1 , 0
 4125.90     0.2       0  4125.9     0.1       0  4658.7    0.16       0
  4966.1    0.05       0    5032    0.16       0  5197.9    0.13       0
    5558    0.15       0    5887     0.2       0
Bank Sta=4966.10,5032.00
Exp/Cntr=0.3,0.1

Type RM Length L Ch R = 1 ,360402.8,851.4,851.4,851.4
BEGIN DESCRIPTION:
Cross Section Little River 22.0 CCX171
END DESCRIPTION:
#Sta/Elev= 30
  4025.6   250.3  4145.6     244  4165.6   245.6  4175.6   245.5  4255.6   240.2
  4355.6   236.3  4495.6     229  4605.6   224.8  4734.8  221.12  4885.6   217.2
  4902.9  218.32  4936.1  216.55  4966.1  216.06  4992.3   210.8  5012.5  210.72
    5032  216.29  5088.5  214.76  5309.8   217.2  5409.8   216.2  5446.2  218.25
  5479.8   220.3  5529.8     222  5621.6  223.64  5749.8     227  5919.8   234.7
  5938.6  233.98  5949.8     234  6019.8   237.6  6159.8   242.6  6367.6   253.2
#Mann= 9 , 1 , 0
 4025.60     0.2       0  4025.6     0.1       0  4734.8    0.16       0
  4966.1    0.05       0    5032    0.16       0  5446.2    0.13       0
  5621.6    0.15       0  5938.6     0.1       0  6367.6     0.2       0
Bank Sta=4966.10,5032.00
Exp/Cntr=0.3,0.1

Type RM Length L Ch R = 1 ,359551.4,748.8,748.8,748.8
BEGIN DESCRIPTION:
Cross Section Little River 21.0
END DESCRIPTION:
#Sta/Elev= 30
    4431   253.2    4491   251.7    4581   245.7    4591   246.1    4611   243.3
    4681     241    4741     241  4783.5  237.56    4821   235.1    4901   224.6
    4931   216.2    4941   214.8  4966.1  214.17  4992.3  208.91  5012.5  208.83
    5032   214.4  5129.9   214.1  5219.9   214.4  5249.9   215.3  5559.9   215.8
  5599.9   216.3  5672.9  218.97  5759.9   220.8  5789.9   220.2  5899.9   223.4
  6119.9   227.3  6198.4  230.73  6219.9   231.8  6339.9   241.9    6494   251.5
#Mann= 8 , 1 , 0
 4431.00     0.2       0    4431     0.1       0  4783.5    0.16       0
  4966.1    0.05       0    5032    0.16       0  5672.9    0.13       0
  6198.4     0.1       0    6494     0.2       0
Bank Sta=4966.10,5032.00
Exp/Cntr=0.3,0.1

Type RM Length L Ch R = 1 ,358802.6,167.2,167.2,167.2
BEGIN DESCRIPTION:
Cross Section Little River 20.0
END DESCRIPTION:
#Sta/Elev= 30
  4440.5     254  4530.5   247.7  4540.5   247.8  4560.5   244.3  4590.5   243.1
  4640.5   237.7  4674.9     236  4700.5   234.8  4760.5   225.9  4840.5     218
  4880.5   215.7  4920.5   214.3  4972.3  214.17  4999.4   207.3  5019.3  213.16
  5025.2  213.48  5030.2  215.03  5038.8   215.1  5059.1  217.34  5198.8   229.2
  5228.8   233.3  5258.8   233.9  5278.8   233.1  5288.8   234.4  5298.8   237.4
  5308.8   238.9  5368.8   242.5  5408.8   246.2  5510.5  249.49  5550.4   251.3
#Mann= 8 , 1 , 0
 4440.50     0.2       0  4440.5     0.1       0  4674.9    0.16       0
  4972.3    0.05       0  5030.2    0.16       0  5059.1     0.1       0
  5510.5    0.16       0  5550.4     0.2       0
Bank Sta=4972.30,5030.20
Exp/Cntr=0.5,0.3

Type RM Length L Ch R = 1 ,358635.4,53,53,53
BEGIN DESCRIPTION:
Upstream Section of Bridge/Culvert/Weir
END DESCRIPTION:
#Sta/Elev= 30
  4334.5  251.72  4354.5  252.22  4384.5  249.42  4424.5  248.92  4514.5  246.42
  4564.5  244.02  4659.2  238.04  4724.5  234.12    4820  229.89  4865.8  227.22
  4952.9  217.19  4965.6   216.3  4974.9  212.93  4999.4  207.03  5019.3  212.89
  5025.2  213.21  5030.2  214.76  5108.6  219.45  5183.7  231.74  5194.6  232.57
  5248.4  233.79  5294.3   236.3  5311.4  236.62  5319.4   237.5  5331.4  238.92
  5361.4  240.02  5441.4  245.02  5521.4  249.02  5611.4  251.62  5637.5  251.92
#Mann= 5 , 1 , 0
 4334.50     0.2       0  4659.2     0.1       0  4965.6    0.05       0
  5030.2     0.1       0  5319.4     0.2       0
#XS Ineff= 2 , 0
       0  4916.9   231.5    5081       0   231.4
Bank Sta=4965.60,5030.20
Exp/Cntr=0.5,0.3