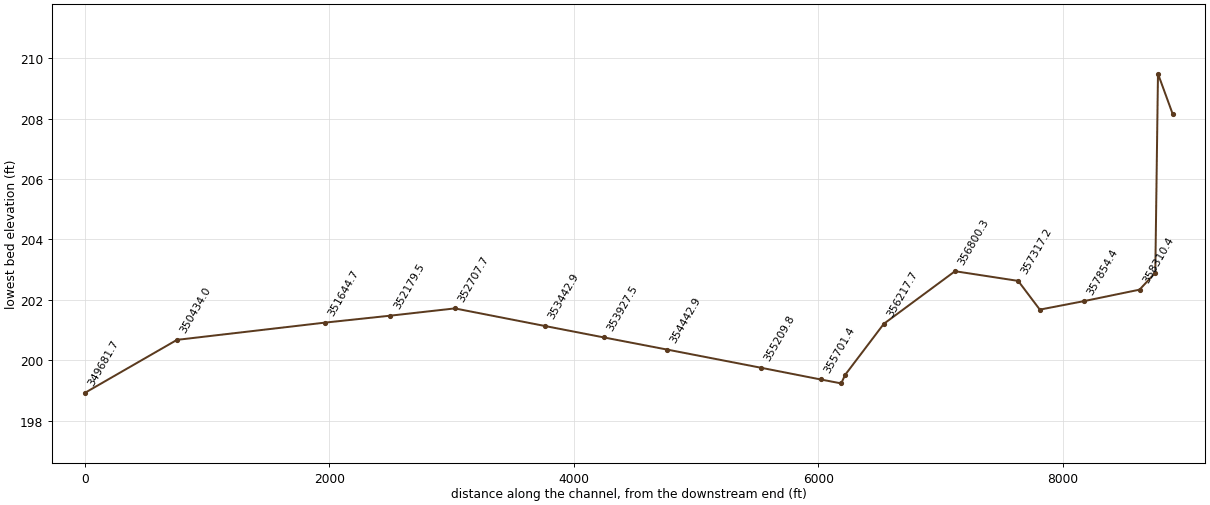
HEC-RAS study Little_River_FINAL.prj: Little River Detail Study

--- Little_River_FINAL.g01 (geometry) --- (continued)

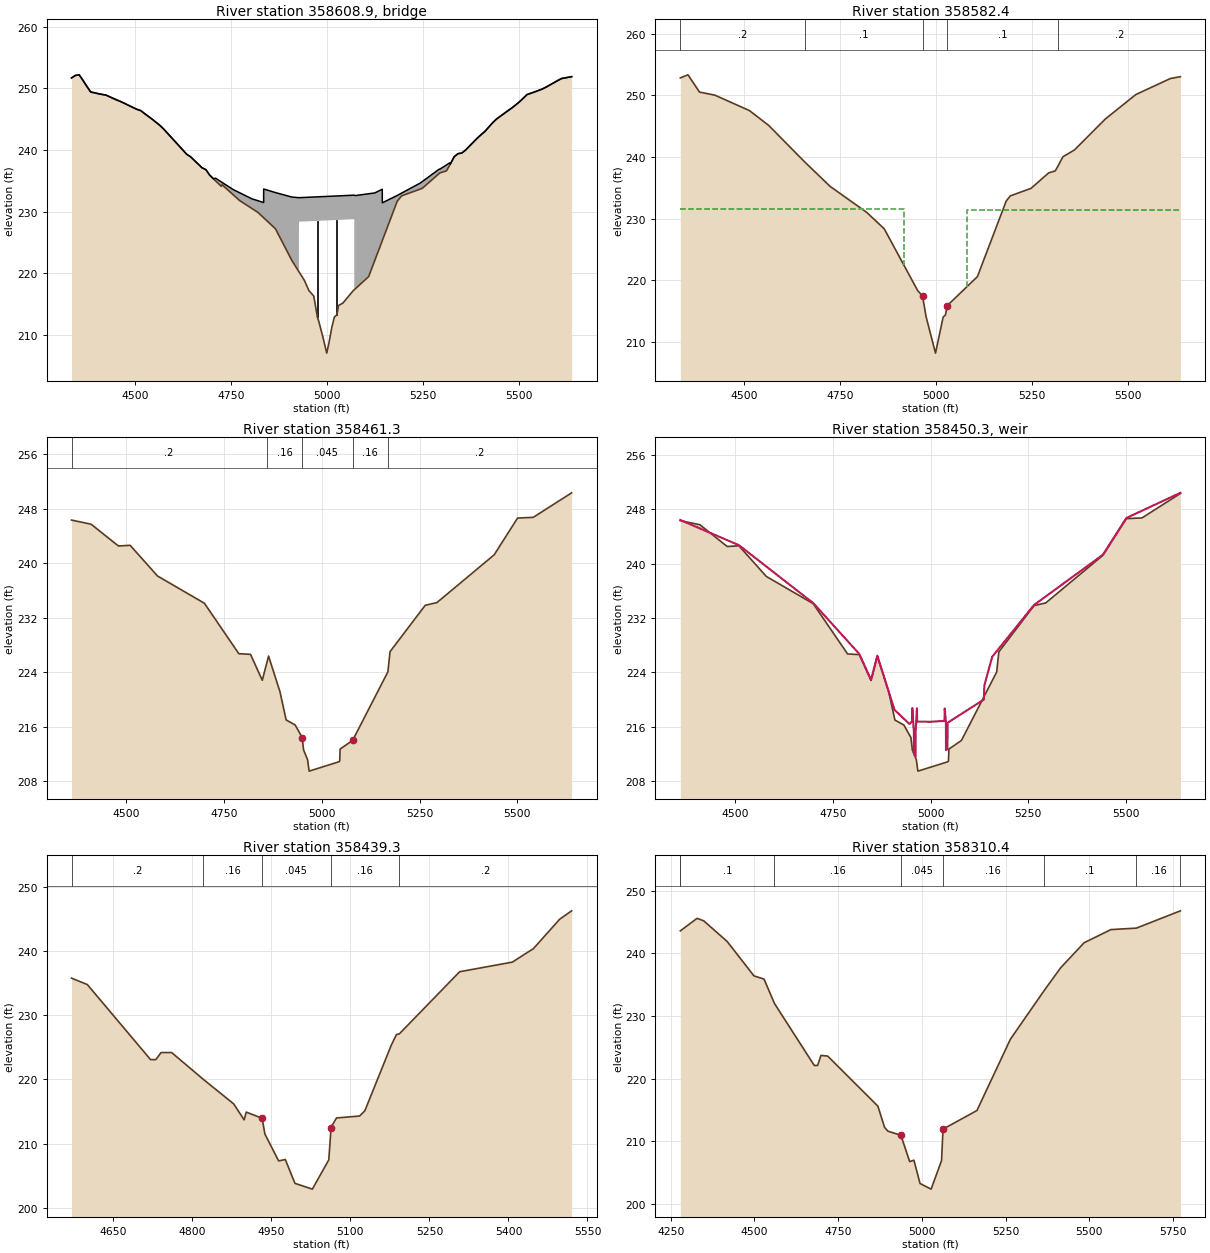
Type RM Length L Ch R = 3 ,358608.9,,,
BEGIN DESCRIPTION:
MACK-TODD RD
Structure ID: WK_LITR3
END DESCRIPTION:
Bridge Culvert--1,0,-1,-1, 0
Deck Dist Width WeirC Skew NumUp NumDn MinLoCord MaxHiCord MaxSubmerge Is_Ogee
10,33,2.6,, 60, 60,,,0.95,0,1,1,,
  4334.5  4344.5  4354.5  4384.5  4424.5  4464.5  4504.5  4514.5  4544.5  4564.5
  4574.5  4634.5  4644.5  4674.5  4684.5  4694.5  4704.5  4709.7  4724.5    4727
  4756.2  4772.5  4804.2    4820 4834.99  4835.1  4865.8  4908.7 4927.01  4927.1
 5071.09  5071.2  5073.8  5108.6  5124.5  5144.1 5144.21  5183.1  5194.6  5243.7
  5248.4  5292.3  5294.3  5311.4  5319.4  5321.4  5331.4  5341.4  5351.4  5361.4
  5391.4  5411.4  5431.4  5441.4  5481.4  5501.4  5521.4  5561.4  5611.4  5637.5
   251.7   252.1   252.2   249.4   248.9   247.8   246.6   246.4     245     244
   243.4   239.3   238.9  237.11  236.81  235.91  235.31  235.42  234.82  234.72
  233.55  233.05  232.07  231.76  231.46  233.66  233.08  232.35  232.25  232.25
  232.66  232.66  232.59  232.89  233.02  233.62  231.42  232.61     233  234.65
  234.87  236.88  236.89  237.57   237.9   237.7   238.9   239.4   239.5     240
   241.9     243   244.4     245   246.8   247.8     249   249.9   251.6   251.9
   251.7   252.1   252.2   249.4   248.9   247.8   246.6   246.4     245     244
   243.4   239.3   238.9   237.1   236.8   235.9   235.3  234.99   234.1  234.34
   232.7  231.78  230.51  229.87     229  228.99   227.2  222.04  220.23  228.35
  228.76   217.3  217.45  219.43  222.04  225.26  225.28  231.67  232.55  233.66
  233.77  236.17  236.28   236.6  237.48   237.7   238.9   239.4   239.5     240
   241.9     243   244.4     245   246.8   247.8     249   249.9   251.6   251.9
  4334.5  4344.5  4354.5  4384.5  4424.5  4464.5  4504.5  4514.5  4544.5  4564.5
  4574.5  4634.5  4644.5  4674.5  4684.5  4694.5  4704.5  4709.7  4724.5    4727
  4756.2  4772.5  4804.2    4820 4834.99  4835.1  4865.8  4908.7 4927.01  4927.1
 5071.09  5071.2  5073.8  5108.6  5124.5  5144.1 5144.21  5183.1  5194.6  5243.7
  5248.4  5292.3  5294.3  5311.4  5319.4  5321.4  5331.4  5341.4  5351.4  5361.4
  5391.4  5411.4  5431.4  5441.4  5481.4  5501.4  5521.4  5561.4  5611.4  5637.5
   251.7   252.1   252.2   249.4   248.9   247.8   246.6   246.4     245     244
   243.4   239.3   238.9  237.11  236.81  235.91  235.31  235.42  234.82  234.72
  233.55  233.05  232.07  231.76  231.46  233.66  233.08  232.35  232.25  232.25
  232.66  232.66  232.59  232.89  233.02  233.62  231.42  232.61     233  234.65
  234.87  236.88  236.89  237.57   237.9   237.7   238.9   239.4   239.5     240
   241.9     243   244.4     245   246.8   247.8     249   249.9   251.6   251.9
   251.6     252   252.1   249.3   248.8   247.7   246.5   246.3   244.9   243.9
   243.3   239.2   238.8     237   236.7   235.8   235.2  234.89     234  234.24
   232.6  231.68  230.41  229.77   228.9  228.89   227.1  221.94  220.13  228.25
  228.66   217.2  217.35  219.33  221.94  225.16  225.18  231.57  232.45  233.56
  233.67  236.07  236.18   236.5  237.38   237.6   238.8   239.3   239.4   239.9
   241.8   242.9   244.3   244.9   246.7   247.7   248.9   249.8   251.5   251.8
Pier Skew, UpSta & Num, DnSta & Num=,4974.9, 2 ,4974.9, 2 , 0 , 0 , 0 ,,
       3       3
  211.61  229.49
       3       3
  211.51  229.39
Pier Skew, UpSta & Num, DnSta & Num=,5025.2, 2 ,5025.2, 2 , 0 , 0 , 0 ,,
       3       3
  212.11  229.64
       3       3
  212.01  229.54
BR Coef= 1 , 1 , 0 ,1.25, 0 ,,,0.8,0,2,0,
Wspro=,,,, 1 ,,,, 0 ,,,, 0 ,,,,-1 ,-1 ,-1 , 0 , 0 , 0 , 0 , 0
BC Design=,, 0 ,, 0 ,,,,,,
BR U #Sta/Elev= 114
  4334.5   251.7  4344.5   252.1  4354.5   252.2  4364.5   251.3  4374.5   250.3
  4384.5   249.4  4394.5   249.3  4404.5   249.1  4414.5     249  4424.5   248.9
  4434.5   248.6  4444.5   248.3  4464.5   247.8  4474.5   247.5  4484.5   247.2
  4494.5   246.9  4504.5   246.6  4514.5   246.4  4524.5   245.9  4544.5     245
  4554.5   244.5  4564.5     244  4574.5   243.4  4624.5     240  4634.5   239.3
  4644.5   238.9  4659.2  238.02  4674.5   237.1  4679.2  236.96  4684.5   236.8
  4689.2  236.38  4694.5   235.9  4699.2  235.62  4704.5   235.3  4709.7  234.99
  4714.5   234.7  4724.5   234.1    4727  234.34  4756.2   232.7  4772.5  231.78
  4804.2  230.51    4820  229.87 4834.99     229  4835.1  228.99 4835.21  228.98
  4855.2  227.82  4865.8   227.2  4905.7   222.4  4908.7  222.04  4922.6  220.66
  4926.9  220.24 4927.01  220.23  4927.1  220.22  4927.2  220.21  4941.3  218.81
  4952.9  217.17  4965.6  216.28  4972.3  213.88  4974.9  212.91  4979.2  212.05
  4989.6  209.58  4999.4  207.01  5005.4  208.74  5012.6  211.17  5019.3  212.87
  5025.2  213.19  5027.6  213.82  5030.2  214.74  5041.7  215.15  5067.7   217.1
    5071  217.29 5071.09  217.29  5071.2   217.3  5071.3  217.31  5073.8  217.45
  5108.6  219.43  5124.5  222.04 5143.99  225.24  5144.1  225.26 5144.21  225.28
  5183.1  231.67  5183.7  231.72  5194.6  232.55  5243.7  233.66  5248.4  233.77
  5292.3  236.17  5294.3  236.28    5295  236.29  5311.4   236.6  5319.4  237.48
  5321.4   237.7  5331.4   238.9  5341.4   239.4  5351.4   239.5  5361.4     240
  5391.4   241.9  5401.4   242.5  5411.4     243  5421.4   243.7  5431.4   244.4
  5441.4     245  5471.4   246.4  5481.4   246.8  5491.4   247.3  5501.4   247.8
  5511.4   248.4  5521.4     249  5531.4   249.2  5541.4   249.4  5561.4   249.9
  5571.4   250.2  5601.4   251.3  5611.4   251.6  5637.5   251.9
BR U #Mann= 5
 4334.50     0.2  4659.2     0.1  4965.6    0.05  5030.2     0.1  5319.4     0.2
BR U Banks=4965.60,5030.20
BR D #Sta/Elev= 114
  4334.5   251.6  4344.5     252  4354.5   252.1  4364.5   251.2  4374.5   250.2
  4384.5   249.3  4394.5   249.2  4404.5     249  4414.5   248.9  4424.5   248.8
  4434.5   248.5  4444.5   248.2  4464.5   247.7  4474.5   247.4  4484.5   247.1
  4494.5   246.8  4504.5   246.5  4514.5   246.3  4524.5   245.8  4544.5   244.9
  4554.5   244.4  4564.5   243.9  4574.5   243.3  4624.5   239.9  4634.5   239.2
  4644.5   238.8  4659.2  237.92  4674.5     237  4679.2  236.86  4684.5   236.7
  4689.2  236.28  4694.5   235.8  4699.2  235.52  4704.5   235.2  4709.7  234.89
  4714.5   234.6  4724.5     234    4727  234.24  4756.2   232.6  4772.5  231.68
  4804.2  230.41    4820  229.77 4834.99   228.9  4835.1  228.89 4835.21  228.88
  4855.2  227.72  4865.8   227.1  4905.7   222.3  4908.7  221.94  4922.6  220.56
  4926.9  220.14 4927.01  220.13  4927.1  220.12  4927.2  220.11  4941.3  218.71
  4952.9  217.07  4965.6  216.18  4972.3  213.78  4974.9  212.81  4979.2  211.95
  4989.6  209.48  4999.4  206.91  5005.4  208.64  5012.6  211.07  5019.3  212.77
  5025.2  213.09  5027.6  213.72  5030.2  214.64  5041.7  215.05  5067.7     217
    5071  217.19 5071.09  217.19  5071.2   217.2  5071.3  217.21  5073.8  217.35
  5108.6  219.33  5124.5  221.94 5143.99  225.14  5144.1  225.16 5144.21  225.18
  5183.1  231.57  5183.7  231.62  5194.6  232.45  5243.7  233.56  5248.4  233.67
  5292.3  236.07  5294.3  236.18    5295  236.19  5311.4   236.5  5319.4  237.38
  5321.4   237.6  5331.4   238.8  5341.4   239.3  5351.4   239.4  5361.4   239.9
  5391.4   241.8  5401.4   242.4  5411.4   242.9  5421.4   243.6  5431.4   244.3
  5441.4   244.9  5471.4   246.3  5481.4   246.7  5491.4   247.2  5501.4   247.7
  5511.4   248.3  5521.4   248.9  5531.4   249.1  5541.4   249.3  5561.4   249.8
  5571.4   250.1  5601.4   251.2  5611.4   251.5  5637.5   251.8
BR D #Mann= 5
 4334.50     0.2  4659.2     0.1  4965.6    0.05  5030.2     0.1  5319.4     0.2
BR D Banks=4965.60,5030.20

Type RM Length L Ch R = 1 ,358582.4,121.1,121.1,121.1
BEGIN DESCRIPTION:
Downstream Section of Bridge/Culvert/Weir
END DESCRIPTION:
#Sta/Elev= 30
  4334.5  252.83  4354.5  253.33  4384.5  250.53  4424.5  250.03  4514.5  247.53
  4564.5  245.13  4659.2  239.15  4724.5  235.23    4820     231  4865.8  228.33
  4952.9   218.3  4965.6  217.41  4974.9  214.04  4999.4  208.14  5019.3     214
  5025.2  214.32  5030.2  215.87  5108.6  220.56  5183.7  232.85  5194.6  233.68
  5248.4   234.9  5294.3  237.41  5311.4  237.73  5319.4  238.61  5331.4  240.03
  5361.4  241.13  5441.4  246.13  5521.4  250.13  5611.4  252.73  5637.5  253.03
#Mann= 5 , 1 , 0
 4334.50     0.2       0  4659.2     0.1       0  4965.6    0.05       0
  5030.2     0.1       0  5319.4     0.2       0
#XS Ineff= 2 , 0
       0  4916.9   231.5    5081       0   231.4
Bank Sta=4965.60,5030.20
Exp/Cntr=0.5,0.3

Type RM Length L Ch R = 1 ,358461.3,22,22,22
BEGIN DESCRIPTION:
Upstream Section of Bridge/Culvert/Weir
END DESCRIPTION:
#Sta/Elev= 30
  4359.4  246.31  4409.4  245.71  4479.4  242.51  4509.4  242.61  4579.4  238.11
  4699.4  234.11  4787.5  226.71  4817.5  226.61  4847.5  222.81  4858.9  225.32
  4863.6  226.36  4892.8  221.13  4908.6  216.99  4931.6  216.26  4949.6  214.41
  4953.2  212.59  4963.4  211.17  4967.4  209.48    5043  210.84  5045.6  210.95
  5046.8  212.72  5078.8  213.99    5169  224.05  5174.5  227.01  5264.5  233.81
  5294.5  234.21  5440.9  241.21  5500.9  246.61  5540.9  246.71  5639.2  250.31
#Mann= 5 , 1 , 0
 4359.40     0.2       0  4858.9    0.16       0  4949.6   0.045       0
  5078.8    0.16       0    5169     0.2       0
#XS Ineff= 2 , 0
       0  4939.2   211.6  5088.4       0   212.6
Bank Sta=4949.60,5078.80
Exp/Cntr=0.5,0.3

Type RM Length L Ch R = 5 ,358450.3,,,
BEGIN DESCRIPTION:
Dam D/S Mack Todd Rd
Structure ID: WK_LITR3DAM
END DESCRIPTION:
#Inline Weir SE= 30
  4359.4   246.4  4509.4   242.7  4699.4   234.2  4817.5   226.7  4847.5   222.9
  4863.6  226.46  4907.5  218.49  4945.8  216.41  4952.4  216.79    4953  218.76
    4957  215.34  4957.2  212.13  4961.2  211.58  4961.6  215.31    4965  218.72
  4965.4  216.76  4999.6  216.74  5035.5  216.86  5036.1   218.7  5039.2  216.57
  5039.3  212.58    5043  212.72  5043.3  216.59  5136.2     220  5137.6   222.1
  5157.6   226.3  5264.5   233.9  5440.9   241.3  5500.9   246.7  5639.2   250.4
IW Dist,WD,Coef,Skew,MaxSub,Min_El,Is_Ogee,SpillHt,DesHd
10.0,2.0,3.0,,0.95,, 0 ,,,1.0,1.0,

Type RM Length L Ch R = 1 ,358439.3,128.9,128.9,128.9
BEGIN DESCRIPTION:
Cross Section FIELD_DS
Located At: US 64
END DESCRIPTION:
#Sta/Elev= 30
  4570.6   235.8  4600.6   234.8  4720.6   223.1  4730.6   223.1  4740.6   224.2
  4760.6   224.2  4820.6  220.03  4878.3   216.2  4898.3   213.7  4902.2  214.91
  4932.3  213.96  4937.7  211.49  4963.7   207.3  4976.4  207.52  4994.7   203.8
  5027.7   202.9  5058.9  207.46  5062.4  211.48  5062.5  212.46  5073.6     214
  5117.3   214.3  5127.3   215.1  5177.3   225.3  5187.3     227  5192.8  227.11
  5307.3   236.8  5407.3   238.3  5447.3   240.4  5497.3     245  5519.9   246.3
#Mann= 5 , 1 , 0
 4570.60     0.2       0  4820.6    0.16       0  4932.3   0.045       0
  5062.5    0.16       0  5192.8     0.2       0
Bank Sta=4932.30,5062.50
Exp/Cntr=0.3,0.1

Type RM Length L Ch R = 1 ,358310.4,456,456,456
BEGIN DESCRIPTION:
Cross Section Little River 19.0
END DESCRIPTION:
#Sta/Elev= 30
  4278.8   243.6  4328.8   245.6  4348.8   245.2  4418.8   241.9  4498.8   236.4
  4528.8   235.9  4559.9     232  4678.8   222.1  4688.8   222.1  4698.8   223.7
  4718.8   223.6  4868.8   215.6  4888.8   212.2  4898.8   211.6  4937.7  210.93
  4963.7  206.74  4976.4  206.96  4994.7  203.24  5027.7  202.34  5058.9   206.9
  5062.4  210.92  5062.5   211.9  5164.6   214.9  5264.6   226.3  5364.5     234
  5414.6   237.7  5484.6   241.7  5564.6   243.8  5640.9  244.04  5772.2   246.8
#Mann= 8 , 1 , 0
 4278.80     0.2       0  4278.8     0.1       0  4559.9    0.16       0
  4937.7   0.045       0  5062.5    0.16       0  5364.5     0.1       0
  5640.9    0.16       0  5772.2     0.2       0
Bank Sta=4937.70,5062.50
Exp/Cntr=0.3,0.1

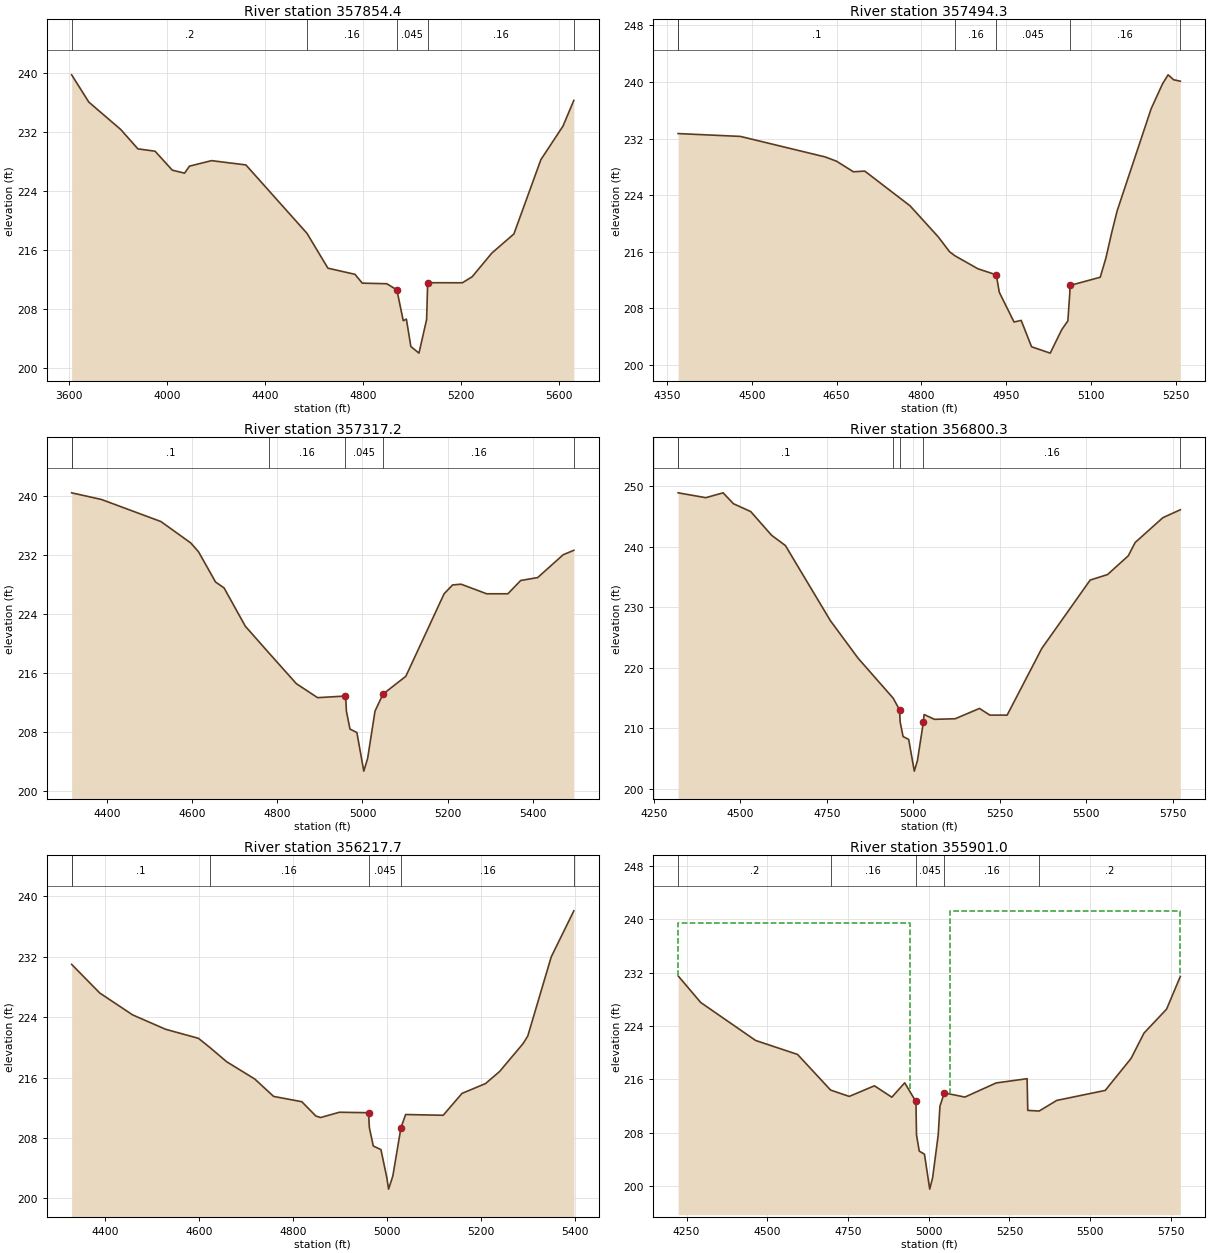
Type RM Length L Ch R = 1 ,357854.4,360.1,360.1,360.1
BEGIN DESCRIPTION:
Cross Section Little River 18.0
END DESCRIPTION:
#Sta/Elev= 30
  3612.5  239.74  3682.5  236.04  3812.5  232.32  3882.5  229.69  3952.5  229.37
  4022.5   226.8  4072.5  226.39  4092.5  227.34  4182.5  228.09  4322.5  227.51
  4571.3  218.23  4656.8  213.49  4766.8  212.66  4796.8  211.46  4896.8  211.38
  4937.7  210.55  4963.7  206.36  4976.4  206.58  4994.7  202.86  5027.7  201.96
  5058.9  206.52  5062.4  210.54  5062.5  211.52  5204.6  211.51  5244.6  212.33
  5324.6  215.54  5414.6  218.14  5524.6  228.23  5614.6  232.78  5658.8  236.27
#Mann= 5 , 1 , 0
 3612.50     0.2       0  4571.3    0.16       0  4937.7   0.045       0
  5062.5    0.16       0  5658.8     0.2       0
Bank Sta=4937.70,5062.50
Exp/Cntr=0.3,0.1

Type RM Length L Ch R = 1 ,357494.3,177.1,177.1,177.1
BEGIN DESCRIPTION:
Cross Section Little River 17.0
END DESCRIPTION:
#Sta/Elev= 30
  4369.8   232.7  4479.8   232.3  4629.8   229.4  4649.8   228.8  4679.8   227.3
  4699.8   227.4  4779.8   222.5  4829.8   218.1  4849.8     216  4858.9  215.45
  4899.8   213.6  4932.3  212.74  4937.7  210.27  4963.7  206.08  4976.4   206.3
  4994.7  202.58  5027.7  201.68  5047.9  204.97  5058.9  206.24  5062.4  210.26
  5062.5  211.24  5116.1   212.4  5126.1   215.1  5136.1   218.6  5146.1   221.8
  5206.1   236.2  5226.1   239.7  5236.1     241  5246.1   240.3  5257.7   240.1
#Mann= 6 , 1 , 0
 4369.80     0.2       0  4369.8     0.1       0  4858.9    0.16       0
  4932.3   0.045       0  5062.5    0.16       0  5257.7     0.2       0
Bank Sta=4932.30,5062.50
Exp/Cntr=0.3,0.1

Type RM Length L Ch R = 1 ,357317.2,516.9,516.9,516.9
BEGIN DESCRIPTION:
Cross Section Little River 16.0
END DESCRIPTION:
#Sta/Elev= 30
  4316.3   240.4  4386.3   239.5  4526.3   236.5  4596.3   233.6  4614.6   232.4
  4654.6   228.3  4674.6   227.5  4724.6   222.3  4780.4  218.65  4844.6   214.5
  4894.6   212.6  4959.8  212.82  4960.5  212.76  4962.3  210.76  4970.7  208.34
  4986.9  207.87  5003.2  202.63  5012.3  204.39  5029.5  210.77  5048.3  213.08
    5102   215.5    5192   226.7    5212   227.9    5232     228    5292   226.7
    5342   226.7    5372   228.5    5412   228.9    5472     232    5497   232.6
#Mann= 6 , 1 , 0
 4316.30     0.2       0  4316.3     0.1       0  4780.4    0.16       0
  4959.8   0.045       0  5048.3    0.16       0    5497     0.2       0
Bank Sta=4959.80,5048.30
Exp/Cntr=0.3,0.1

Type RM Length L Ch R = 1 ,356800.3,582.6,582.6,582.6
BEGIN DESCRIPTION:
Cross Section Little River 15.0
END DESCRIPTION:
#Sta/Elev= 30
  4320.6   248.9  4400.6   248.1  4450.6   248.9  4480.6   247.1  4530.6   245.8
  4590.6   241.9  4630.6   240.2  4760.6   227.8  4840.6   221.6  4941.9  215.01
  4960.5  213.08  4962.3  211.08  4970.7  208.66  4986.9  208.19  5003.2  202.95
  5012.3  204.71  5029.5  211.09  5031.5   212.3  5061.5   211.5  5121.5   211.6
  5191.5   213.3  5221.5   212.2  5271.5   212.2  5371.5   223.2  5511.5   234.5
  5561.5   235.4  5621.5   238.5  5641.5   240.7  5721.5   244.8  5771.9   246.1
#Mann= 6 , 1 , 0
 4320.60     0.2       0  4320.6     0.1       0  4941.9    0.16       0
  4960.5   0.045       0  5029.5    0.16       0  5771.9     0.2       0
Bank Sta=4960.50,5029.50
Exp/Cntr=0.3,0.1

Type RM Length L Ch R = 1 ,356217.7,316.7,316.7,316.7
BEGIN DESCRIPTION:
Cross Section Little River 14.7
END DESCRIPTION:
#Sta/Elev= 30
  4328.4     231  4388.4   227.2  4458.4   224.3  4528.4   222.4  4598.4   221.2
  4623.4  219.95  4658.4   218.1  4718.4   215.8  4758.4   213.5  4818.4   212.8
  4848.4   210.9  4858.4   210.7  4898.4   211.4  4960.5  211.34  4962.3  209.34
  4970.7  206.92  4986.9  206.45  4999.3  202.78  5003.2  201.21  5012.3  202.97
  5029.5  209.35  5039.5   211.1  5119.5     211  5159.5   213.9  5209.5   215.2
  5239.5   216.8  5289.5   220.5  5299.5   221.5  5349.5     232  5397.6   238.1
#Mann= 6 , 1 , 0
 4328.40     0.2       0  4328.4     0.1       0  4623.4    0.16       0
  4960.5   0.045       0  5029.5    0.16       0  5397.6     0.2       0
Bank Sta=4960.50,5029.50
Exp/Cntr=0.5,0.3

Type RM Length L Ch R = 1 ,355901.0,32,32,32
BEGIN DESCRIPTION:
Upstream Section of Bridge/Culvert/Weir
END DESCRIPTION:
#Sta/Elev= 30
  4223.9  231.54  4293.9  227.54  4463.9  221.84  4593.9  219.74  4696.2  214.39
  4753.9  213.44    4832  215.03  4885.8  213.32  4925.7  215.48  4959.8  212.71
  4960.5  212.65  4962.3  207.65  4970.7  205.23  4986.9  204.76  5003.2  199.52
  5012.3  201.28  5029.5  207.66  5034.8  211.97  5048.3  213.97  5112.1  213.34
    5209  215.46  5304.9   216.1  5306.8  211.34  5341.9  211.24  5396.8  212.84
  5546.8  214.34  5626.8  219.14  5666.8  222.94  5736.8  226.54  5779.3  231.44
#Mann= 5 , 1 , 0
 4223.90     0.2       0  4696.2    0.16       0  4959.8   0.045       0
  5048.3    0.16       0  5341.9     0.2       0
#XS Ineff= 2 , 0
       0  4943.1   239.4  5064.9       0   241.3
Bank Sta=4959.80,5048.30
Exp/Cntr=0.5,0.3

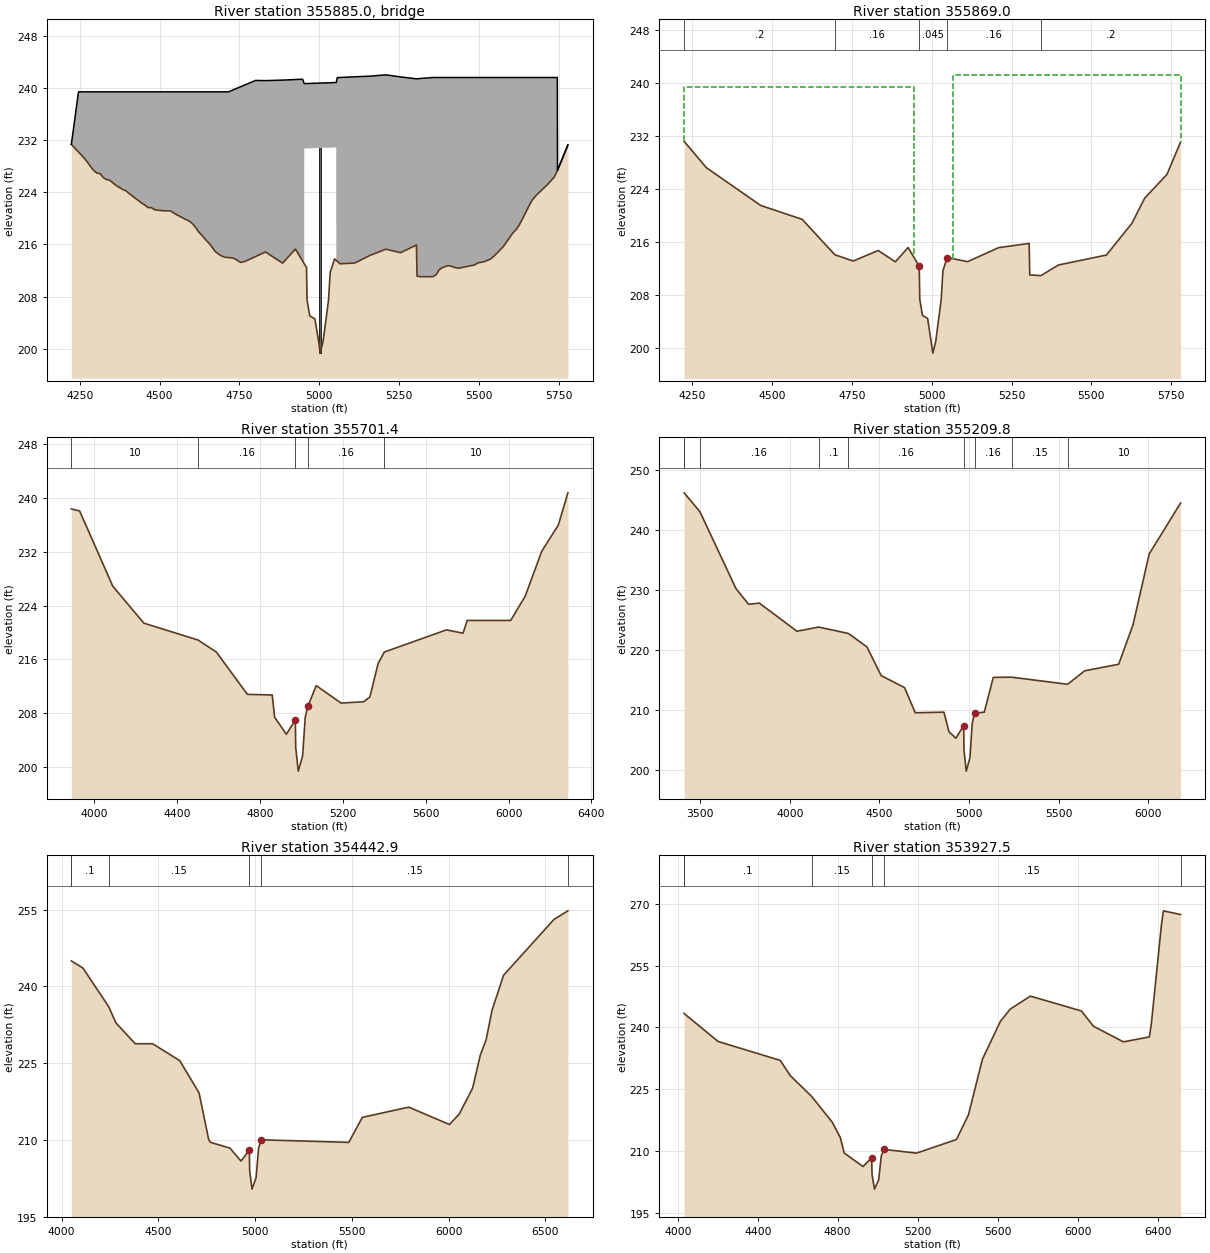
Type RM Length L Ch R = 3 ,355885.0,,,
BEGIN DESCRIPTION:
CAROLINA AND NORTHWESTERN RR
Structure ID: WK_LITR2
END DESCRIPTION:
Bridge Culvert--1,0,-1,-1, 0
Deck Dist Width WeirC Skew NumUp NumDn MinLoCord MaxHiCord MaxSubmerge Is_Ogee
10,12,2.6,, 60, 60,,,0.95,0,1,1,,
  4223.9  4246.2  4263.9  4293.9  4303.9  4313.9  4323.9  4343.9  4363.9  4393.9
  4463.9  4473.9  4493.9  4533.9  4593.9  4603.9  4623.9  4663.9  4673.9  4693.9
  4716.2  4733.9  4753.9    4767  4800.6    4832  4885.8  4925.7  4948.2 4953.41
  4953.5 5053.69  5053.8  5053.9  5056.8  5065.3  5112.1    5158    5209  5254.9
  5304.9  5306.8  5316.8  5356.8  5366.8  5376.8  5396.8  5406.8  5436.8  5486.8
  5496.8  5536.8  5576.8  5606.8  5626.8  5666.8  5736.8  5746.2  5746.8  5779.3
  231.35   239.4   239.4   239.4   239.4   239.4   239.4   239.4   239.4   239.4
   239.4   239.4   239.4   239.4   239.4   239.4   239.4   239.4   239.4   239.4
   239.4  239.77  240.18  240.45  241.15  241.12   241.2  241.29  241.34  240.66
  240.66  240.83  240.83  240.86  241.58   241.6  241.71   241.8  242.01  241.69
   241.4   241.4  241.45   241.6   241.6   241.6   241.6   241.6   241.6   241.6
   241.6   241.6   241.6   241.6   241.6   241.6   241.6   241.6  227.35  231.25
  231.35  230.18  229.25  227.35  226.95  226.85  226.25  225.85  225.05  224.25
  221.65  221.65  221.25  221.15  219.55  219.15  217.85  215.65  214.95  214.25
  213.99  213.85  213.25  213.38  214.13  214.84  213.13  215.29  213.46  213.04
  230.71  230.88  213.54  213.53  213.41  213.03  213.15  214.29  215.27  214.73
  215.91  211.15  211.05  211.05  211.35  212.15  212.65  212.75  212.35  212.85
  213.15  213.75  215.65  217.75  218.95  222.75  226.35  227.29  227.35  231.25
  4223.9  4246.2  4263.9  4293.9  4303.9  4313.9  4323.9  4343.9  4363.9  4393.9
  4463.9  4473.9  4493.9  4533.9  4593.9  4603.9  4623.9  4663.9  4673.9  4693.9
  4716.2  4733.9  4753.9    4767  4800.6    4832  4885.8  4925.7  4948.2 4953.41
  4953.5 5053.69  5053.8  5053.9  5056.8  5065.3  5112.1    5158    5209  5254.9
  5304.9  5306.8  5316.8  5356.8  5366.8  5376.8  5396.8  5406.8  5436.8  5486.8
  5496.8  5536.8  5576.8  5606.8  5626.8  5666.8  5736.8  5746.2  5746.8  5779.3
   231.3   239.4   239.4   239.4   239.4   239.4   239.4   239.4   239.4   239.4
   239.4   239.4   239.4   239.4   239.4   239.4   239.4   239.4   239.4   239.4
   239.4  239.77  240.18  240.45  241.15  241.12   241.2  241.29  241.34  240.66
  240.66  240.83  240.83  240.86  241.58   241.6  241.71   241.8  242.01  241.69
   241.4   241.4  241.45   241.6   241.6   241.6   241.6   241.6   241.6   241.6
   241.6   241.6   241.6   241.6   241.6   241.6   241.6   241.6   227.3   231.2
  231.25  230.08  229.15  227.25  226.85  226.75  226.15  225.75  224.95  224.15
  221.55  221.55  221.15  221.05  219.45  219.05  217.75  215.55  214.85  214.15
  213.89  213.75  213.15  213.28  214.03  214.74  213.03  215.19  213.36  212.94
  230.61  230.78  213.44  213.43  213.31  212.93  213.05  214.19  215.17  214.63
  215.81  211.05  210.95  210.95  211.25  212.05  212.55  212.65  212.25  212.75
  213.05  213.65  215.55  217.65  218.85  222.65  226.25  227.19  227.25  231.15
Pier Skew, UpSta & Num, DnSta & Num=,5003.2, 2 ,5003.2, 2 , 0 , 0 , 0 ,,
     4.5     4.5
  198.77  231.79
     4.5     4.5
  198.67  231.69
BR Coef= 1 , 1 , 0 ,1.25, 0 ,,,0.8,0,2,0,
Wspro=,,,, 1 ,,,, 0 ,,,, 0 ,,,,-1 ,-1 ,-1 , 0 , 0 , 0 , 0 , 0
BC Design=,, 0 ,, 0 ,,,,,,
BR U #Sta/Elev= 124
  4223.9  231.35  4246.2  230.18  4263.9  229.25  4273.9  228.65  4283.9  227.95
  4293.9  227.35  4303.9  226.95  4313.9  226.85  4323.9  226.25  4333.9  225.95
  4343.9  225.85  4353.9  225.45  4363.9  225.05  4373.9  224.75  4383.9  224.45
  4393.9  224.25  4403.9  223.85  4443.9  222.35  4453.9  222.05  4463.9  221.65
  4473.9  221.65  4483.9  221.35  4493.9  221.25  4513.9  221.15  4523.9  221.15
  4533.9  221.15  4543.9  220.85  4553.9  220.55  4593.9  219.55  4603.9  219.15
  4613.9  218.55  4623.9  217.85  4633.9  217.35  4643.9  216.75  4653.9  216.25
  4663.9  215.65  4673.9  214.95  4683.9  214.55  4693.9  214.25  4696.2   214.2
  4703.9  214.05  4706.2  214.04  4716.2  213.99  4723.9  213.95  4733.9  213.85
  4743.9  213.55  4753.9  213.25    4767  213.38  4800.6  214.13    4832  214.84
  4848.9   214.3  4885.8  213.13  4897.9  213.79  4925.7  215.29  4948.2  213.46
  4953.3  213.05 4953.41  213.04  4953.5  213.03  4953.6  213.02  4959.8  212.52
  4960.5  212.46  4962.3  207.46  4970.7  205.04  4986.9  204.57  4999.3   200.9
  5003.2  199.33  5012.3  201.09  5029.5  207.47  5034.8  211.78  5039.5   212.4
  5048.3  213.78  5053.6  213.55 5053.69  213.54  5053.8  213.54  5053.9  213.53
  5056.8  213.41  5065.3  213.03  5108.5  213.14  5112.1  213.15    5158  214.29
  5158.5   214.3  5207.6  215.24    5209  215.27  5254.9  214.73  5296.2   215.7
  5304.9  215.91  5306.2  212.65  5306.8  211.15  5316.8  211.05  5326.2  211.05
  5326.8  211.05  5336.2  211.05  5341.9  211.05  5356.8  211.05  5366.8  211.35
  5376.8  212.15  5386.8  212.45  5396.8  212.65  5406.8  212.75  5426.8  212.45
  5436.8  212.35  5456.8  212.55  5476.8  212.75  5486.8  212.85  5496.8  213.15
  5516.8  213.35  5536.8  213.75  5546.8  214.15  5576.8  215.65  5586.8  216.35
  5596.8  217.05  5606.8  217.75  5616.8  218.25  5626.8  218.95  5646.8  220.85
  5656.8  221.85  5666.8  222.75  5676.8  223.35  5686.8  223.85  5716.8  225.25
  5736.8  226.35  5746.2  227.29  5746.8  227.35  5779.3  231.25
BR U #Mann= 5
 4223.90     0.2  4696.2    0.16  4959.8   0.045  5048.3    0.16  5341.9     0.2
BR U Banks=4959.80,5048.30
BR D #Sta/Elev= 124
  4223.9  231.25  4246.2  230.08  4263.9  229.15  4273.9  228.55  4283.9  227.85
  4293.9  227.25  4303.9  226.85  4313.9  226.75  4323.9  226.15  4333.9  225.85
  4343.9  225.75  4353.9  225.35  4363.9  224.95  4373.9  224.65  4383.9  224.35
  4393.9  224.15  4403.9  223.75  4443.9  222.25  4453.9  221.95  4463.9  221.55
  4473.9  221.55  4483.9  221.25  4493.9  221.15  4513.9  221.05  4523.9  221.05
  4533.9  221.05  4543.9  220.75  4553.9  220.45  4593.9  219.45  4603.9  219.05
  4613.9  218.45  4623.9  217.75  4633.9  217.25  4643.9  216.65  4653.9  216.15
  4663.9  215.55  4673.9  214.85  4683.9  214.45  4693.9  214.15  4696.2   214.1
  4703.9  213.95  4706.2  213.94  4716.2  213.89  4723.9  213.85  4733.9  213.75
  4743.9  213.45  4753.9  213.15    4767  213.28  4800.6  214.03    4832  214.74
  4848.9   214.2  4885.8  213.03  4897.9  213.69  4925.7  215.19  4948.2  213.36
  4953.3  212.95 4953.41  212.94  4953.5  212.93  4953.6  212.92  4959.8  212.42
  4960.5  212.36  4962.3  207.36  4970.7  204.94  4986.9  204.47  4999.3   200.8
  5003.2  199.23  5012.3  200.99  5029.5  207.37  5034.8  211.68  5039.5   212.3
  5048.3  213.68  5053.6  213.45 5053.69  213.44  5053.8  213.44  5053.9  213.43
  5056.8  213.31  5065.3  212.93  5108.5  213.04  5112.1  213.05    5158  214.19
  5158.5   214.2  5207.6  215.14    5209  215.17  5254.9  214.63  5296.2   215.6
  5304.9  215.81  5306.2  212.55  5306.8  211.05  5316.8  210.95  5326.2  210.95
  5326.8  210.95  5336.2  210.95  5341.9  210.95  5356.8  210.95  5366.8  211.25
  5376.8  212.05  5386.8  212.35  5396.8  212.55  5406.8  212.65  5426.8  212.35
  5436.8  212.25  5456.8  212.45  5476.8  212.65  5486.8  212.75  5496.8  213.05
  5516.8  213.25  5536.8  213.65  5546.8  214.05  5576.8  215.55  5586.8  216.25
  5596.8  216.95  5606.8  217.65  5616.8  218.15  5626.8  218.85  5646.8  220.75
  5656.8  221.75  5666.8  222.65  5676.8  223.25  5686.8  223.75  5716.8  225.15
  5736.8  226.25  5746.2  227.19  5746.8  227.25  5779.3  231.15
BR D #Mann= 5
 4223.90     0.2  4696.2    0.16  4959.8   0.045  5048.3    0.16  5341.9     0.2
BR D Banks=4959.80,5048.30

Type RM Length L Ch R = 1 ,355869.0,167.6,167.6,167.6
BEGIN DESCRIPTION:
Downstream Section of Bridge/Culvert/Weir
END DESCRIPTION:
#Sta/Elev= 30
  4223.9  231.26  4293.9  227.26  4463.9  221.56  4593.9  219.46  4696.2  214.11
  4753.9  213.16    4832  214.75  4885.8  213.04  4925.7   215.2  4959.8  212.43
  4960.5  212.37  4962.3  207.37  4970.7  204.95  4986.9  204.48  5003.2  199.24
  5012.3     201  5029.5  207.38  5034.8  211.69  5048.3  213.69  5112.1  213.06
    5209  215.18  5304.9  215.82  5306.8  211.06  5341.9  210.96  5396.8  212.56
  5546.8  214.06  5626.8  218.86  5666.8  222.66  5736.8  226.26  5779.3  231.16
#Mann= 5 , 1 , 0
 4223.90     0.2       0  4696.2    0.16       0  4959.8   0.045       0
  5048.3    0.16       0  5341.9     0.2       0
#XS Ineff= 2 , 0
       0  4943.1   239.4  5064.9       0   241.3
Bank Sta=4959.80,5048.30
Exp/Cntr=0.5,0.3

Type RM Length L Ch R = 1 ,355701.4,491.6,491.6,491.6
BEGIN DESCRIPTION:
Cross Section Little River 14.5
END DESCRIPTION:
#Sta/Elev= 30
  3888.5   238.4  3928.5   238.1  4088.5   226.9  4238.5   221.4    4500  218.89
  4588.5   217.1  4738.5   210.8  4858.5   210.7    4870   207.4  4926.8  204.86
  4970.1  206.98  4971.9   202.9  4984.2  199.37  5005.1  201.62    5018   207.4
  5030.5  209.02  5071.1   212.1  5191.1   209.5    5300   209.7    5330   210.4
    5370   215.4    5400   217.1    5700   220.4    5780   219.9    5800   221.8
    6010   221.8    6080   225.4    6160   232.1    6240     236  6286.3   240.8
#Mann= 5 , 1 , 0
 3888.50      10       0    4500    0.16       0  4970.1   0.045       0
  5030.5    0.16       0    5400      10       0
Bank Sta=4970.10,5030.50
Exp/Cntr=0.3,0.1

Type RM Length L Ch R = 1 ,355209.8,766.9,766.9,766.9
BEGIN DESCRIPTION:
Cross Section Little River 14.0
END DESCRIPTION:
#Sta/Elev= 30
  3409.9   246.2  3497.7  243.09  3699.9   230.2  3769.9   227.6  3829.9   227.8
  4039.9   223.1    4161   223.8    4327  222.73  4429.9   220.5  4509.9   215.7
  4639.9   213.7  4699.9   209.5  4859.9   209.6    4888  206.33  4926.8  205.25
  4970.1  207.37  4971.9  203.29  4984.2  199.76  5005.1  202.01    5018  207.79
  5030.5  209.41  5085.2   209.6  5135.2   215.4  5237.1  215.44    5550  214.25
  5645.2   216.5  5835.2   217.6  5915.2   224.2  6005.2     236  6180.4   244.5
#Mann= 9 , 1 , 0
 3409.90     0.2       0  3409.9     0.1       0  3497.7    0.16       0
    4161     0.1       0    4327    0.16       0  4970.1   0.045       0
  5030.5    0.16       0  5237.1    0.15       0    5550      10       0
Bank Sta=4970.10,5030.50
Exp/Cntr=0.3,0.1

Type RM Length L Ch R = 1 ,354442.9,515.4,515.4,515.4
BEGIN DESCRIPTION:
Cross Section Little River 13.0
END DESCRIPTION:
#Sta/Elev= 30
  4050.3     245  4110.3   243.6  4243.4  236.04  4280.3   232.9  4380.3   228.8
  4470.3   228.8  4610.3   225.5  4710.3   219.2  4760.3     210  4770.3   209.5
    4870  208.39  4926.8  205.85  4970.1  207.97  4971.9  203.89  4984.2  200.36
  5005.1  202.61    5018  208.39  5030.5  210.01  5484.1   209.5  5554.1   214.4
  5794.1   216.4  6004.1     213  6054.1     215  6124.1   220.1  6164.1   226.6
  6194.1   229.6  6224.1   235.3  6284.1   242.2  6544.1   253.1  6616.5   254.8
#Mann= 6 , 1 , 0
 4050.30     0.2       0  4050.3     0.1       0  4243.4    0.15       0
  4970.1   0.045       0  5030.5    0.15       0  6616.5     0.2       0
Bank Sta=4970.10,5030.50
Exp/Cntr=0.3,0.1

Type RM Length L Ch R = 1 ,353927.5,484.6,484.6,484.6
BEGIN DESCRIPTION:
Cross Section Little River 12.0
END DESCRIPTION:
#Sta/Elev= 30
  4031.7   243.4  4201.7   236.6  4512.9     232  4562.9   228.3  4669.6  223.27
  4772.9     217  4812.9   213.3  4832.9   209.5  4926.8  206.25  4970.1  208.37
  4971.9  204.29  4984.2  200.76  5005.1  203.01    5018  208.79  5030.5  210.41
  5194.1   209.5  5394.1   212.8  5454.1   218.8  5524.1   232.3  5614.1   241.5
  5664.1   244.5  5764.1   247.6  6019.1     244  6079.1   240.3  6229.1   236.5
  6359.1   237.7  6369.1     241  6419.1   264.8  6429.1   268.3  6515.1   267.4
#Mann= 6 , 1 , 0
 4031.70     0.2       0  4031.7     0.1       0  4669.6    0.15       0
  4970.1   0.045       0  5030.5    0.15       0  6515.1     0.2       0
Bank Sta=4970.10,5030.50
Exp/Cntr=0.3,0.1

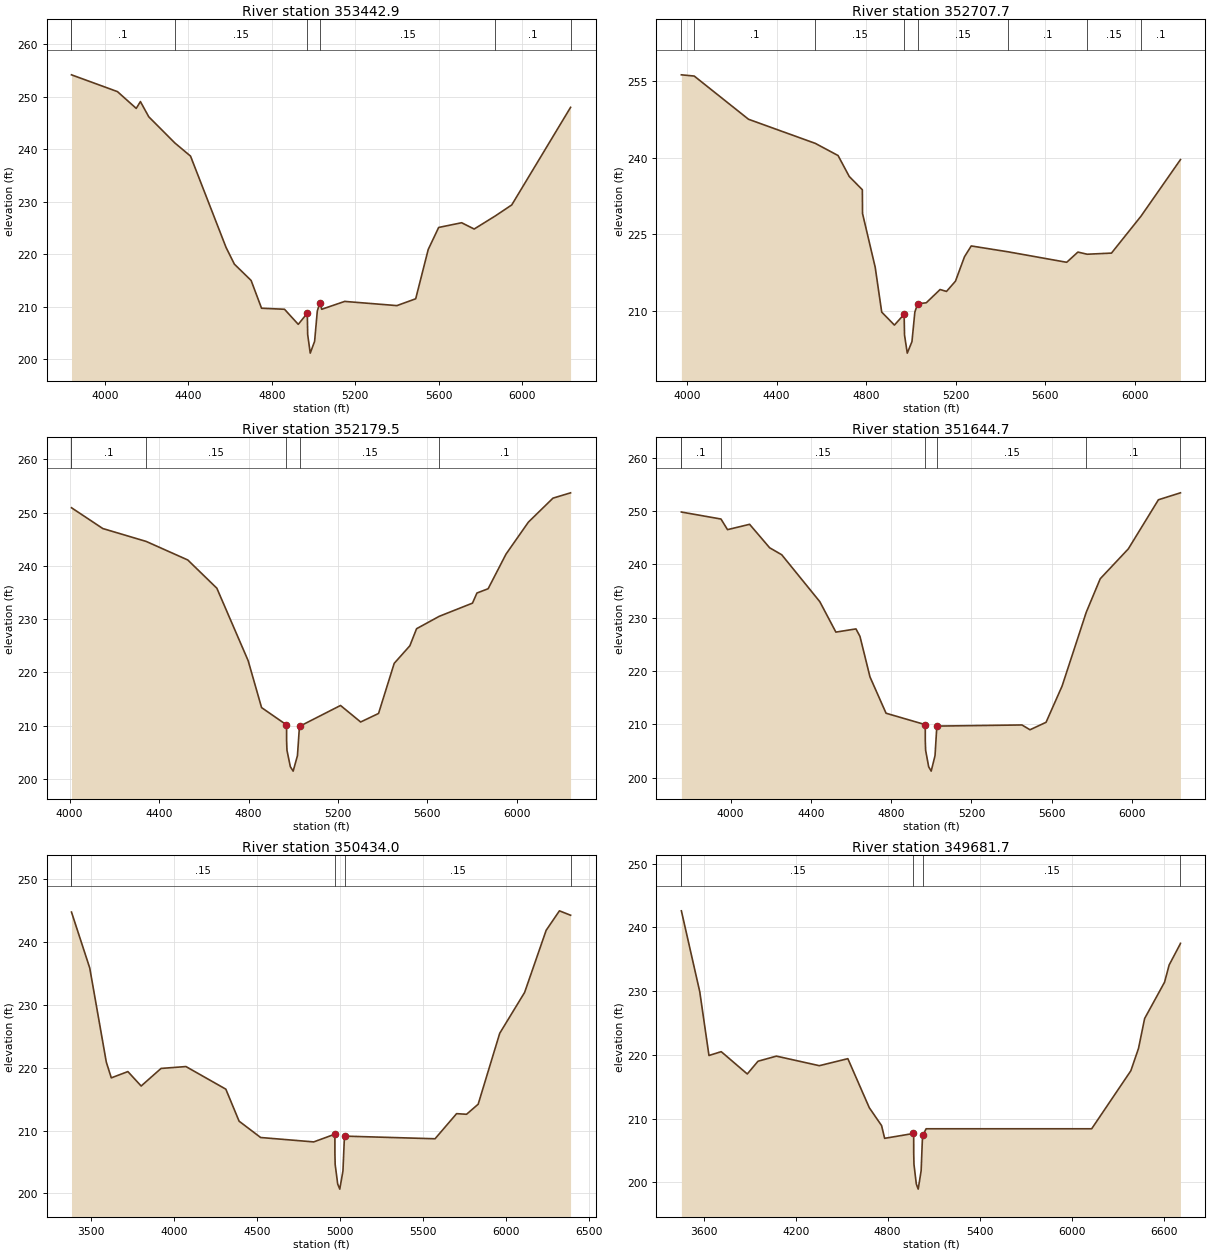
Type RM Length L Ch R = 1 ,353442.9,735.2,735.2,735.2
BEGIN DESCRIPTION:
Cross Section Little River 11.0
END DESCRIPTION:
#Sta/Elev= 30
    3841   254.2    4061     251    4151   247.8    4171   249.1    4211   246.2
  4335.6  241.22    4411   238.7    4581   221.3    4621   218.1    4701     215
    4751   209.7    4861   209.5  4926.8  206.63  4970.1  208.75  4971.9  204.67
  4984.2  201.14  5005.1  203.39    5018  209.17  5030.5  210.79  5039.1   209.5
  5149.1     211  5399.1   210.2  5489.1   211.5  5549.1   220.9  5599.1   225.1
  5709.1     226  5769.1   224.8  5870.4   227.3  5949.1   229.4  6230.7     248
#Mann= 7 , 1 , 0
 3841.00     0.2       0    3841     0.1       0  4335.6    0.15       0
  4970.1   0.045       0  5030.5    0.15       0  5870.4     0.1       0
  6230.7     0.2       0
Bank Sta=4970.10,5030.50
Exp/Cntr=0.3,0.1

Type RM Length L Ch R = 1 ,352707.7,528.2,528.2,528.2
BEGIN DESCRIPTION:
Cross Section Little River 10.0 (CCX 169)
END DESCRIPTION:
#Sta/Elev= 30
    3975   256.2  4032.4  255.96    4275   247.5  4573.4  242.78    4675   240.4
    4725   236.3  4783.5   233.7  4784.3  229.05  4840.9  218.53    4870  209.75
  4926.8  207.21  4970.1  209.33  4971.9  205.25  4984.2  201.72  5005.1  203.97
    5018  209.75  5030.5  211.37  5069.1  211.58  5130.8  214.17  5159.4   213.8
  5199.4   215.8  5239.9   220.6  5269.9   222.7    5435  221.55  5696.4   219.5
  5746.4   221.5    5788  221.08  5896.4   221.3  6027.8   228.5  6204.6   239.6
#Mann= 8 , 1 , 0
 3975.00     0.2       0  4032.4     0.1       0  4573.4    0.15       0
  4970.1   0.045       0  5030.5    0.15       0    5435     0.1       0
    5788    0.15       0  6027.8     0.1       0
Bank Sta=4970.10,5030.50
Exp/Cntr=0.3,0.1

Type RM Length L Ch R = 1 ,352179.5,534.8,534.8,534.8
BEGIN DESCRIPTION:
Cross Section Little River 9.0
END DESCRIPTION:
#Sta/Elev= 30
  4008.4   250.9  4148.4     247  4342.4  244.58  4528.4   241.1  4658.4   235.8
  4798.4   222.2  4858.4   213.4  4968.1  210.21  4970.2  209.81  4970.3  207.15
  4971.9  205.39  4987.1   202.3  4999.6  201.48  5018.8  204.38  5026.6  209.16
    5030  209.92  5211.4   213.8  5301.4   210.7  5381.4   212.3  5451.4   221.7
  5521.4     225  5551.4   228.2  5652.9  230.53  5801.4     233  5821.4   234.9
  5871.4   235.7  5951.4   242.2  6051.4   248.2  6161.4   252.7  6240.1   253.7
#Mann= 6 , 1 , 0
 4008.40     0.2       0  4008.4     0.1       0  4342.4    0.15       0
  4968.1   0.045       0    5030    0.15       0  5652.9     0.1       0
Bank Sta=4968.10,5030.00
Exp/Cntr=0.3,0.1

Type RM Length L Ch R = 1 ,351644.7,1210.7,1210.7,1210.7
BEGIN DESCRIPTION:
Cross Section Little River 8.0
END DESCRIPTION:
#Sta/Elev= 30
  3754.7   249.8    3952  248.49  3984.7   246.5  4094.7   247.5  4194.7   243.1
  4254.7   241.8  4444.7     233  4524.7   227.3  4624.7   227.9  4644.7   226.5
  4694.7   218.9  4774.7   212.1  4968.1  209.98  4970.2  209.58  4970.3  206.92
  4971.9  205.16  4987.1  202.07  4999.6  201.25  5018.8  204.15  5026.6  208.93
    5030  209.69  5452.1   209.9  5492.1     209  5572.1   210.4  5652.1   217.2
  5772.4  231.02  5842.1   237.3  5982.1   242.9  6132.1   252.1  6241.9   253.4
#Mann= 7 , 1 , 0
 3754.70     0.2       0  3754.7     0.1       0    3952    0.15       0
  4968.1   0.045       0    5030    0.15       0  5772.4     0.1       0
  6241.9     0.2       0
Bank Sta=4968.10,5030.00
Exp/Cntr=0.3,0.1

Type RM Length L Ch R = 1 ,350434.0,752.3,752.3,752.3
BEGIN DESCRIPTION:
Cross Section Little River 7.0
END DESCRIPTION:
#Sta/Elev= 30
    3382   244.8    3492   235.9    3592   220.9    3622   218.4    3722   219.4
    3802   217.1    3922   219.9    4072   220.2  4312.6   216.6  4392.6   211.5
  4522.6   208.9  4842.6   208.2  4968.1  209.41  4970.2  209.01  4970.3  206.35
  4971.9  204.59  4987.1   201.5  4999.6  200.68  5018.8  203.58  5026.6  208.36
    5030  209.12  5574.1   208.7  5704.1   212.7  5764.1   212.6  5834.1   214.2
  5964.1   225.5  6114.1     232  6244.1   241.9  6324.1     245  6391.3   244.3
#Mann= 5 , 1 , 0
 3382.00     0.2       0    3382    0.15       0  4968.1   0.045       0
    5030    0.15       0  6391.3     0.2       0
Bank Sta=4968.10,5030.00
Exp/Cntr=0.3,0.1

Type RM Length L Ch R = 1 ,349681.7,777.4,777.4,777.4
BEGIN DESCRIPTION:
Cross Section Little River 6.0
END DESCRIPTION:
#Sta/Elev= 30
  3454.5   242.6  3574.5   229.9  3634.5   219.9  3714.5   220.5  3884.5     217
  3954.5     219  4074.5   219.8  4354.5   218.3  4540.6   219.4  4680.6   211.7
  4760.6   208.9  4780.6   206.9  4968.1  207.66  4970.2  207.26  4970.3   204.6
  4971.9  202.84  4987.1  199.75  4999.6  198.93  5018.8  201.83  5026.6  206.61
    5030  207.37  5051.3   208.4  6131.3   208.4  6386.8   217.5  6436.8     221
  6476.8   225.7  6606.8   231.4  6636.8   234.1  6708.7  237.38  6710.6   237.5
#Mann= 5 , 1 , 0
 3454.50     0.2       0  3454.5    0.15       0  4968.1   0.045       0
    5030    0.15       0  6708.7     0.2       0
Bank Sta=4968.10,5030.00
Exp/Cntr=0.3,0.1