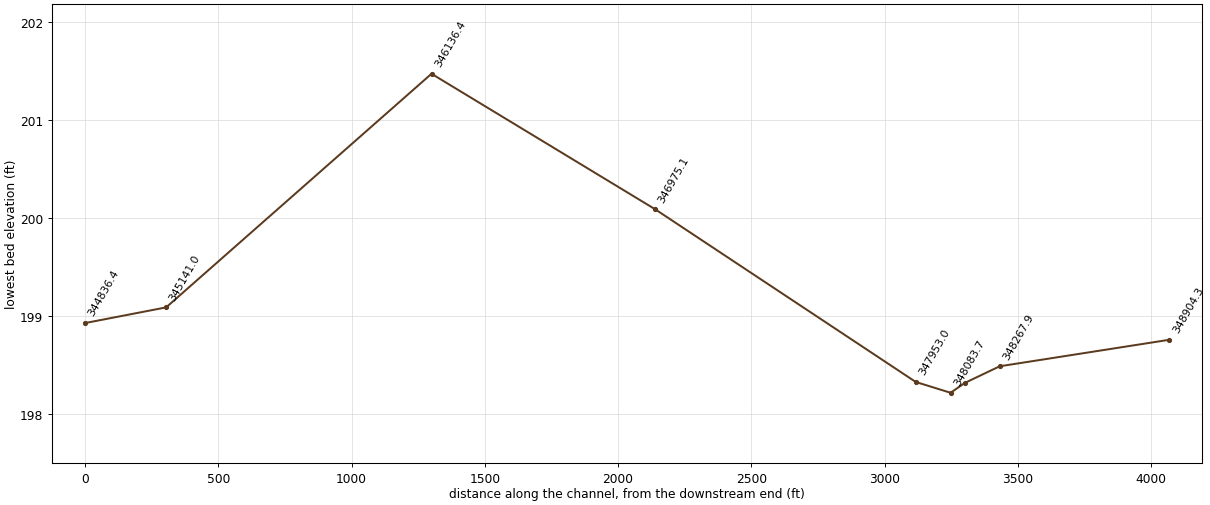
HEC-RAS study Little_River_FINAL.prj: Little River Detail Study

--- Little_River_FINAL.g01 (geometry) --- (continued)

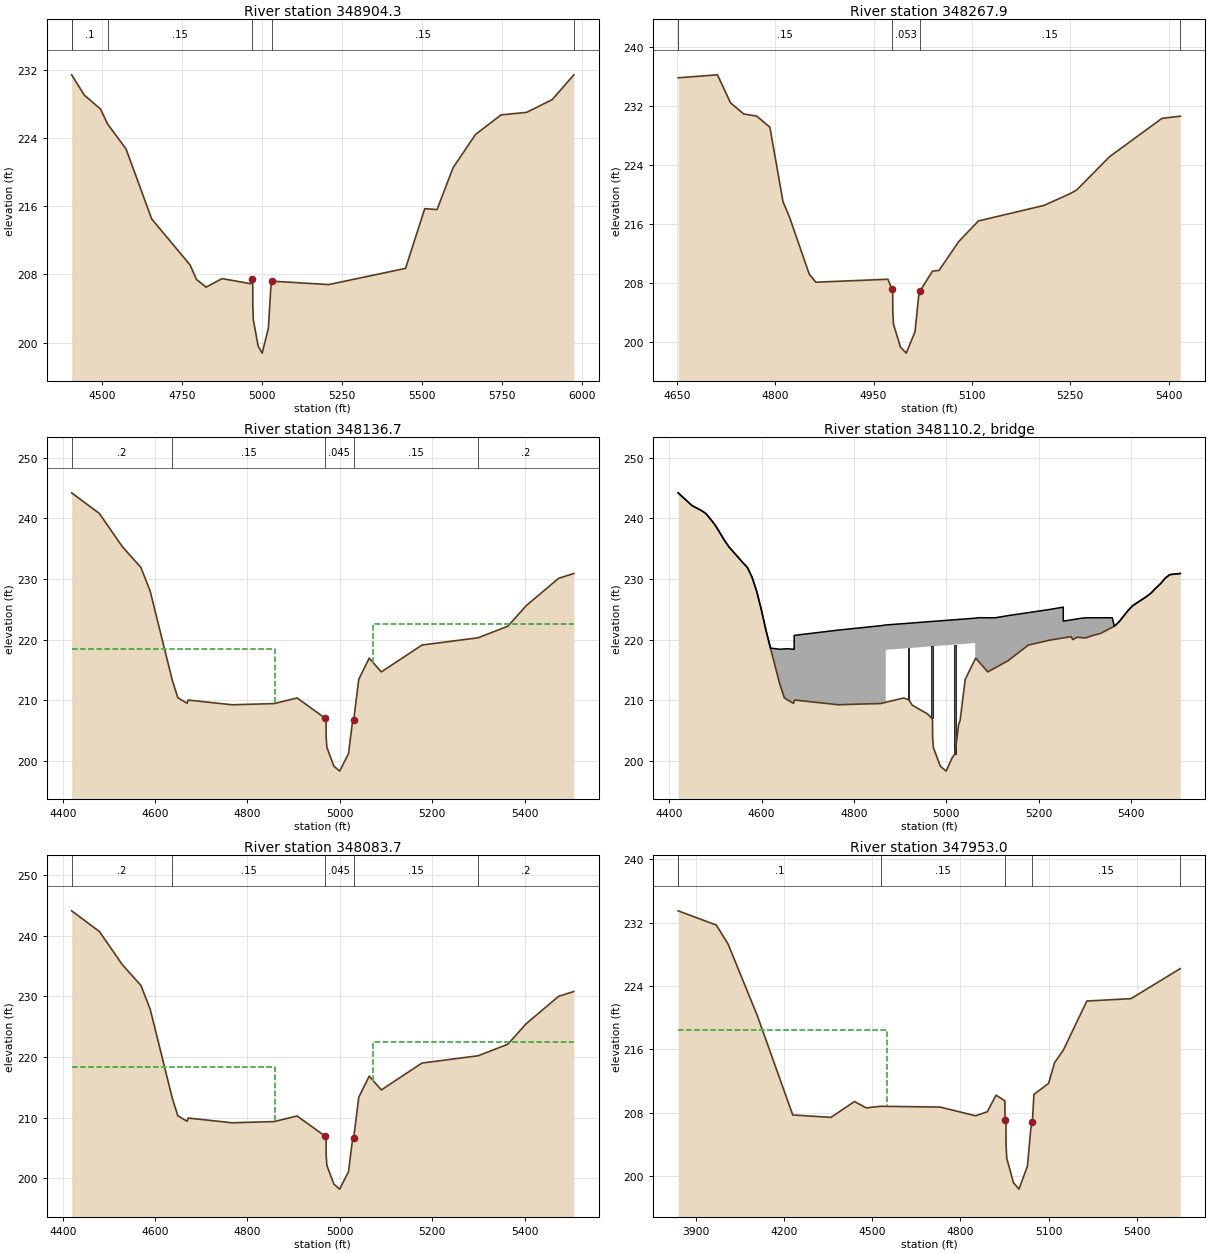
Type RM Length L Ch R = 1 ,348904.3,636.4,636.4,636.4
BEGIN DESCRIPTION:
Cross Section Little River 5.0
END DESCRIPTION:
#Sta/Elev= 30
  4404.4   231.4  4444.4     229  4494.4   227.4  4516.8  225.63  4574.4   222.7
  4654.4   214.5  4774.4   209.1  4794.4   207.4  4824.4   206.5  4874.4   207.5
  4964.4   206.9  4968.1  207.49  4970.2  207.09  4970.3  204.43  4971.9  202.67
  4987.1  199.58  4999.6  198.76  5018.8  201.66  5026.6  206.44    5030   207.2
  5207.4   206.8  5447.4   208.7  5507.4   215.7  5545.8   215.6  5595.8   220.5
  5665.8   224.4  5745.8   226.7  5825.8     227  5905.8   228.5  5973.1   231.4
#Mann= 6 , 1 , 0
 4404.40     0.2       0  4404.4     0.1       0  4516.8    0.15       0
  4968.1   0.053       0    5030    0.15       0  5973.1     0.2       0
Bank Sta=4968.10,5030.00
Exp/Cntr=0.3,0.1

Type RM Length L Ch R = 1 ,348267.9,131.2,131.2,131.2
BEGIN DESCRIPTION:
Cross Section Little River 4.0
END DESCRIPTION:
#Sta/Elev= 30
  4651.8   235.8  4711.8   236.2  4731.8   232.4  4751.8   230.9  4771.8   230.6
  4791.8   229.1  4811.8     219  4821.8   216.9  4851.8   209.2  4861.8   208.1
  4971.8   208.5 4977.67  207.22 4979.14  206.82 4979.21  204.16 4980.33   202.4
 4990.97  199.31 4999.72  198.49 5013.16  201.39 5018.62  206.17    5021  206.93
  5039.8   209.6  5049.8   209.7  5079.8   213.6  5109.8   216.4  5209.8   218.5
  5249.8   220.1  5259.8   220.6  5309.8   225.1  5389.8   230.3  5417.8   230.6
#Mann= 5 , 1 , 0
 4651.80     0.2       0  4651.8    0.15       0 4977.67   0.053       0
    5021    0.15       0  5417.8     0.2       0
Bank Sta=4977.67,5021.00
Exp/Cntr=0.5,0.3

Type RM Length L Ch R = 1 ,348136.7,53,53,53
BEGIN DESCRIPTION:
Upstream Section of Bridge/Culvert/Weir
END DESCRIPTION:
#Sta/Elev= 30
  4419.2  244.21  4479.2  240.81  4529.2  235.31  4569.2  231.91  4589.2  228.01
  4637.3  213.27  4649.2  210.41  4669.2  209.51  4671.6  210.04  4766.7  209.26
  4857.7  209.46  4907.5  210.38  4968.1  207.05  4970.2  206.65  4970.3  203.99
  4971.9  202.23  4987.1  199.14  4999.6  198.32  5018.8  201.22  5026.6     206
    5030  206.76    5041  213.47  5063.6  216.95  5089.8  214.68  5177.9  219.11
  5299.4  220.31  5363.7  222.21  5403.7  225.61  5473.7  230.11  5506.7  230.91
#Mann= 5 , 1 , 0
 4419.20     0.2       0  4637.3    0.15       0  4968.1   0.045       0
    5030    0.15       0  5299.4     0.2       0
#XS Ineff= 2 , 0
       0  4858.6   218.4  5072.4       0   222.5
Bank Sta=4968.10,5030.00
Exp/Cntr=0.5,0.3

Type RM Length L Ch R = 3 ,348110.2,,,
BEGIN DESCRIPTION:
MORPHUS BRIDGE RD
Structure ID: WK_LITR1
END DESCRIPTION:
Bridge Culvert--1,0,-1,-1, 0
Deck Dist Width WeirC Skew NumUp NumDn MinLoCord MaxHiCord MaxSubmerge Is_Ogee
10,33,2.6,, 55, 56,,,0.95,0,1,1,,
  4419.2  4449.2  4469.2  4479.2  4499.2  4519.2  4529.2  4559.2  4569.2  4579.2
  4589.2  4599.2  4609.2  4619.2  4639.2  4649.2  4657.3  4669.2 4670.49  4670.6
  4671.6  4766.7  4857.7 4868.71  4868.8 5062.49  5062.6  5063.6  5068.7  5089.8
  5106.1  5133.6  5177.9  5224.7  5253.2 5253.31  5270.5  5273.7  5283.7  5293.7
  5303.7  5313.7  5333.7  5359.4  5363.7  5373.7  5393.7  5403.7  5433.7  5443.7
  5453.7  5463.7  5473.7  5483.7  5506.7
   244.2   242.1   241.3   240.8   238.9   236.4   235.3   232.7   231.9   230.3
     228     225   221.6   218.6  218.41  218.46   218.5  218.39  218.39  220.69
   220.7  221.57  222.29  222.41  222.41  223.53  223.53  223.54  223.61   223.6
   223.6  223.95  224.45  224.98  225.35  223.05  223.25  223.29  223.41  223.53
   223.6   223.6   223.6   223.6   222.2   222.9   224.8   225.6   227.1   227.7
   228.5   229.2   230.1   230.7   230.9
   244.2   242.1   241.3   240.8   238.9   236.4   235.3   232.7   231.9   230.3
     228     225   221.6   218.6   212.7   210.4     210   209.5  209.78  209.81
  210.03  209.25  209.45  209.65  218.31  219.43  216.79  216.94   216.5  214.67
  215.35  216.51   219.1  219.92  220.27  220.27  220.48     220   220.4   220.3
   220.3   220.6     221  222.03   222.2   222.9   224.8   225.6   227.1   227.7
   228.5   229.2   230.1   230.7   230.9
  4419.2  4449.2  4469.2  4479.2  4489.2  4499.2  4519.2  4529.2  4559.2  4569.2
  4579.2  4589.2  4599.2  4609.2  4619.2  4639.2  4649.2  4657.3  4669.2 4670.49
  4670.6  4671.6  4766.7  4857.7 4868.71  4868.8 5062.49  5062.6  5063.6  5068.7
  5089.8  5106.1  5133.6  5177.9  5224.7  5253.2 5253.31  5270.5  5273.7  5283.7
  5293.7  5303.7  5313.7  5333.7  5359.4  5363.7  5373.7  5393.7  5403.7  5433.7
  5443.7  5453.7  5463.7  5473.7  5483.7  5506.7
   244.2   242.1   241.3   240.8   239.9   238.9   236.4   235.3   232.7   231.9
   230.3     228     225   221.6   218.6  218.41  218.46   218.5  218.39  218.39
  220.69   220.7  221.57  222.29  222.41  222.41  223.53  223.53  223.54  223.61
   223.6   223.6  223.95  224.45  224.98  225.35  223.05  223.25  223.29  223.41
  223.53   223.6   223.6   223.6   223.6   222.2   222.9   224.8   225.6   227.1
   227.7   228.5   229.2   230.1   230.7   230.9
   244.1     242   241.2   240.7   239.8   238.8   236.3   235.2   232.6   231.8
   230.2   227.9   224.9   221.5   218.5   212.6   210.3   209.9   209.4  209.68
  209.71  209.93  209.15  209.35  209.55  218.21  219.33  216.69  216.84   216.4
  214.57  215.25  216.41     219  219.82  220.17  220.17  220.38   219.9   220.3
   220.2   220.2   220.5   220.9  221.93   222.1   222.8   224.7   225.5     227
   227.6   228.4   229.1     230   230.6   230.8
Pier Skew, UpSta & Num, DnSta & Num=,4918.5, 2 ,4918.5, 2 , 0 , 0 , 0 ,,
       3       3
  208.91  219.61
       3       3
  208.81  219.51
Pier Skew, UpSta & Num, DnSta & Num=,4968.7, 2 ,4968.7, 2 , 0 , 0 , 0 ,,
       3       3
  205.64   219.9
       3       3
  205.54   219.8
Pier Skew, UpSta & Num, DnSta & Num=,5018.8, 2 ,5018.8, 2 , 0 , 0 , 0 ,,
       3       3
  200.03  220.19
       3       3
  199.93  220.09
BR Coef= 1 , 1 , 0 ,1.25, 0 ,,,0.8,0,2,0,
Wspro=,,,, 1 ,,,, 0 ,,,, 0 ,,,,-1 ,-1 ,-1 , 0 , 0 , 0 , 0 , 0
BC Design=,, 0 ,, 0 ,,,,,,
BR U #Sta/Elev= 100
  4419.2   244.2  4449.2   242.1  4459.2   241.7  4469.2   241.3  4479.2   240.8
  4489.2   239.9  4499.2   238.9  4509.2   237.7  4519.2   236.4  4529.2   235.3
  4559.2   232.7  4569.2   231.9  4579.2   230.3  4589.2     228  4599.2     225
  4609.2   221.6  4619.2   218.6  4637.3  213.26  4639.2   212.7  4649.2   210.4
  4657.3     210  4659.2   209.9  4667.3  209.58  4669.2   209.5 4670.49  209.78
  4670.6  209.81 4670.71  209.83    4671   209.9  4671.6  210.03  4719.2  209.64
  4719.3  209.64  4766.7  209.25    4767  209.25  4813.1  209.37  4813.2  209.37
  4857.7  209.45  4862.6  209.54  4868.6  209.65 4868.71  209.65  4868.8  209.66
  4868.9  209.66  4907.5  210.37  4918.5  210.09  4926.1  209.19  4959.2  207.75
  4968.1  207.04  4968.7  207.03  4970.2  206.64  4970.3  203.98  4971.9  202.22
  4987.1  199.13  4999.6  198.31    5012  200.41  5018.8  201.21  5022.7  203.55
  5026.6  205.99  5029.8  206.63    5030  206.75    5041  213.46  5062.4  216.76
 5062.49  216.77  5062.6  216.79  5062.7   216.8  5063.6  216.94  5068.7   216.5
  5089.8  214.67  5106.1  215.35  5133.6  216.51  5154.4  217.73  5177.9   219.1
  5204.2  219.56  5224.7  219.92 5253.09  220.27  5253.2  220.27 5253.31  220.27
  5255.9   220.3  5270.5  220.48  5273.7     220  5283.7   220.4  5293.7   220.3
  5299.4   220.3  5303.7   220.3  5313.7   220.6  5323.7   220.8  5333.7     221
  5359.4  222.03  5363.7   222.2  5373.7   222.9  5393.7   224.8  5403.7   225.6
  5413.7   226.1  5423.7   226.6  5433.7   227.1  5443.7   227.7  5453.7   228.5
  5463.7   229.2  5473.7   230.1  5483.7   230.7  5493.7   230.8  5506.7   230.9
BR U #Mann= 5
 4419.20     0.2  4637.3    0.15  4968.1   0.045    5030    0.15  5299.4     0.2
BR U Banks=4968.10,5030.00
BR D #Sta/Elev= 100
  4419.2   244.1  4449.2     242  4459.2   241.6  4469.2   241.2  4479.2   240.7
  4489.2   239.8  4499.2   238.8  4509.2   237.6  4519.2   236.3  4529.2   235.2
  4559.2   232.6  4569.2   231.8  4579.2   230.2  4589.2   227.9  4599.2   224.9
  4609.2   221.5  4619.2   218.5  4637.3  213.16  4639.2   212.6  4649.2   210.3
  4657.3   209.9  4659.2   209.8  4667.3  209.48  4669.2   209.4 4670.49  209.68
  4670.6  209.71 4670.71  209.73    4671   209.8  4671.6  209.93  4719.2  209.54
  4719.3  209.54  4766.7  209.15    4767  209.15  4813.1  209.27  4813.2  209.27
  4857.7  209.35  4862.6  209.44  4868.6  209.55 4868.71  209.55  4868.8  209.56
  4868.9  209.56  4907.5  210.27  4918.5  209.99  4926.1  209.09  4959.2  207.65
  4968.1  206.94  4968.7  206.93  4970.2  206.54  4970.3  203.88  4971.9  202.12
  4987.1  199.03  4999.6  198.21    5012  200.31  5018.8  201.11  5022.7  203.45
  5026.6  205.89  5029.8  206.53    5030  206.65    5041  213.36  5062.4  216.66
 5062.49  216.67  5062.6  216.69  5062.7   216.7  5063.6  216.84  5068.7   216.4
  5089.8  214.57  5106.1  215.25  5133.6  216.41  5154.4  217.63  5177.9     219
  5204.2  219.46  5224.7  219.82 5253.09  220.17  5253.2  220.17 5253.31  220.17
  5255.9   220.2  5270.5  220.38  5273.7   219.9  5283.7   220.3  5293.7   220.2
  5299.4   220.2  5303.7   220.2  5313.7   220.5  5323.7   220.7  5333.7   220.9
  5359.4  221.93  5363.7   222.1  5373.7   222.8  5393.7   224.7  5403.7   225.5
  5413.7     226  5423.7   226.5  5433.7     227  5443.7   227.6  5453.7   228.4
  5463.7   229.1  5473.7     230  5483.7   230.6  5493.7   230.7  5506.7   230.8
BR D #Mann= 5
 4419.20     0.2  4637.3    0.15  4968.1   0.045    5030    0.15  5299.4     0.2
BR D Banks=4968.10,5030.00

Type RM Length L Ch R = 1 ,348083.7,130.7,130.7,130.7
BEGIN DESCRIPTION:
Downstream Section of Bridge/Culvert/Weir
END DESCRIPTION:
#Sta/Elev= 30
  4419.2  244.11  4479.2  240.71  4529.2  235.21  4569.2  231.81  4589.2  227.91
  4637.3  213.17  4649.2  210.31  4669.2  209.41  4671.6  209.94  4766.7  209.16
  4857.7  209.36  4907.5  210.28  4968.1  206.95  4970.2  206.55  4970.3  203.89
  4971.9  202.13  4987.1  199.04  4999.6  198.22  5018.8  201.12  5026.6   205.9
    5030  206.66    5041  213.37  5063.6  216.85  5089.8  214.58  5177.9  219.01
  5299.4  220.21  5363.7  222.11  5403.7  225.51  5473.7  230.01  5506.7  230.81
#Mann= 5 , 1 , 0
 4419.20     0.2       0  4637.3    0.15       0  4968.1   0.045       0
    5030    0.15       0  5299.4     0.2       0
#XS Ineff= 2 , 0
       0  4858.6   218.4  5072.4       0   222.5
Bank Sta=4968.10,5030.00
Exp/Cntr=0.5,0.3

Type RM Length L Ch R = 1 ,347953.0,977.9,977.9,977.9
BEGIN DESCRIPTION:
Cross Section Little River 3.5
END DESCRIPTION:
#Sta/Elev= 30
  3839.9   233.5  3969.9   231.7  4009.9   229.3  4109.9   220.2  4229.9   207.7
  4359.9   207.4  4439.9   209.4  4479.9   208.6  4529.8   208.8  4731.5   208.7
  4851.5   207.6  4891.5   208.1  4921.5   210.2  4951.5   209.5 4952.15  207.06
  4955.3  206.66 4955.45     204 4957.85  202.24 4980.65  199.15  4999.4  198.33
  5028.2  201.23  5039.9  206.01    5045  206.77  5050.4   210.3  5100.4   211.7
  5120.4   214.3  5150.4   215.9  5230.4   222.1  5380.4   222.4  5548.3   226.2
#Mann= 6 , 1 , 0
 3839.90     0.2       0  3839.9     0.1       0  4529.8    0.15       0
 4952.15    0.05       0    5045    0.15       0  5548.3     0.2       0
#XS Ineff= 2 , 0
       0    4550   218.4               0
Bank Sta=4952.15,5045.00
Exp/Cntr=0.3,0.1

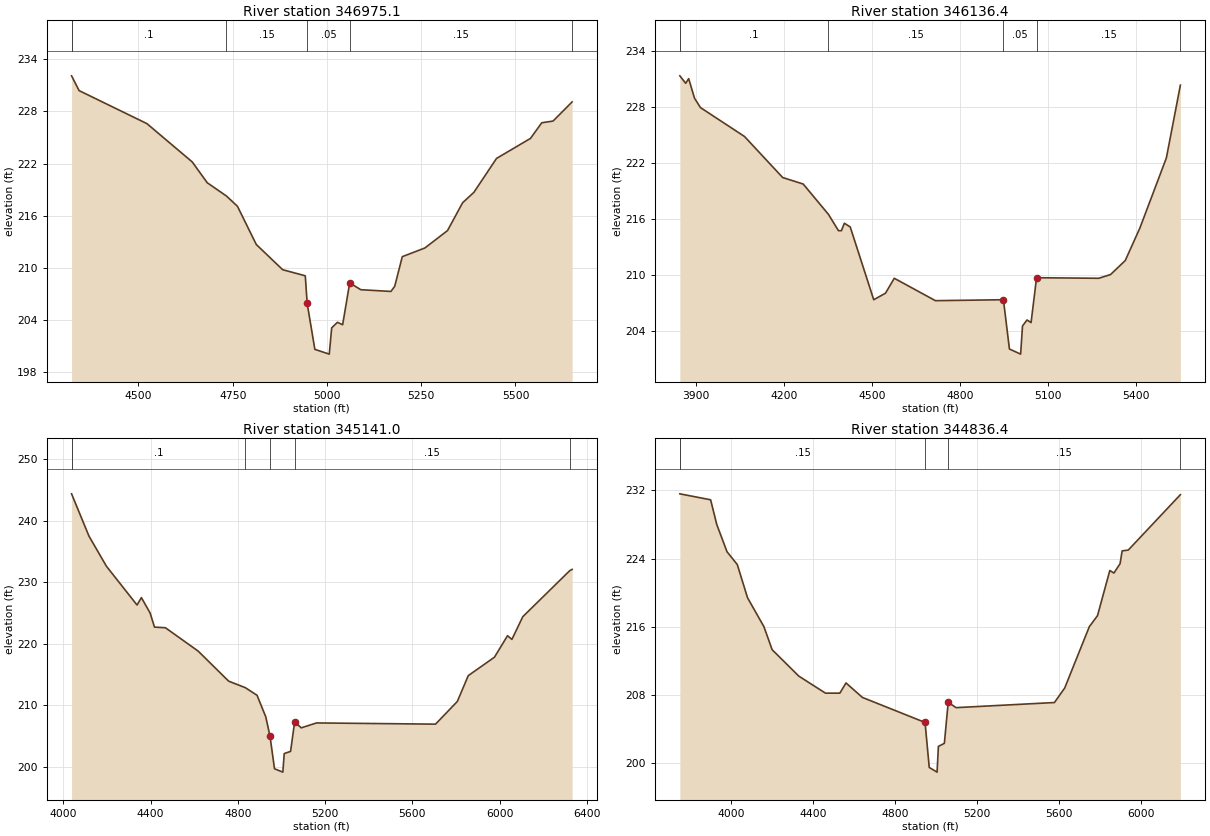
Type RM Length L Ch R = 1 ,346975.1,838.7,838.7,838.7
BEGIN DESCRIPTION:
Cross Section Little River 3.0
END DESCRIPTION:
#Sta/Elev= 30
  4322.5   232.1  4342.5   230.4  4522.5   226.6  4642.5   222.2  4682.5   219.8
  4733.2  218.28  4762.5   217.1  4812.5   212.7  4882.5   209.8  4942.5   209.1
  4947.5  205.92  4967.9  200.64  5006.1  200.09  5012.5  203.11  5027.8  203.75
  5041.6  203.47  5060.3  208.28  5089.8   207.5  5169.8   207.3  5179.8   207.9
  5199.8   211.3  5259.8   212.3  5319.8   214.3  5359.8   217.5  5389.8   218.7
  5449.8   222.6  5539.8   224.9  5569.8   226.7  5599.8   226.9  5650.3   229.1
#Mann= 6 , 1 , 0
 4322.50     0.2       0  4322.5     0.1       0  4733.2    0.15       0
  4947.5    0.05       0  5060.3    0.15       0  5650.3     0.2       0
Bank Sta=4947.50,5060.30
Exp/Cntr=0.3,0.1

Type RM Length L Ch R = 1 ,346136.4,995.4,995.4,995.4
BEGIN DESCRIPTION:
Cross Section Little River 2.0 CCX168
END DESCRIPTION:
#Sta/Elev= 30
    3846   231.3    3866   230.5    3876     231    3896   228.9    3916   227.9
    4066   224.8    4196   220.4    4266   219.7  4351.9  216.45    4386   214.7
    4396   214.7    4406   215.5    4426   215.1    4506   207.3    4546     208
    4576   209.6    4716   207.2  4947.5   207.3  4967.9  202.02  5006.1  201.47
  5012.5  204.49  5027.8  205.13  5041.6  204.85  5060.3  209.66  5272.2   209.6
  5312.2     210  5362.2   211.5  5412.2     215  5502.2   222.5  5549.9   230.3
#Mann= 6 , 1 , 0
 3846.00     0.2       0    3846     0.1       0  4351.9    0.15       0
  4947.5    0.05       0  5060.3    0.15       0  5549.9     0.2       0
Bank Sta=4947.50,5060.30
Exp/Cntr=0.3,0.1

Type RM Length L Ch R = 1 ,345141.0,304.6,304.6,304.6
BEGIN DESCRIPTION:
Cross Section Little River 1.0
END DESCRIPTION:
#Sta/Elev= 30
  4037.9   244.4  4117.9   237.5  4197.9   232.6  4337.9   226.3  4357.9   227.5
  4397.9     225  4417.9   222.7  4467.9   222.6  4617.9   218.8  4757.9   213.9
  4834.3  212.84  4887.9   211.6  4927.9   208.1  4947.5  204.92  4967.9  199.64
  5006.1  199.09  5012.5  202.11  5041.6  202.47  5060.3  207.28  5090.5   206.3
  5160.5   207.1  5705.9   206.9  5805.9   210.6  5855.9   214.8  5975.9   217.8
  6035.9   221.3  6055.9   220.7  6105.9   224.4  6320.9  231.89  6331.8   232.1
#Mann= 6 , 1 , 0
 4037.90     0.2       0  4037.9     0.1       0  4834.3    0.15       0
  4947.5    0.05       0  5060.3    0.15       0  6320.9     0.2       0
Bank Sta=4947.50,5060.30
Exp/Cntr=0.3,0.1

Type RM Length L Ch R = 1 ,344836.4,0,0,0
BEGIN DESCRIPTION:
Cross Section Little River 0.5
END DESCRIPTION:
#Sta/Elev= 30
  3752.1   231.6  3902.1   230.9  3932.1     228  3982.1   224.8  4032.1   223.3
  4082.1   219.4  4162.1     216  4202.1   213.3  4332.1   210.2  4462.1   208.2
  4532.1   208.2  4562.1   209.4  4642.1   207.7  4947.5  204.76  4967.9  199.48
  5006.1  198.93  5012.5  201.95  5041.6  202.31  5060.3  207.12  5098.8   206.5
  5578.2   207.1  5628.2   208.8  5748.2     216  5788.2   217.3  5848.2   222.6
  5868.2   222.3  5898.2   223.4  5908.2   224.9  5938.2     225  6192.2   231.5
#Mann= 5 , 1 , 0
 3752.10     0.2       0  3752.1    0.15       0  4947.5    0.05       0
  5060.3    0.15       0  6192.2     0.2       0
Bank Sta=4947.50,5060.30
Exp/Cntr=0.3,0.1

Chan Stop Cuts=-1