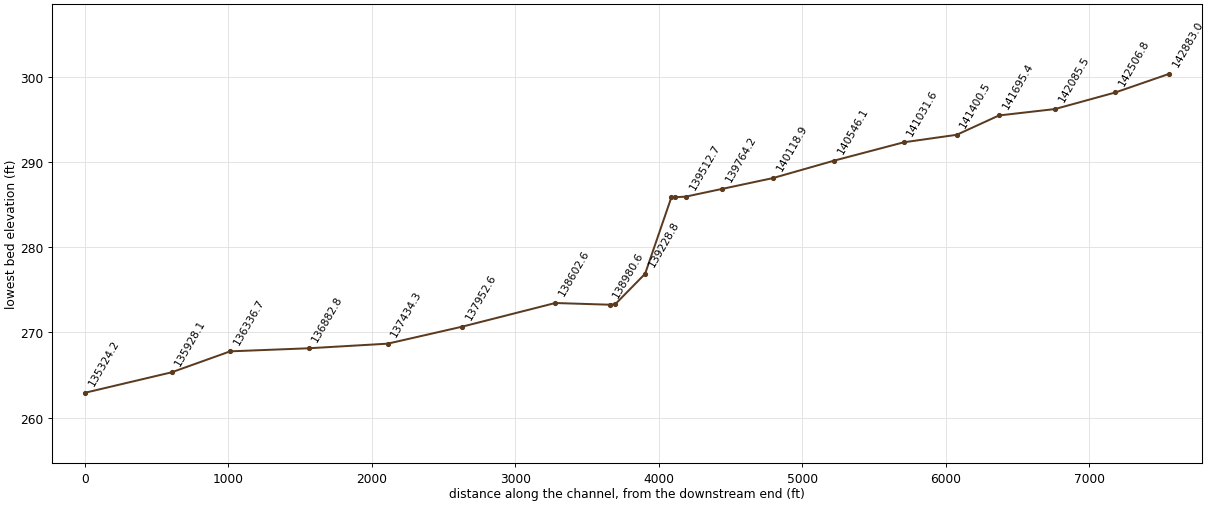
--- Moccasin_Creek_FINAL.prj (project) ---

Proj Title=Moccasin Creek - Detail Study
Current Plan=p02
Default Exp/Contr=.3,.1
English Units
Geom File=g01
Flow File=f01
Flow File=f02
Plan File=p01
Plan File=p02
Y Axis Title=Elevation
X Axis Title(PF)=Main Channel Distance
X Axis Title(XS)=Station
BEGIN DESCRIPTION:
NEUSE RIVER BASIN
Franklin-Wake County Line
END DESCRIPTION:
DSS Export Rating Curves= 0
DSS Export Rating Curve Sorted= 0
DSS Export Volume Flow Curves= 0
DXF OffsetX= 0
DXF OffsetY= 0
DXF ScaleX= 1
DXF ScaleY= 10

--- Moccasin_Creek_FINAL.p02 (plan) ---

Plan Title=Floodway
Version=Version 3.0.1  Mar 2001
Short Identifier=100YR_FW
Geom File=g01
Flow File=f02
Subcritical Flow
K Sum by GR= 0
Std Step Tol= 0.01
Critical Tol= 0.01
Num of Std Step Trials= 20
Max Error Tol= 0.3
Flow Tol Ratio= 0.001
Split Flow NTrial= 30
Split Flow Tol= 0.02
Split Flow Ratio= 0.02
Log Output Level= 0
Friction Slope Method= 1
Unsteady Friction Slope Method= 2
Parabolic Critical Depth
Global Vel Dist= 0 , 0 , 0
Global Log Level= 0
CheckData=True
Encroach Param=-1 ,10,10, 2
Encroach River=Moccasin Creek
Encroach Reach=Reach - 1
Encroach Node=142883.0
       1    4940    5140
Encroach Node=142506.8
       1    4890    5030
Encroach Node=142085.5
       1    4900    5125
Encroach Node=141695.4
       1    4975    5070
Encroach Node=141400.5
       1    4890    5095
Encroach Node=141031.6
       1    4880    5050
Encroach Node=140546.1
       1    4860    5025
Encroach Node=140118.9
       1    4575    5095
Encroach Node=139764.2
       1    4750    5110
Encroach Node=139512.7
       1    4920    5060
Encroach Node=139440.4
       1    4940    5027
Encroach Node=139425.9
       1    4940    5027
Encroach Node=139411.4
       1    4940    5027
Encroach Node=139228.8
       4       1
Encroach Node=139021.6
       1    4955    5037
Encroach Node=139001.1
       1    4955    5037
Encroach Node=138980.6
       1    4955    5037
Encroach Node=138602.6
       1    4900    5125
Encroach Node=137952.6
       1    4950    5125
Encroach Node=137434.3
       1    4700    5100
Encroach Node=136882.8
       4       1
Encroach Node=136336.7
       1    4910    5100
Encroach Node=135928.1
       1    4965    5175
Encroach Node=135324.2
       1    4900    5250
Encroach Node=134820.4
       1    4825    5115
Encroach Node=134563.1
       1    4920    5065
Encroach Node=134518.6
       1    4920    5065
Encroach Node=134474.1
       1    4920    5065
Encroach Node=134327.0
       1    4900    5105
Encroach Node=133904.0
       1    4940    5040
Encroach Node=133386.8
       4       1
Encroach Node=132897.3
       4       1
Encroach Node=132466.4
       1    4815    5125
Encroach Node=132105.9
       1    4730    5050
Encroach Node=131939.0
       1    4775    5100
Encroach Node=131747.7
       1    4800    5125
Encroach Node=131543.9
       4       1
Encroach Node=131200.0
       1    4975    5037
Encroach Node=131177.5
       1    4975    5037
Encroach Node=131155.0
       1    4975    5037
Encroach Node=130822.0
       1    4962    5050
Encroach Node=130443.0
       1    4957    5035
Encroach Node=130071.6
       1    4975    5100
Encroach Node=129838.9
       1    4965    5054
Encroach Node=129460.5
       1    4900    5025
Encroach Node=128933.7
       1    4910    5225
Encroach Node=128450.1
       1    4825    5125
Encroach Node=127746.3
       1    4825    5120
Encroach Node=127143.2
       1    4850    5225
Encroach Node=126527.0
       1    4775    5350
Encroach Node=126045.7
       1    4700    5190
Encroach Node=125457.5
       1    4655    5225
Encroach Node=124805.9
       1    4959    5280
Encroach Node=124784.9
       1    4959    5280
Encroach Node=124763.9
       1    4959    5280
Encroach Node=124014.4
       4       1
Encroach Node=123368.2
       1    4650    5065
Encroach Node=122925.1
       4       1
Encroach Node=122598.2
       1    4850    5175
Encroach Node=122143.5
       1    4700    5325
Encroach Node=121736.5
       1    4740    5275
Encroach Node=121068.7
       1    4785    5125
Encroach Node=120527.0
       1    4825    5050
Encroach Node=119927.0
       1    4790    5235
Encroach Node=119290.8
       1    4625    5175
Encroach Node=118650.0
       1    4700    5125
Encroach Node=118089.0
       1    4750    5250
Encroach Node=117432.3
       1    4625    5250
Encroach Node=116770.7
       1    4800    5125
Encroach Node=116102.9
       1    4925    5075
Encroach Node=115955.1
       1    4958    5042
Encroach Node=115927.1
       1    4958    5042
Encroach Node=115899.1
       1    4958    5042
Encroach Node=115658.3
       1    4850    5100
Encroach Node=115259.5
       1    4800    5100
Encroach Node=114797.6
       1    4775    5125
Encroach Node=114253.0
       1    4800    5070
Encroach Node=113726.0
       1    4870    5130
Encroach Node=113253.0
       1    4720    5160
Encroach Node=112173.5
       1    4550    5240
Encroach Node=111041.4
       1    4765    5150
Encroach Node=110079.9
       1    4939    5071
Encroach Node=109999.9
       1    4939    5071
Encroach Node=109919.9
       1    4939    5071
Encroach Node=109342.8
       4       1
Encroach Node=107795.2
       1    4400    5640
Encroach Node=106381.7
       1    4573    5417
Encroach Node=106367.2
       1    4573    5417
Encroach Node=106352.7
       1    4900    5150
Encroach Node=106193.6
       1    4945    5045
Encroach Node=106158.6
       1    4945    5045
Encroach Node=106123.6
       1    4945    5045
Encroach Node=105518.5
       1    4725    5140
Encroach Node=104823.3
       1    4700    5275
Encroach Node=104282.0
       1    4650    5140
Encroach Node=103679.7
       1    4550    5300
Encroach Node=103174.7
       1    4550    5310
Encroach Node=103154.7
       1    4550    5310
Encroach Node=103134.7
       1    4550    5310
Encroach Node=102912.8
       1    4635    5310
Encroach Node=102387.3
       4       1
Encroach Node=101806.5
       1    4650    5350
Encroach Node=101291.2
       1    4700    5300
Encroach Node=100646.0
       1    4650    5300
Encroach Node=100153.4
       1    4575    5250
Encroach Node=99443.3
       1    4750    5250
Encroach Node=98683.1
       1    4955    5045
Encroach Node=98661.6
       1    4955    5045
Encroach Node=98640.1
       1    4955    5045
Encroach Node=97238.8
       1    4650    5500
Encroach Node=96590.9
       1    4560    5125
Encroach Node=95987.2
       1    4652    5325
Encroach Node=95463.7
       4       1
Encroach Node=94837.3
       4       1
Encroach Node=94329.1
       4       1
Encroach Node=93527.0
       1    4460    5380
Encroach Node=92927.0
       1    4680    5575
Encroach Node=92194.9
       1    4430    5255
Encroach Node=91628.4
       1    4575    5400
Encroach Node=91018.7
       1    4350    5115
Encroach Node=89898.6
       1    4450    5035
Encroach Node=89778.1
       1    4450    5035
Encroach Node=89657.6
       1    4450    5035
Encroach Node=88694.6
       1    4370    5070
Encroach Node=88230.9
       1    4330    5040
Encroach Node=88203.4
       1    4330    5040
Encroach Node=88175.9
       1    4330    5040
Encroach Node=87844.9
       1    4640    5195
Computation Interval=1HOUR
Output Interval=1HOUR
Run HTab= 0
Run UNet= 0
Run PostProcess= 0
UNET Theta= 1
UNET ZTol= 0.02
UNET ZSATol= 0.1
UNET MxIter= 20
UNET MaxInSteps= 20
UNET DtIC= 0
UNET DtMin= 0
UNET MaxCRTS= 20
UNET WFStab= 2
UNET SFStab= 1
UNET WFX= 1
UNET SFX= 1
UNET Convert EG Bridges=-1
UNET Use Existing IB Tables=-1
Instantaneous Interval=1HOUR
Write IC File= 0
Write Velocity= 0
Write Detailed= 0

--- Moccasin_Creek_FINAL.p01 (plan) ---

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Plan Title=Multiple
Short Identifier=Plan01
Geom File=g01
Flow File=f01
Encroach Param=-1 ,0,0, 0

--- Moccasin_Creek_FINAL.f02 (steady flow) ---

Flow Title=Floodway
Version=Version 3.0.1  Mar 2001
Number of Profiles= 2
Profile Names=100-year,100-yr FW
River Rch & RM=Moccasin Creek,Reach - 1       ,142883.0
    1130    1130
River Rch & RM=Moccasin Creek,Reach - 1       ,142506.8
    1520    1520
River Rch & RM=Moccasin Creek,Reach - 1       ,137952.6
    1900    1900
River Rch & RM=Moccasin Creek,Reach - 1       ,135928.1
    2370    2370
River Rch & RM=Moccasin Creek,Reach - 1       ,131747.7
    3470    3470
River Rch & RM=Moccasin Creek,Reach - 1       ,127746.3
    3800    3800
River Rch & RM=Moccasin Creek,Reach - 1       ,124805.9
    4060    4060
River Rch & RM=Moccasin Creek,Reach - 1       ,123368.2
    4310    4310
River Rch & RM=Moccasin Creek,Reach - 1       ,121068.7
    4440    4440
River Rch & RM=Moccasin Creek,Reach - 1       ,117432.3
    4840    4840
River Rch & RM=Moccasin Creek,Reach - 1       ,111041.4
    5160    5160
River Rch & RM=Moccasin Creek,Reach - 1       ,107795.2
    6070    6070
River Rch & RM=Moccasin Creek,Reach - 1       ,102387.3
    6960    6960
River Rch & RM=Moccasin Creek,Reach - 1       ,99443.3
    7230    7230
River Rch & RM=Moccasin Creek,Reach - 1       ,94329.1
    7470    7470
Boundary for River Rch & Prof#=Moccasin Creek,Reach - 1       , 1
Up Type= 0
Dn Type= 3
Dn Slope=.00212
Boundary for River Rch & Prof#=Moccasin Creek,Reach - 1       , 2
Up Type= 0
Dn Type= 1
Dn Known WS=209.48
DSS Import GetInterval= 0
DSS Import GetPeak= 0
DSS Import FillOption= 0

--- Moccasin_Creek_FINAL.f01 (steady flow) ---

Flow Title= Multiple
Version=Version 3.0.1  Mar 2001
Number of Profiles= 4
Profile Names=10-year,50-year,100-year,500-year
River Rch & RM=Moccasin Creek,Reach - 1       ,142883.0
     394     847    1130    2030
River Rch & RM=Moccasin Creek,Reach - 1       ,142506.8
     537    1140    1520    2690
River Rch & RM=Moccasin Creek,Reach - 1       ,137952.6
     682    1430    1900    3340
River Rch & RM=Moccasin Creek,Reach - 1       ,135928.1
     862    1790    2370    4140
River Rch & RM=Moccasin Creek,Reach - 1       ,131747.7
    1340    2630    3470    6210
River Rch & RM=Moccasin Creek,Reach - 1       ,127746.3
    1480    2890    3800    6710
River Rch & RM=Moccasin Creek,Reach - 1       ,124805.9
    1590    3090    4060    7090
River Rch & RM=Moccasin Creek,Reach - 1       ,123368.2
    1690    3280    4310    7440
River Rch & RM=Moccasin Creek,Reach - 1       ,121068.7
    1750    3380    4440    7620
River Rch & RM=Moccasin Creek,Reach - 1       ,117432.3
    1910    3690    4840    8190
River Rch & RM=Moccasin Creek,Reach - 1       ,111041.4
    2050    3940    5160    8630
River Rch & RM=Moccasin Creek,Reach - 1       ,107795.2
    2430    4650    6070    9850
River Rch & RM=Moccasin Creek,Reach - 1       ,102387.3
    2810    5350    6960   11000
River Rch & RM=Moccasin Creek,Reach - 1       ,99443.3
    2930    5560    7230   11400
River Rch & RM=Moccasin Creek,Reach - 1       ,94329.1
    3030    5740    7470   11700
Boundary for River Rch & Prof#=Moccasin Creek,Reach - 1       , 1
Up Type= 0
Dn Type= 3
Dn Slope=.00212
Boundary for River Rch & Prof#=Moccasin Creek,Reach - 1       , 2
Up Type= 0
Dn Type= 3
Dn Slope=.00212
DSS Import GetInterval= 0
DSS Import GetPeak= 0
DSS Import FillOption= 0

--- Moccasin_Creek_FINAL.g01 (geometry) ---

Geom Title=Geom 01 by CodeH2 for Windows

River Reach=Moccasin Creek,Reach - 1
Reach XY= 2
              .5             .95              .5             .05

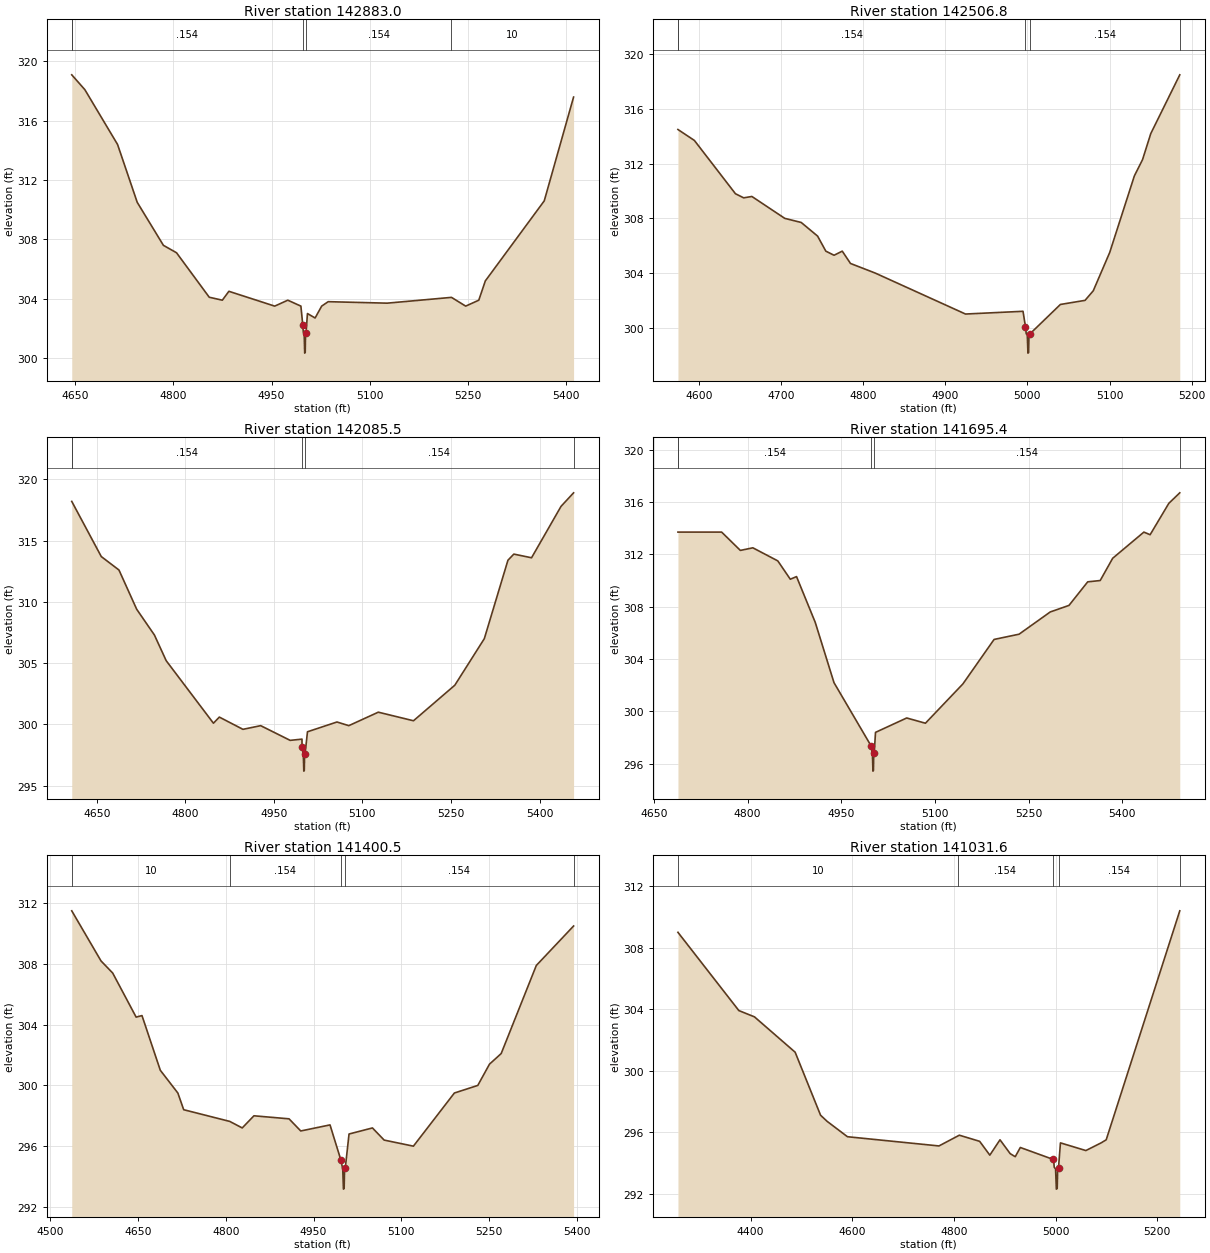
Type RM Length L Ch R = 1 ,142883.0,376.2,376.2,376.2
BEGIN DESCRIPTION:
Cross Section Moccasin Creek 90.0
END DESCRIPTION:
#Sta/Elev= 30
  4644.9   319.1  4664.9   318.1  4714.9   314.4  4744.9   310.5  4784.9   307.6
  4804.9   307.1  4854.9   304.1  4874.9   303.9  4884.9   304.5  4954.9   303.5
  4974.9   303.9  4994.9   303.5  4997.7  302.26  4998.6  301.75  4999.9  301.65
  5000.7  300.33  5001.5  300.37  5001.9  301.48  5002.8  301.72  5004.9     303
  5016.6   302.7  5026.6   303.5  5036.6   303.8  5126.6   303.7  5224.9  304.09
  5246.6   303.5  5266.6   303.9  5276.6   305.2  5366.6   310.6  5411.4   317.6
#Mann= 5 , 1 , 0
 4644.90    0.22       0  4644.9   0.154       0  4997.7   0.054       0
  5002.8   0.154       0  5224.9      10       0
Bank Sta=4997.70,5002.80
Exp/Cntr=0.3,0.1

Type RM Length L Ch R = 1 ,142506.8,421.3,421.3,421.3
BEGIN DESCRIPTION:
Cross Section Moccasin Creek 89.0
END DESCRIPTION:
#Sta/Elev= 30
  4574.7   314.5  4594.7   313.7  4644.7   309.8  4654.7   309.5  4664.7   309.6
  4704.7     308  4724.7   307.7  4744.7   306.7  4754.7   305.6  4764.7   305.3
  4774.7   305.6  4784.7   304.7  4814.7     304  4924.7     301  4994.7   301.2
  4997.7  300.07  4998.6  299.56  4999.9  299.46  5000.7  298.14  5001.5  298.18
  5001.9  299.29  5002.8  299.53  5040.2   301.7  5070.2     302  5080.2   302.7
  5100.2   305.5  5130.2   311.1  5140.2   312.3  5150.2   314.2  5185.5   318.5
#Mann= 5 , 1 , 0
 4574.70    0.22       0  4574.7   0.154       0  4997.7   0.054       0
  5002.8   0.154       0  5185.5    0.22       0
Bank Sta=4997.70,5002.80
Exp/Cntr=0.3,0.1

Type RM Length L Ch R = 1 ,142085.5,390.1,390.1,390.1
BEGIN DESCRIPTION:
Cross Section Moccasin Creek 88.0
END DESCRIPTION:
#Sta/Elev= 30
  4607.6   318.2  4657.6   313.7  4687.6   312.6  4717.6   309.4  4747.6   307.3
  4767.6   305.2  4847.6   300.1  4857.6   300.6  4897.6   299.6  4927.6   299.9
  4977.6   298.7  4997.6   298.8  4997.7  298.12  4999.9  297.51  5000.7  296.19
  5001.5  296.23  5001.9  297.34  5002.8  297.58  5006.9   299.4  5056.9   300.2
  5076.9   299.9  5126.9     301  5186.5   300.3  5256.5   303.2  5306.5     307
  5346.5   313.4  5356.5   313.9  5386.5   313.6  5436.5   317.8  5457.7   318.9
#Mann= 5 , 1 , 0
 4607.60    0.22       0  4607.6   0.154       0  4997.7   0.054       0
  5002.8   0.154       0  5457.7    0.22       0
Bank Sta=4997.70,5002.80
Exp/Cntr=0.3,0.1

Type RM Length L Ch R = 1 ,141695.4,294.9,294.9,294.9
BEGIN DESCRIPTION:
Cross Section Moccasin Creek 87.5
END DESCRIPTION:
#Sta/Elev= 30
  4688.3   313.7  4758.3   313.7  4788.3   312.3  4808.3   312.5  4848.3   311.5
  4868.3   310.1  4878.3   310.3  4908.3   306.8  4938.3   302.2  4997.7  297.37
  4999.9  296.76  5000.7  295.44  5001.5  295.48  5001.9  296.59  5002.8  296.83
  5004.8   298.4  5054.8   299.5  5084.8   299.1  5144.8   302.1  5194.8   305.5
  5234.8   305.9  5284.8   307.6  5314.8   308.1  5344.8   309.9  5364.8     310
  5384.8   311.7  5434.8   313.7  5444.8   313.5  5474.8   315.9  5492.3   316.7
#Mann= 5 , 1 , 0
 4688.30    0.22       0  4688.3   0.154       0  4997.7   0.054       0
  5002.8   0.154       0  5492.3    0.22       0
Bank Sta=4997.70,5002.80
Exp/Cntr=0.3,0.1

Type RM Length L Ch R = 1 ,141400.5,368.9,368.9,368.9
BEGIN DESCRIPTION:
Cross Section Moccasin Creek 87.0
END DESCRIPTION:
#Sta/Elev= 30
  4536.8   311.5  4586.8   308.2  4606.8   307.4  4646.8   304.5  4656.8   304.6
  4688.1     301  4718.1   299.5  4728.1   298.4  4806.8  297.63  4828.1   297.2
  4848.1     298  4908.1   297.8  4928.1     297  4978.1   297.4 4996.55   295.1
 4999.85  294.49 5001.05  293.17 5002.25  293.21 5002.85  294.32  5004.2  294.56
  5010.6   296.8  5050.6   297.2  5070.6   296.4  5120.6     296  5190.6   299.5
  5230.6     300  5250.6   301.4  5270.6   302.1  5330.6   307.9  5394.3   310.5
#Mann= 5 , 1 , 0
 4536.80      10       0  4806.8   0.154       0 4996.55   0.054       0
  5004.2   0.154       0  5394.3    0.22       0
Bank Sta=4996.55,5004.20
Exp/Cntr=0.3,0.1

Type RM Length L Ch R = 1 ,141031.6,485.5,485.5,485.5
BEGIN DESCRIPTION:
Cross Section Moccasin Creek 86.0
END DESCRIPTION:
#Sta/Elev= 30
  4257.1     309  4377.1   303.9  4377.6   303.9  4407.6   303.5  4487.6   301.2
  4537.6   297.1  4550.5   296.7  4590.5   295.7  4770.5   295.1  4807.1  295.74
  4810.5   295.8  4850.5   295.4  4870.5   294.5  4890.5   295.5  4910.5   294.6
  4920.5   294.4  4930.5     295  4995.4  294.22  4996.4  294.02  4997.2  293.71
  4999.8  293.61  5001.4  292.29    5003  292.33  5003.8  293.44  5005.6  293.68
  5009.4   295.3  5059.4   294.8  5089.4   295.3  5099.4   295.5  5244.1   310.4
#Mann= 5 , 1 , 0
 4257.10      10       0  4807.1   0.154       0  4995.4   0.054       0
  5005.6   0.154       0  5244.1    0.22       0
Bank Sta=4995.40,5005.60
Exp/Cntr=0.3,0.1

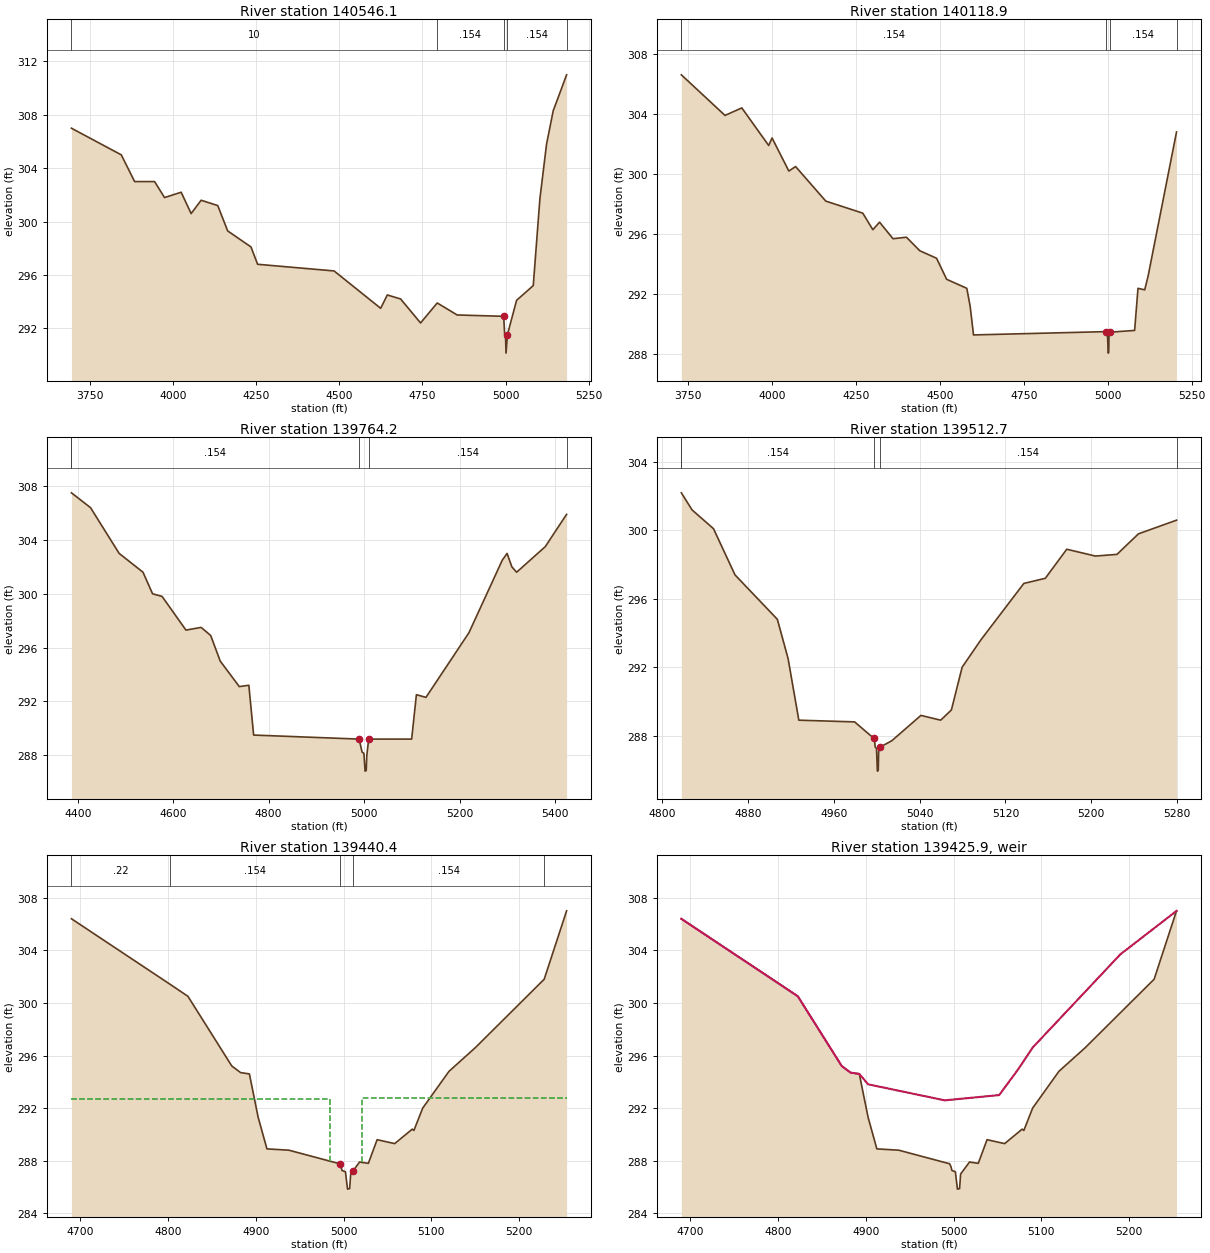
Type RM Length L Ch R = 1 ,140546.1,427.2,427.2,427.2
BEGIN DESCRIPTION:
Cross Section Moccasin Creek 85.0
END DESCRIPTION:
#Sta/Elev= 30
  3694.5     307  3844.5     305  3884.5     303  3944.5     303  3974.5   301.8
  4024.5   302.2  4054.5   300.6  4084.5   301.6  4134.5   301.2  4164.4   299.3
  4234.4   298.1  4254.4   296.8  4484.4   296.3  4624.4   293.5  4644.4   294.5
  4684.4   294.2  4744.4   292.4  4794.5   293.9  4854.4     293  4994.4   292.9
  4997.2  291.56  4999.8  291.46  5001.4  290.14  5005.6  291.53  5033.2   294.1
  5083.2   295.2  5103.2   301.7  5123.2   305.8  5143.2   308.3  5183.5     311
#Mann= 5 , 1 , 0
 3694.50      10       0  4794.5   0.154       0  4994.4   0.054       0
  5005.6   0.154       0  5183.5    0.22       0
Bank Sta=4994.40,5005.60
Exp/Cntr=0.3,0.1

Type RM Length L Ch R = 1 ,140118.9,354.7,354.7,354.7
BEGIN DESCRIPTION:
Cross Section Moccasin Creek 84.0
END DESCRIPTION:
#Sta/Elev= 30
  3730.9   306.6  3860.9   303.9  3910.9   304.4  3990.9   301.9  4000.9   302.4
  4050.9   300.2  4070.9   300.5  4160.9   298.2  4270.9   297.4  4300.9   296.3
  4320.9   296.8  4360.9   295.7  4400.9   295.8  4440.6   294.9  4490.6   294.4
  4520.6     293  4580.6   292.4  4590.6   291.2  4600.6   289.3  4995.4  289.52
  4999.8  289.11  5001.4  288.09    5003  288.13  5003.8  289.24  5005.6  289.48
  5080.1   289.6  5090.1   292.4  5110.1   292.3  5120.1   293.2  5204.8   302.8
#Mann= 5 , 1 , 0
 3730.90    0.22       0  3730.9   0.154       0  4995.4   0.054       0
  5005.6   0.154       0  5204.8    0.22       0
Bank Sta=4995.40,5005.60
Exp/Cntr=0.3,0.1

Type RM Length L Ch R = 1 ,139764.2,251.5,251.5,251.5
BEGIN DESCRIPTION:
Cross Section Moccasin Creek 83.5
END DESCRIPTION:
#Sta/Elev= 30
  4386.8   307.5  4426.8   306.4  4486.8     303  4536.8   301.6  4556.8     300
  4576.8   299.8  4626.8   297.3  4658.6   297.5  4678.6   296.9  4698.6     295
  4738.6   293.1  4758.6   293.2  4768.6   289.5  4989.7   289.2  4995.8  288.24
  4999.7  288.14  5002.1  286.82  5004.5  286.86  5005.7  287.97  5009.7   289.2
  5099.7   289.2  5109.7   292.5  5129.7   292.3  5219.7   297.1  5289.7   302.5
  5299.7     303  5309.7     302  5319.7   301.6  5379.7   303.5  5424.4   305.9
#Mann= 5 , 1 , 0
 4386.80    0.22       0  4386.8   0.154       0  4989.7   0.054       0
  5009.7   0.154       0  5424.4    0.22       0
Bank Sta=4989.70,5009.70
Exp/Cntr=0.3,0.1

Type RM Length L Ch R = 1 ,139512.7,72.3,72.3,72.3
BEGIN DESCRIPTION:
Cross Section Moccasin Creek XS167
END DESCRIPTION:
#Sta/Elev= 30
    4818   302.2    4828   301.2    4848   300.1    4868   297.4  4907.5   294.8
  4917.5   292.5  4927.5   288.9  4979.5   288.8    4994  288.02  4997.7  287.85
  4998.2  287.65  4998.6  287.34  4999.9  287.24  5000.7  285.92  5001.5  285.96
  5001.9  287.07  5002.8  287.31  5014.2   287.7  5041.3  289.18  5059.7   288.9
  5069.7   289.5  5079.7     292  5097.2   293.6  5137.2   296.9  5157.2   297.2
  5177.2   298.9    5204   298.5    5224   298.6    5244   299.8  5279.5   300.6
#Mann= 5 , 1 , 0
 4818.00    0.22       0    4818   0.154       0  4997.7   0.054       0
  5002.8   0.154       0  5279.5    0.22       0
Bank Sta=4997.70,5002.80
Exp/Cntr=0.5,0.3

Type RM Length L Ch R = 1 ,139440.4,29,29,29
BEGIN DESCRIPTION:
Upstream Section of Bridge/Culvert/Weir
END DESCRIPTION:
#Sta/Elev= 28
    4690  306.41  4802.7  301.41  4822.7  300.51  4872.7  295.21  4882.7  294.71
  4892.7  294.61  4902.7  291.31  4912.7  288.91  4937.7  288.81  4995.5  287.78
    4997  287.58  4998.2  287.27  5002.1  287.17  5004.5  285.85  5006.9  285.89
  5008.1     287  5010.8  287.24  5018.2  287.91  5028.2  287.81  5038.2  289.61
  5058.2  289.31  5078.2  290.41  5080.1  290.31  5090.1  292.01  5120.1  294.81
  5150.1  296.61  5228.5  301.81    5254  307.01
#Mann= 5 , 1 , 0
 4690.00    0.22       0  4802.7   0.154       0  4995.5   0.054       0
  5010.8   0.154       0  5228.5    0.22       0
#XS Ineff= 2 , 0
       0    4985   292.7    5021       0   292.8
Bank Sta=4995.50,5010.80
Exp/Cntr=0.5,0.3

Type RM Length L Ch R = 5 ,139425.9,,,
BEGIN DESCRIPTION:
Moccasin Creek 83.0 (Breached Dam)
Structure ID:
END DESCRIPTION:
#Inline Weir SE= 12
    4690   306.4  4822.7  300.51  4872.7  295.21  4882.7  294.71  4892.7  294.61
  4902.7  293.82    4990   292.6    5052     293    5073   294.9  5090.1  296.61
    5190   303.7    5254     307
IW Dist,WD,Coef,Skew,MaxSub,Min_El,Is_Ogee,SpillHt,DesHd
10.0,9.0,3.0,,0.95,, 0 ,,,1.9,1.9,

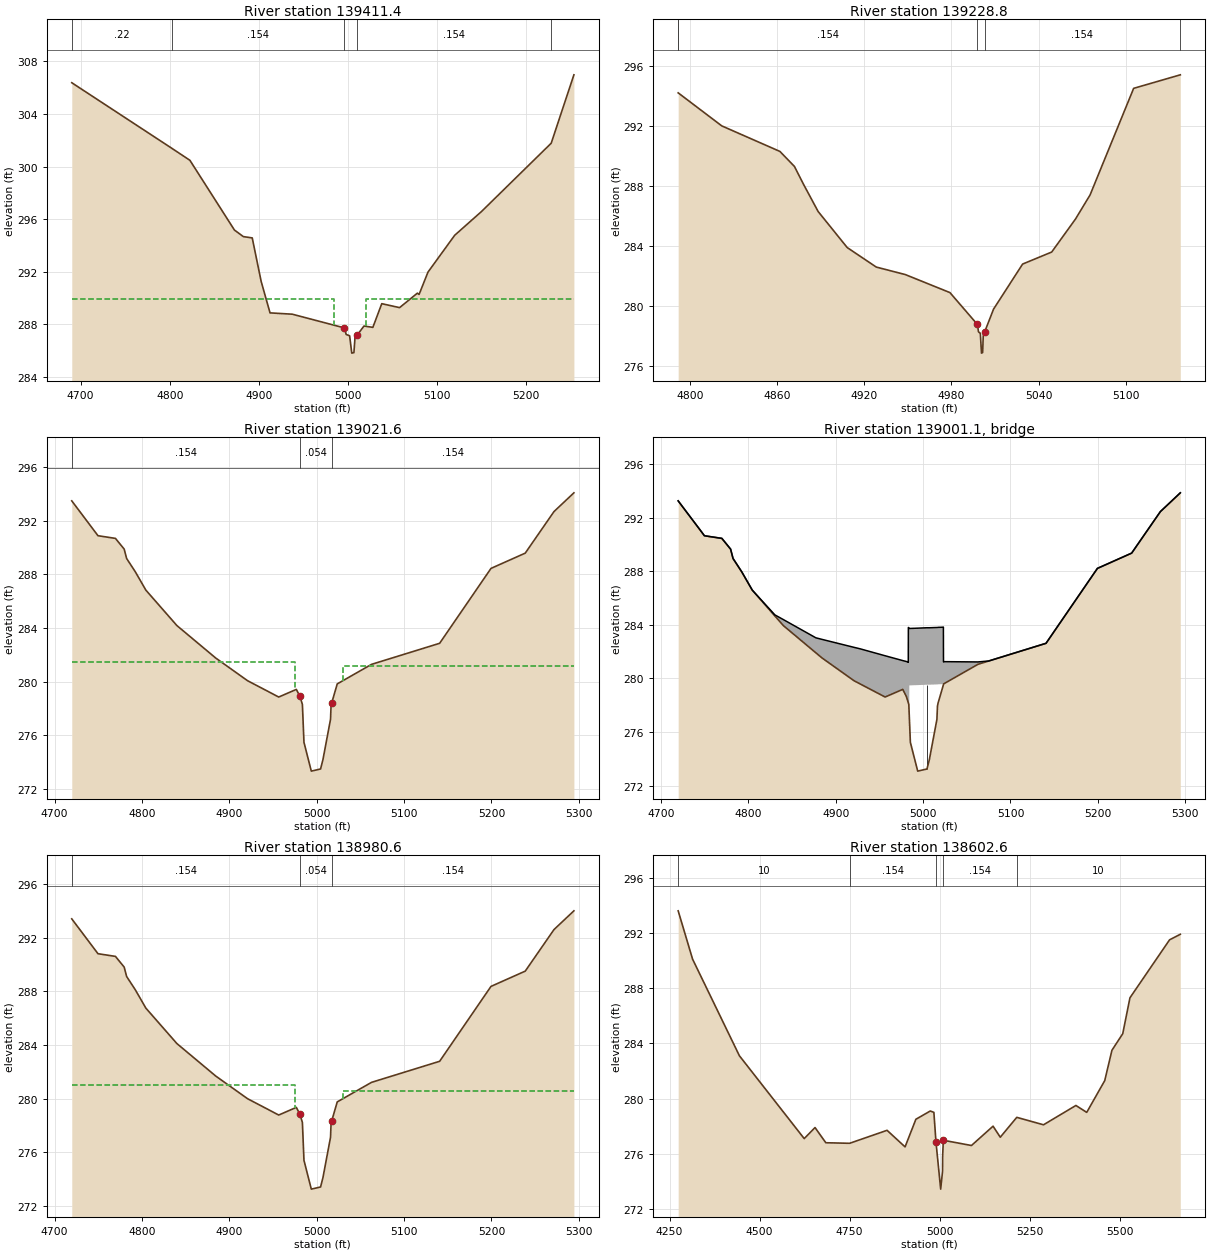
Type RM Length L Ch R = 1 ,139411.4,182.6,182.6,182.6
BEGIN DESCRIPTION:
Downstream Section of Bridge/Culvert/Weir
END DESCRIPTION:
#Sta/Elev= 28
    4690  306.38  4802.7  301.38  4822.7  300.48  4872.7  295.18  4882.7  294.68
  4892.7  294.58  4902.7  291.28  4912.7  288.88  4937.7  288.78  4995.5  287.75
    4997  287.55  4998.2  287.24  5002.1  287.14  5004.5  285.82  5006.9  285.86
  5008.1  286.97  5010.8  287.21  5018.2  287.88  5028.2  287.78  5038.2  289.58
  5058.2  289.28  5078.2  290.38  5080.1  290.28  5090.1  291.98  5120.1  294.78
  5150.1  296.58  5228.5  301.78    5254  306.98
#Mann= 5 , 1 , 0
 4690.00    0.22       0  4802.7   0.154       0  4995.5   0.054       0
  5010.8   0.154       0  5228.5    0.22       0
#XS Ineff= 2 , 0
       0    4985   289.9    5021       0   289.9
Bank Sta=4995.50,5010.80
Exp/Cntr=0.5,0.3

Type RM Length L Ch R = 1 ,139228.8,207.2,207.2,207.2
BEGIN DESCRIPTION:
Cross Section Moccasin Creek 82.5
END DESCRIPTION:
#Sta/Elev= 25
    4792   294.2    4822     292    4862   290.3    4872   289.3  4878.3   288.1
  4888.3   286.3  4908.3   283.9  4928.3   282.6  4948.3   282.1    4979   280.9
  4997.7   278.8  4998.2   278.6  4998.6  278.29  4999.9  278.19  5000.7  276.87
  5001.5  276.91  5001.9  278.02  5002.8  278.26    5009   279.8    5029   282.8
    5049   283.6  5065.4   285.8  5075.4   287.4  5105.4   294.5  5137.5   295.4
#Mann= 5 , 1 , 0
 4792.00    0.22       0    4792   0.154       0  4997.7   0.054       0
  5002.8   0.154       0  5137.5    0.22       0
Bank Sta=4997.70,5002.80
Exp/Cntr=0.5,0.3

Type RM Length L Ch R = 1 ,139021.6,41,41,41
BEGIN DESCRIPTION:
Upstream Section of Bridge/Culvert/Weir
END DESCRIPTION:
#Sta/Elev= 28
  4719.6  293.49  4749.6  290.89  4769.6  290.69  4779.6  289.89  4782.4  289.19
  4792.4  288.19  4804.4  286.83    4840  284.18  4884.4  281.76  4920.8  280.07
  4956.5  278.85  4976.7  279.42  4980.8  278.89  4983.6   278.3  4985.4  275.47
  4993.8  273.32  5004.4  273.48  5007.1  274.17  5015.8  277.19  5016.4  278.17
  5017.1   278.4  5023.5  279.83  5062.8  281.29  5140.7  282.86  5199.5  288.45
  5238.7  289.59  5271.6  292.69  5294.4  294.09
#Mann= 3 , 1 , 0
 4719.60   0.154       0  4980.8   0.054       0  5017.1   0.154       0
#XS Ineff= 2 , 0
       0    4975   281.5    5030       0   281.2
Bank Sta=4980.80,5017.10
Exp/Cntr=0.5,0.3

Type RM Length L Ch R = 3 ,139001.1,,,
BEGIN DESCRIPTION:
Henry Baker Rd
Structure ID: FRMCCR9
END DESCRIPTION:
Bridge Culvert--1,0,-1,-1, 0
Deck Dist Width WeirC Skew NumUp NumDn MinLoCord MaxHiCord MaxSubmerge Is_Ogee
10,21,2.6,,56,56,,,0.95,0,1,1,,
  4719.6  4724.2  4744.8  4749.6  4752.2  4769.6  4779.6  4782.4  4786.5  4792.4
  4804.4  4830.3    4840  4877.2  4884.4  4920.8  4927.8  4956.5  4976.7  4980.8
  4982.9 4982.99  4983.1 4983.21  4983.6    4984 4984.11  4984.2  4984.3  4985.4
  4993.8  5004.4  5007.1  5015.8  5016.4  5017.1  5022.7 5022.79  5022.9 5022.99
  5023.1  5023.2 5023.31  5023.5  5024.3  5062.8  5075.1  5127.3  5140.7  5179.3
  5199.5  5231.5  5238.7  5271.6  5283.7  5294.4
  293.25  292.85  291.07  290.65  290.62  290.45  289.65  288.95  288.54  287.95
  286.59  284.74  284.39  283.03  282.91  282.32  282.21  281.69  281.33  281.26
  281.22   281.2   283.8   283.8  283.77  283.73  283.73  283.73  283.73  283.73
  283.75  283.78  283.78   283.8   283.8  283.81  283.82  283.82  283.82  283.83
  283.83  283.83  281.23  281.23  281.25  281.23   281.3  282.35  282.62  286.29
  288.21  289.14  289.35  292.45  293.19  293.85
  293.25  292.85  291.07  290.65  290.62  290.45  289.65  288.95  288.54  287.95
  286.59  284.66  283.94  281.91  281.52  279.83  279.59  278.61  279.18  278.65
  278.21  278.19  278.17  278.14  278.06  277.43  277.26  279.48  279.48  279.48
   279.5  279.53  279.53  279.55  279.55  279.56  279.57  279.57  279.46  279.48
   279.5  279.52  279.55  279.59  279.62  281.05   281.3  282.35  282.62  286.29
  288.21  289.14  289.35  292.45  293.19  293.85
  4719.6  4724.2  4744.8  4749.6  4752.2  4769.6  4779.6  4782.4  4786.5  4792.4
  4804.4  4830.3    4840  4877.2  4884.4  4920.8  4927.8  4956.5  4976.7  4980.8
  4982.9 4982.99  4983.1 4983.21  4983.6    4984 4984.11  4984.2  4984.3  4985.4
  4993.8  5004.4  5007.1  5015.8  5016.4  5017.1  5022.7 5022.79  5022.9 5022.99
  5023.1  5023.2 5023.31  5023.5  5024.3  5062.8  5075.1  5127.3  5140.7  5179.3
  5199.5  5231.5  5238.7  5271.6  5283.7  5294.4
   293.2  292.81  291.03  290.61  290.58  290.41  289.61  288.91   288.5  287.91
  286.55  284.74  284.39  283.03  282.91  282.32  282.21  281.69  281.33  281.26
  281.22   281.2   283.8   283.8  283.77  283.73  283.73  283.73  283.73  283.73
  283.75  283.78  283.78   283.8   283.8  283.81  283.82  283.82  283.82  283.83
  283.83  283.83  281.23  281.23  281.25  281.23  281.26  282.31  282.58  286.25
  288.17   289.1  289.31  292.41  293.15   293.8
  293.15  292.75  290.97  290.55  290.52  290.35  289.55  288.85  288.44  287.85
  286.49  284.56  283.84  281.81  281.42  279.73  279.49  278.51  279.08  278.55
  278.11  278.09  278.07  278.04  277.96  277.33  277.16  279.38  279.38  279.38
   279.4  279.43  279.43  279.45  279.45  279.46  279.47  279.47  279.36  279.38
   279.4  279.42  279.45  279.49  279.52  280.95   281.2  282.25  282.52  286.19
  288.11  289.04  289.25  292.35  293.09  293.75
Pier Skew, UpSta & Num, DnSta & Num=,5004.4, 2 ,5004.4, 2 , 0 , 0 , 0 ,,
       1       1
  272.23  280.53
       1       1
  272.13  280.43
BR Coef= 1 , 1 , 0 ,1.25, 0 ,,,0.8,0,2,0,
Wspro=,,,, 1 ,,,, 0 ,,,, 0 ,,,,-1 ,-1 ,-1 , 0 , 0 , 0 , 0 , 0
BC Design=,, 0 ,, 0 ,,,,,,
BR U #Sta/Elev= 56
  4719.6  293.25  4724.2  292.85  4744.8  291.07  4749.6  290.65  4752.2  290.62
  4769.6  290.45  4779.6  289.65  4782.4  288.95  4786.5  288.54  4792.4  287.95
  4804.4  286.59  4830.3  284.66    4840  283.94  4877.2  281.91  4884.4  281.52
  4920.8  279.83  4927.8  279.59  4956.5  278.61  4976.7  279.18  4980.8  278.65
  4982.9  278.21 4982.99  278.19  4983.1  278.17 4983.21  278.14  4983.6  278.06
    4984  277.43 4984.11  277.26  4984.2  277.12  4984.3  276.96  4985.4  275.23
  4993.8  273.08  5004.4  273.24  5007.1  273.93  5015.8  276.95  5016.4  277.93
  5017.1  278.16  5022.7  279.41 5022.79  279.43  5022.9  279.46 5022.99  279.48
  5023.1   279.5  5023.2  279.52 5023.31  279.55  5023.5  279.59  5024.3  279.62
  5062.8  281.05  5075.1   281.3  5127.3  282.35  5140.7  282.62  5179.3  286.29
  5199.5  288.21  5231.5  289.14  5238.7  289.35  5271.6  292.45  5283.7  293.19
  5294.4  293.85
BR U #Mann= 3
 4719.60   0.154  4980.8   0.054  5017.1   0.154
BR U Banks=4980.80,5017.10
BR D #Sta/Elev= 56
  4719.6  293.15  4724.2  292.75  4744.8  290.97  4749.6  290.55  4752.2  290.52
  4769.6  290.35  4779.6  289.55  4782.4  288.85  4786.5  288.44  4792.4  287.85
  4804.4  286.49  4830.3  284.56    4840  283.84  4877.2  281.81  4884.4  281.42
  4920.8  279.73  4927.8  279.49  4956.5  278.51  4976.7  279.08  4980.8  278.55
  4982.9  278.11 4982.99  278.09  4983.1  278.07 4983.21  278.04  4983.6  277.96
    4984  277.33 4984.11  277.16  4984.2  277.02  4984.3  276.86  4985.4  275.13
  4993.8  272.98  5004.4  273.14  5007.1  273.83  5015.8  276.85  5016.4  277.83
  5017.1  278.06  5022.7  279.31 5022.79  279.33  5022.9  279.36 5022.99  279.38
  5023.1   279.4  5023.2  279.42 5023.31  279.45  5023.5  279.49  5024.3  279.52
  5062.8  280.95  5075.1   281.2  5127.3  282.25  5140.7  282.52  5179.3  286.19
  5199.5  288.11  5231.5  289.04  5238.7  289.25  5271.6  292.35  5283.7  293.09
  5294.4  293.75
BR D #Mann= 3
 4719.60   0.154  4980.8   0.054  5017.1   0.154
BR D Banks=4980.80,5017.10

Type RM Length L Ch R = 1 ,138980.6,378,378,378
BEGIN DESCRIPTION:
Downstream Section of Bridge/Culvert/Weir
END DESCRIPTION:
#Sta/Elev= 28
  4719.6  293.41  4749.6  290.81  4769.6  290.61  4779.6  289.81  4782.4  289.11
  4792.4  288.11  4804.4  286.75    4840   284.1  4884.4  281.68  4920.8  279.99
  4956.5  278.77  4976.7  279.34  4980.8  278.81  4983.6  278.22  4985.4  275.39
  4993.8  273.24  5004.4   273.4  5007.1  274.09  5015.8  277.11  5016.4  278.09
  5017.1  278.32  5023.5  279.75  5062.8  281.21  5140.7  282.78  5199.5  288.37
  5238.7  289.51  5271.6  292.61  5294.4  294.01
#Mann= 3 , 1 , 0
 4719.60   0.154       0  4980.8   0.054       0  5017.1   0.154       0
#XS Ineff= 2 , 0
       0    4975     281    5030       0   280.6
Bank Sta=4980.80,5017.10
Exp/Cntr=0.5,0.3

Type RM Length L Ch R = 1 ,138602.6,650,650,650
BEGIN DESCRIPTION:
Cross Section Moccasin Creek 82.0
END DESCRIPTION:
#Sta/Elev= 30
    4274   293.6    4314   290.1    4444   283.1  4623.9   277.1  4653.9   277.9
  4683.9   276.8    4750  276.76  4853.9   277.7  4903.9   276.5  4933.9   278.5
  4973.9   279.1  4983.9     279 4989.66  276.86 5002.75  273.44 5007.92  274.74
 5008.14  275.74 5010.01  276.98  5088.2   276.6  5148.2     278  5168.2   277.2
    5214  278.64  5288.2   278.1  5378.2   279.5  5408.2     279  5458.2   281.3
  5478.2   283.5  5508.2   284.7  5528.2   287.3  5638.2   291.5    5668   291.9
#Mann= 5 , 1 , 0
 4274.00      10       0    4750   0.154       0 4989.66   0.054       0
 5010.01   0.154       0    5214      10       0
Bank Sta=4989.66,5010.01
Exp/Cntr=0.3,0.1

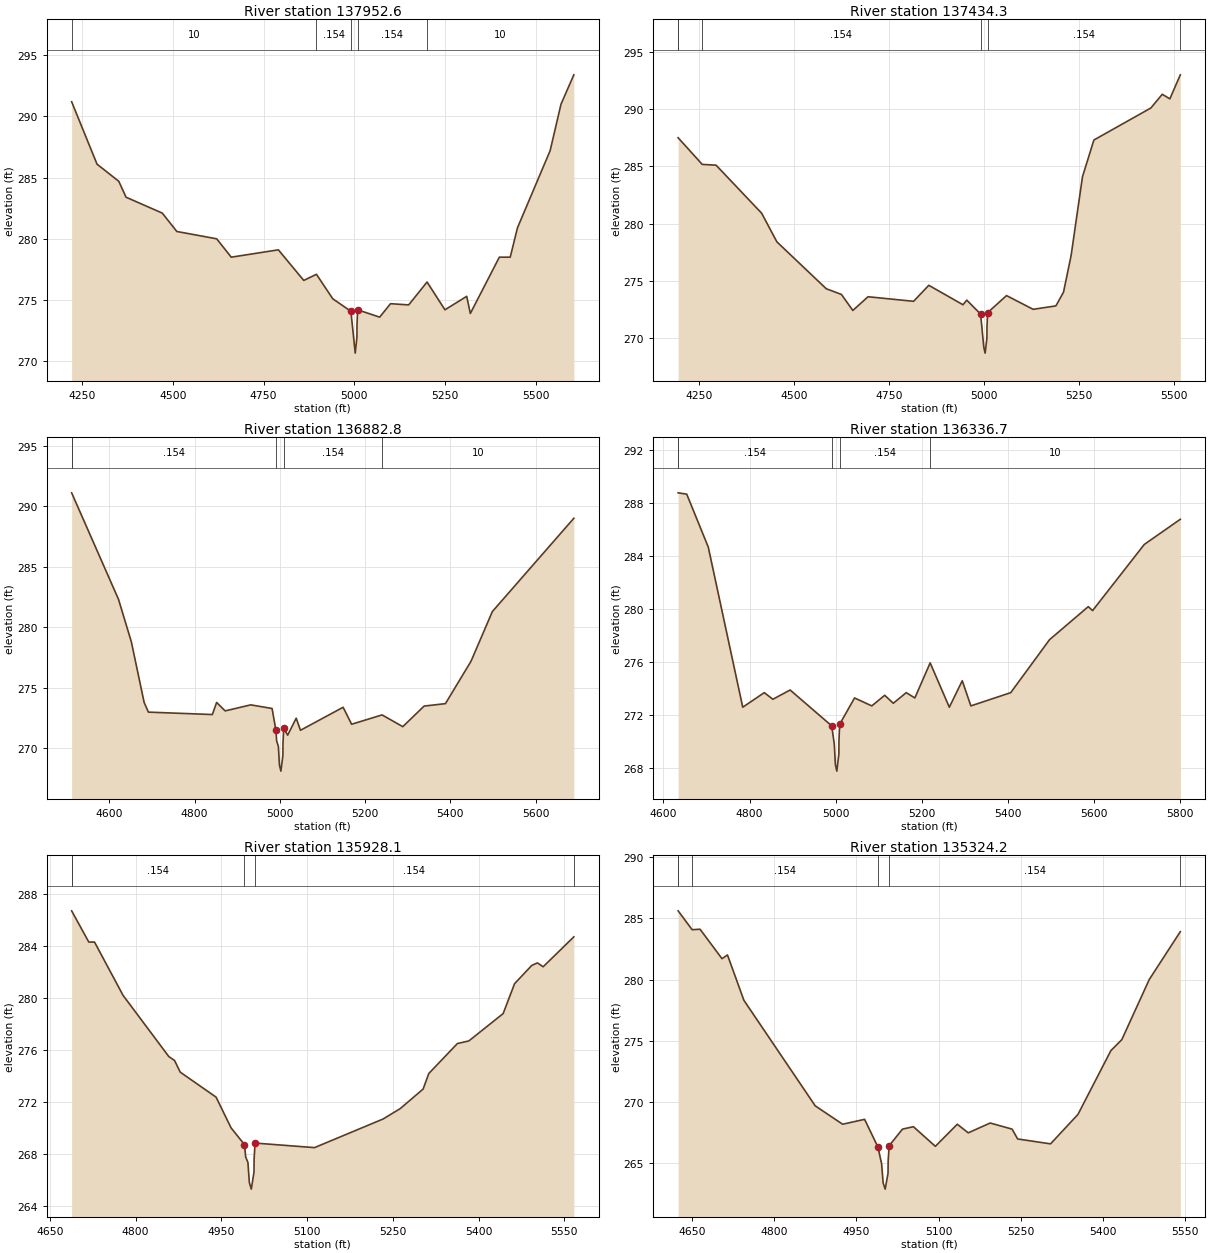
Type RM Length L Ch R = 1 ,137952.6,518.3,518.3,518.3
BEGIN DESCRIPTION:
Cross Section Moccasin Creek 81.0
END DESCRIPTION:
#Sta/Elev= 30
  4220.6   291.2  4290.6   286.1  4350.6   284.7  4370.6   283.4  4470.6   282.1
  4510.6   280.6  4620.6     280  4660.6   278.5  4790.6   279.1  4860.6   276.6
  4895.6   277.1  4940.6   275.1  4990.6  274.08  5002.5  270.66  5007.2  271.96
  5007.4  272.96  5009.1   274.2  5069.9   273.6  5099.9   274.7  5149.9   274.6
  5200.6  276.47  5249.9   274.2  5309.9   275.3  5319.9   273.9  5399.9   278.5
  5429.9   278.5  5449.9   280.9  5539.9   287.2  5569.9     291  5605.3   293.4
#Mann= 5 , 1 , 0
 4220.60      10       0  4895.6   0.154       0  4990.6   0.054       0
  5009.1   0.154       0  5200.6      10       0
Bank Sta=4990.60,5009.10
Exp/Cntr=0.3,0.1

Type RM Length L Ch R = 1 ,137434.3,551.5,551.5,551.5
BEGIN DESCRIPTION:
Cross Section Moccasin Creek 80.0
END DESCRIPTION:
#Sta/Elev= 30
  4194.2   287.5  4257.7  285.17  4294.2   285.1  4414.2   280.9  4454.2   278.4
  4584.2   274.3  4624.2   273.8  4654.2   272.4  4694.2   273.6  4814.2   273.2
  4854.2   274.6  4944.2   272.9  4954.2   273.3  4990.6  272.09  4999.1  269.17
  5002.5  268.67  5007.2  269.97  5007.4  270.97  5009.1  272.21  5058.9   273.7
  5128.9   272.5  5188.9   272.8  5208.9     274  5228.9   277.2  5258.9   284.1
  5288.9   287.3  5438.9   290.1  5468.9   291.3  5488.9   290.9  5516.4     293
#Mann= 6 , 1 , 0
 4194.20    0.22       0  4194.2   0.088       0  4257.7   0.154       0
  4990.6   0.054       0  5009.1   0.154       0  5516.4    0.22       0
Bank Sta=4990.60,5009.10
Exp/Cntr=0.3,0.1

Type RM Length L Ch R = 1 ,136882.8,546.1,546.1,546.1
BEGIN DESCRIPTION:
Cross Section Moccasin Creek 79.0
END DESCRIPTION:
#Sta/Elev= 30
  4511.8   291.1  4621.8   282.3  4651.8   278.8  4681.8   273.8  4691.8     273
  4841.8   272.8  4851.8   273.8  4871.8   273.1  4931.8   273.6  4981.8   273.3
  4990.6  271.55  4992.7   270.6  4996.6  270.18  4999.1  268.63  5002.5  268.13
  5007.2  269.43  5007.4  270.43  5009.1  271.67  5018.4   271.1  5038.4   272.5
  5048.4   271.5  5148.4   273.4  5168.4     272  5239.8  272.77  5288.4   271.8
  5338.4   273.5  5388.4   273.7  5448.4   277.2  5498.4   281.3  5689.5     289
#Mann= 5 , 1 , 0
 4511.80    0.22       0  4511.8   0.154       0  4990.6   0.054       0
  5009.1   0.154       0  5239.8      10       0
Bank Sta=4990.60,5009.10
Exp/Cntr=0.3,0.1

Type RM Length L Ch R = 1 ,136336.7,408.6,408.6,408.6
BEGIN DESCRIPTION:
Cross Section Moccasin Creek 78.0
END DESCRIPTION:
#Sta/Elev= 30
  4634.1   288.8  4654.1   288.7  4704.1   284.7  4784.1   272.6  4834.1   273.7
  4854.1   273.2  4894.1   273.9  4990.6  271.19  4996.6  269.82  4999.1  268.27
  5002.5  267.77  5007.2  269.07  5007.4  270.07  5009.1  271.31  5043.6   273.3
  5083.6   272.7  5113.6   273.5  5133.6   272.9  5163.6   273.7  5183.6   273.3
  5219.1  275.95  5263.6   272.6  5293.6   274.6  5313.6   272.7  5406.1   273.7
  5496.1   277.7  5586.1   280.2  5596.1   279.9  5716.1   284.9  5799.7   286.8
#Mann= 5 , 1 , 0
 4634.10    0.22       0  4634.1   0.154       0  4990.6   0.054       0
  5009.1   0.154       0  5219.1      10       0
Bank Sta=4990.60,5009.10
Exp/Cntr=0.3,0.1

Type RM Length L Ch R = 1 ,135928.1,603.9,603.9,603.9
BEGIN DESCRIPTION:
Cross Section Moccasin Creek XS165
END DESCRIPTION:
#Sta/Elev= 30
  4688.2   286.7  4718.2   284.3  4728.2   284.3  4778.2   280.2  4858.2   275.5
  4868.2   275.2  4878.2   274.3  4940.9  272.38  4967.1  270.02  4990.6  268.73
  4992.7  267.78  4996.6  267.36  4999.1  265.81  5002.5  265.31  5007.2  266.61
  5007.4  267.61  5009.1  268.85  5113.1   268.5  5233.1   270.7  5263.1   271.5
  5303.1     273  5313.1   274.2  5363.1   276.5  5383.1   276.7  5443.1   278.8
  5463.1   281.1  5493.1   282.5  5503.1   282.7  5513.1   282.4  5566.8   284.7
#Mann= 5 , 1 , 0
 4688.20    0.22       0  4688.2   0.154       0  4990.6   0.054       0
  5009.1   0.154       0  5566.8    0.22       0
Bank Sta=4990.60,5009.10
Exp/Cntr=0.3,0.1

Type RM Length L Ch R = 1 ,135324.2,503.8,503.8,503.8
BEGIN DESCRIPTION:
Cross Section Moccasin Creek 77.0
END DESCRIPTION:
#Sta/Elev= 30
  4625.2   285.6  4650.8  284.06  4665.2   284.1  4705.2   281.7  4715.2     282
  4745.2   278.3  4875.2   269.7  4925.2   268.2  4965.2   268.6 4989.66  266.33
 4996.26  264.96 4999.01  263.41 5002.75  262.91 5007.92  264.21 5008.14  265.21
 5010.01  266.45  5034.2   267.8  5054.2     268  5094.2   266.4  5134.2   268.2
  5154.2   267.5  5194.2   268.3  5234.2   267.8  5244.2     267  5304.2   266.6
  5354.2     269  5414.2   274.2  5434.2   275.1  5484.2     280  5540.8   283.9
#Mann= 6 , 1 , 0
 4625.20    0.22       0  4625.2   0.066       0  4650.8   0.154       0
 4989.66   0.054       0 5010.01   0.154       0  5540.8    0.22       0
Bank Sta=4989.66,5010.01
Exp/Cntr=0.3,0.1