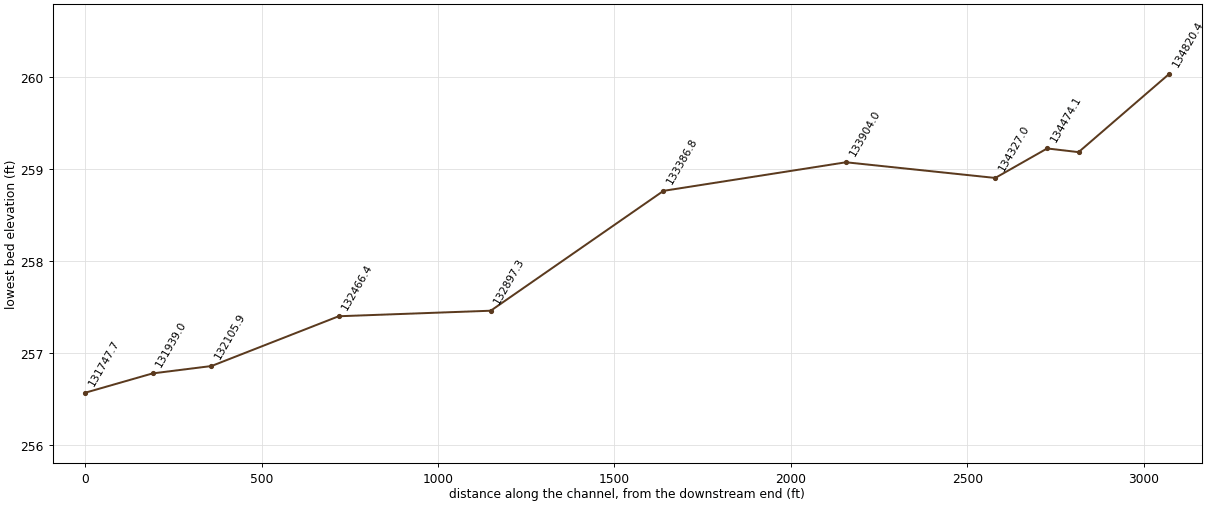
HEC-RAS study Moccasin_Creek_FINAL.prj: Moccasin Creek - Detail Study

--- Moccasin_Creek_FINAL.g01 (geometry) --- (continued)

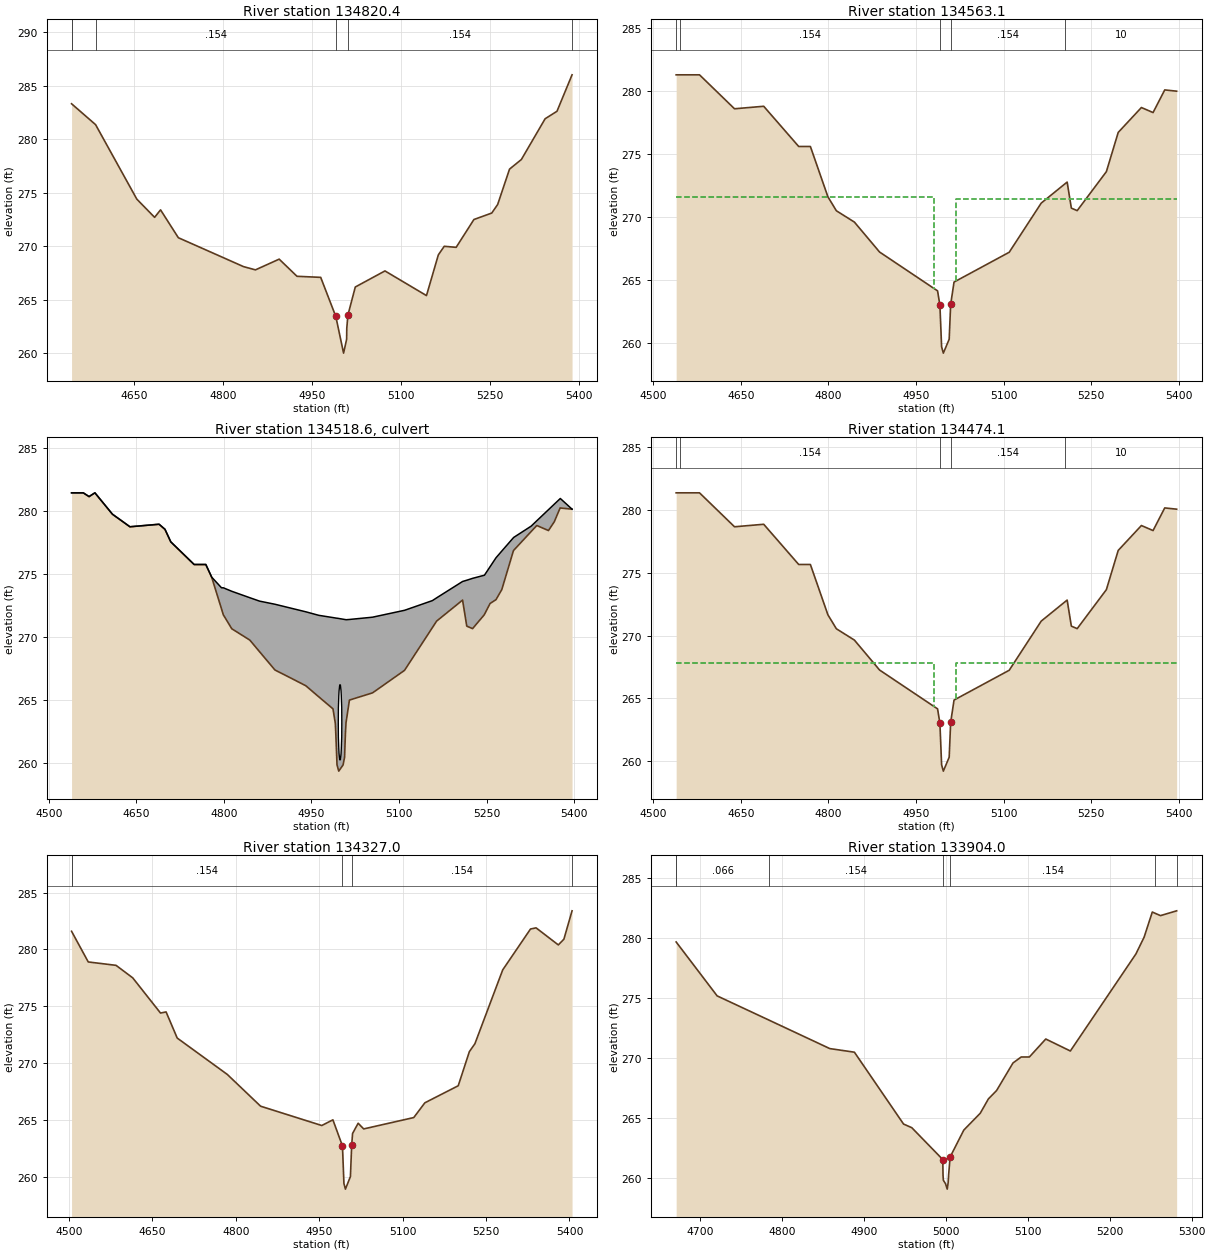
Type RM Length L Ch R = 1 ,134820.4,257.3,257.3,257.3
BEGIN DESCRIPTION:
Cross Section Moccasin Creek 76.0
END DESCRIPTION:
#Sta/Elev= 30
  4544.2   283.3  4584.7  281.35  4654.2   274.4  4684.2   272.7  4694.2   273.4
  4724.2   270.8  4834.2   268.1  4854.2   267.8  4894.2   268.8  4924.2   267.2
  4964.2   267.1 4989.66  263.45 5002.75  260.03 5007.92  261.33 5008.14  262.33
 5010.01  263.57  5022.5   266.2  5072.5   267.7  5142.5   265.4  5162.5   269.2
  5172.5     270  5192.5   269.9  5222.5   272.5  5252.5   273.1  5262.5   273.9
  5282.5   277.2  5302.5   278.1  5342.5   281.9  5362.5   282.6  5387.9     286
#Mann= 6 , 1 , 0
 4544.20    0.22       0  4544.2   0.066       0  4584.7   0.154       0
 4989.66   0.054       0 5010.01   0.154       0  5387.9    0.22       0
Bank Sta=4989.66,5010.01
Exp/Cntr=0.5,0.3

Type RM Length L Ch R = 1 ,134563.1,89,89,89
BEGIN DESCRIPTION:
Upstream Section of Bridge/Culvert/Weir
END DESCRIPTION:
#Sta/Elev= 30
    4539  281.31  4545.9  281.31    4579  281.31    4639  278.61    4689  278.81
    4749  275.61    4769  275.61    4799  271.61  4813.5   270.5  4844.4   269.6
  4887.5  267.22  4986.9  264.13  4990.9  262.98  4993.8  259.68  4996.8  259.18
  5006.8  260.29  5009.3  263.05  5015.1  264.83  5109.6   267.2  5164.5  271.11
  5205.9  272.67  5208.9  272.78  5216.1  270.71  5226.1  270.51  5276.1  273.61
  5296.4  276.73  5336.1  278.71  5356.1  278.31  5376.1  280.11  5396.5  280.01
#Mann= 5 , 1 , 0
 4539.00    0.22       0  4545.9   0.154       0  4990.9   0.054       0
  5009.3   0.154       0  5205.9      10       0
#XS Ineff= 2 , 0
       0    4981   271.6    5019       0   271.4
Bank Sta=4990.90,5009.30
Exp/Cntr=0.5,0.3

Type RM Length L Ch R = 2 ,134518.6,,,
BEGIN DESCRIPTION:
Furney Pearce Rd
Structure ID: WK_MCCR8
END DESCRIPTION:
Bridge Culvert--1,0,-1,-1, 0
Deck Dist Width WeirC Skew NumUp NumDn MinLoCord MaxHiCord MaxSubmerge Is_Ogee
10,69,2.8,, 48, 48,,,0.95,0,1,1,,
    4539    4559    4569    4579    4609    4639    4689    4699    4709    4749
    4769    4779  4795.9    4799  4813.5  4844.4    4861  4887.5  4940.3  4962.5
  4986.9  4990.9  4991.8  4993.8  4996.8  5004.2  5006.8  5008.2  5009.3  5015.1
  5054.5  5109.6  5157.2  5164.5  5208.9  5216.1  5226.1  5246.4  5256.1  5266.1
  5276.1  5296.4  5326.4  5336.1  5356.1  5366.1  5376.4  5396.5
  281.45  281.45  281.15  281.45  279.75  278.75  278.95  278.55  277.55  275.75
  275.75  274.75   273.9   273.9  273.62  273.11  272.84  272.59  271.99  271.71
  271.53   271.5  271.49  271.48  271.46   271.4  271.38  271.37  271.36  271.38
  271.56  272.11  272.88   273.1   274.4   274.5  274.65   274.9  275.58  276.28
  276.82   277.9   278.8  279.23  280.11  280.55     281  280.15
  281.45  281.45  281.15  281.45  279.75  278.75  278.95  278.55  277.55  275.75
  275.75  274.75  272.22  271.75  270.64  269.74  268.82  267.36  266.11  265.23
  264.27  263.12  262.22  259.82  259.32  259.81  260.43  262.31  263.19  264.97
  265.54  267.34  270.73  271.25  272.92  270.85  270.65  271.78  272.65  272.95
  273.75  276.87  278.37  278.85  278.45  279.15  280.25  280.15
    4539    4559    4569    4579    4609    4639    4689    4699    4709    4749
    4769    4779  4795.9    4799  4813.5  4844.4    4861  4887.5  4940.3  4962.5
  4986.9  4990.9  4991.8  4993.8  4996.8  5004.2  5006.8  5008.2  5009.3  5015.1
  5054.5  5109.6  5157.2  5164.5  5208.9  5216.1  5226.1  5246.4  5256.1  5266.1
  5276.1  5296.4  5326.4  5336.1  5356.1  5366.1  5376.4  5396.5
   281.4  281.41  281.11  281.41  279.71  278.71  278.91  278.51  277.51  275.71
  275.71  274.71   273.9   273.9  273.62  273.11  272.84  272.59  271.99  271.71
  271.53   271.5  271.49  271.48  271.46   271.4  271.38  271.37  271.36  271.38
  271.56  272.11  272.88   273.1   274.4   274.5  274.65   274.9  275.58  276.28
  276.82   277.9   278.8  279.23  280.11  280.55     281   280.1
  281.35  281.35  281.05  281.35  279.65  278.65  278.85  278.45  277.45  275.65
  275.65  274.65  272.12  271.65  270.54  269.64  268.72  267.26  266.01  265.13
  264.17  263.02  262.12  259.72  259.22  259.71  260.33  262.21  263.09  264.87
  265.44  267.24  270.63  271.15  272.82  270.75  270.55  271.68  272.55  272.85
  273.65  276.77  278.27  278.75  278.35  279.05  280.15  280.05
BR Coef= 1 , 0 , 0 ,1.25, 0 ,,,0.8,-1,2,0,
Wspro=,,,, 1 ,,,, 0 ,,,, 0 ,,,,-1 ,-1 ,-1 , 0 , 0 , 0 , 0 , 0
Culvert=1,6.0,,69.0,0.024,0.5,1.0,2,1,260.20,4999.00,260.10,4999.00,Culvert #1  ,0,10
BC Design=,, 0 ,, 0 ,,,,,,
BR U #Sta/Elev= 70
    4539  281.45  4545.9  281.45    4559  281.45  4565.9  281.24    4569  281.15
    4579  281.45    4609  279.75  4625.9  279.19    4639  278.75  4675.9   278.9
  4685.9  278.94    4689  278.95  4695.9  278.67    4699  278.55  4705.9  277.86
    4709  277.55    4749  275.75    4769  275.75    4779  274.75  4795.9  272.22
    4799  271.75  4799.4  271.72  4812.6  270.71  4813.5  270.64  4844.4  269.74
    4861  268.82  4887.5  267.36  4912.6  266.77  4940.3  266.11  4962.5  265.23
  4986.9  264.27  4990.9  263.12  4991.8  262.22  4993.8  259.82  4996.8  259.32
  5004.2  259.81  5006.8  260.43  5008.2  262.31  5009.3  263.19  5009.9  263.37
  5015.1  264.97  5054.5  265.54  5058.3  265.66  5107.9  267.28  5109.6  267.34
  5157.2  270.73  5164.5  271.25  5205.8   272.8  5205.9  272.81  5208.9  272.92
  5216.1  270.85  5226.1  270.65  5236.4  271.22  5246.1  271.75  5246.4  271.78
  5256.1  272.65  5266.1  272.95  5266.4  272.97  5276.1  273.75  5296.1  276.85
  5296.4  276.87  5326.4  278.37  5336.1  278.85  5356.1  278.45  5366.1  279.15
  5376.1  280.25  5376.4  280.25  5377.2  280.24  5396.1  280.15  5396.5  280.15
BR U #Mann= 5
 4539.00    0.22  4545.9   0.154  4990.9   0.054  5009.3   0.154  5205.9      10
BR U Banks=4990.90,5009.30
BR D #Sta/Elev= 70
    4539  281.35  4545.9  281.35    4559  281.35  4565.9  281.14    4569  281.05
    4579  281.35    4609  279.65  4625.9  279.09    4639  278.65  4675.9   278.8
  4685.9  278.84    4689  278.85  4695.9  278.57    4699  278.45  4705.9  277.76
    4709  277.45    4749  275.65    4769  275.65    4779  274.65  4795.9  272.12
    4799  271.65  4799.4  271.62  4812.6  270.61  4813.5  270.54  4844.4  269.64
    4861  268.72  4887.5  267.26  4912.6  266.67  4940.3  266.01  4962.5  265.13
  4986.9  264.17  4990.9  263.02  4991.8  262.12  4993.8  259.72  4996.8  259.22
  5004.2  259.71  5006.8  260.33  5008.2  262.21  5009.3  263.09  5009.9  263.27
  5015.1  264.87  5054.5  265.44  5058.3  265.56  5107.9  267.18  5109.6  267.24
  5157.2  270.63  5164.5  271.15  5205.8   272.7  5205.9  272.71  5208.9  272.82
  5216.1  270.75  5226.1  270.55  5236.4  271.12  5246.1  271.65  5246.4  271.68
  5256.1  272.55  5266.1  272.85  5266.4  272.87  5276.1  273.65  5296.1  276.75
  5296.4  276.77  5326.4  278.27  5336.1  278.75  5356.1  278.35  5366.1  279.05
  5376.1  280.15  5376.4  280.15  5377.2  280.14  5396.1  280.05  5396.5  280.05
BR D #Mann= 5
 4539.00    0.22  4545.9   0.154  4990.9   0.054  5009.3   0.154  5205.9      10
BR D Banks=4990.90,5009.30

Type RM Length L Ch R = 1 ,134474.1,147.1,147.1,147.1
BEGIN DESCRIPTION:
Downstream Section of Bridge/Culvert/Weir
END DESCRIPTION:
#Sta/Elev= 30
    4539  281.35  4545.9  281.35    4579  281.35    4639  278.65    4689  278.85
    4749  275.65    4769  275.65    4799  271.65  4813.5  270.54  4844.4  269.64
  4887.5  267.26  4986.9  264.17  4990.9  263.02  4993.8  259.72  4996.8  259.22
  5006.8  260.33  5009.3  263.09  5015.1  264.87  5109.6  267.24  5164.5  271.15
  5205.9  272.71  5208.9  272.82  5216.1  270.75  5226.1  270.55  5276.1  273.65
  5296.4  276.77  5336.1  278.75  5356.1  278.35  5376.1  280.15  5396.5  280.05
#Mann= 5 , 1 , 0
 4539.00    0.22       0  4545.9   0.154       0  4990.9   0.054       0
  5009.3   0.154       0  5205.9      10       0
#XS Ineff= 2 , 0
       0    4981   267.8    5019       0   267.8
Bank Sta=4990.90,5009.30
Exp/Cntr=0.5,0.3

Type RM Length L Ch R = 1 ,134327.0,423,423,423
BEGIN DESCRIPTION:
Cross Section Moccasin Creek 75.0
END DESCRIPTION:
#Sta/Elev= 30
  4504.6   281.6  4534.6   278.9  4584.6   278.6  4614.6   277.5  4664.6   274.4
  4674.6   274.5  4694.6   272.2  4784.6     269  4844.6   266.2  4954.6   264.5
  4974.6     265 4991.81   262.7 4994.42   259.4 4997.12   258.9 5006.12  260.01
 5008.37  262.77    5010   263.8    5020   264.7    5030   264.2    5120   265.2
    5140   266.5    5200     268    5220     271    5230   271.7    5280   278.2
    5330   281.8    5340   281.9    5380   280.4    5390   280.9  5404.7   283.4
#Mann= 5 , 1 , 0
 4504.60    0.22       0  4504.6   0.154       0 4991.81   0.054       0
 5008.37   0.154       0  5404.7    0.22       0
Bank Sta=4991.81,5008.37
Exp/Cntr=0.3,0.1

Type RM Length L Ch R = 1 ,133904.0,517.2,517.2,517.2
BEGIN DESCRIPTION:
Cross Section Moccasin Creek 74.0
END DESCRIPTION:
#Sta/Elev= 30
    4671   279.7    4721   275.2  4784.5  273.17  4858.5   270.8  4888.5   270.5
  4948.5   264.5  4958.5   264.2 4996.32  261.54 4996.64  260.24 4997.04  259.81
  4999.6  259.53 5001.76  259.07 5002.88  259.61 5003.44  260.24 5005.28  261.75
    5022     264    5042   265.4    5052   266.6    5062   267.3    5082   269.6
    5092   270.1    5102   270.1    5122   271.6    5152   270.6    5232   278.7
    5242   280.1    5252   282.2  5255.6  282.09    5262   281.9  5281.7   282.3
#Mann= 7 , 1 , 0
 4671.00    0.22       0    4671   0.066       0  4784.5   0.154       0
 4996.32   0.054       0 5005.28   0.154       0  5255.6   0.066       0
  5281.7    0.22       0
Bank Sta=4996.32,5005.28
Exp/Cntr=0.3,0.1

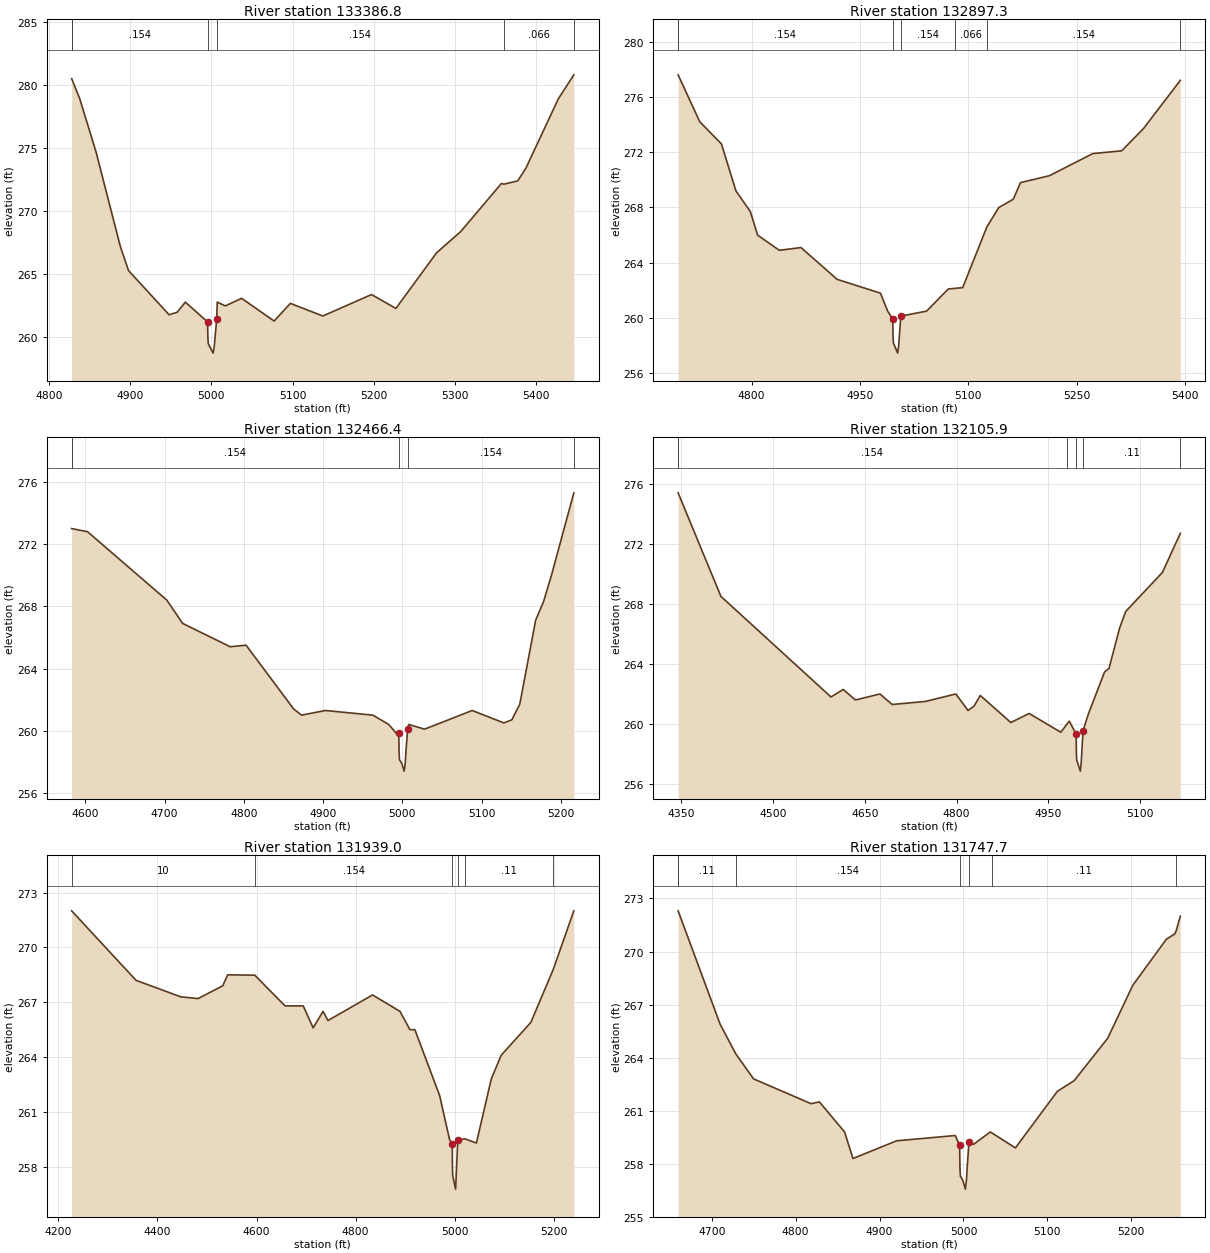
Type RM Length L Ch R = 1 ,133386.8,489.5,489.5,489.5
BEGIN DESCRIPTION:
Cross Section Moccasin Creek 73.0
END DESCRIPTION:
#Sta/Elev= 30
    4828   280.5    4838   278.9    4858   274.7    4888   267.2    4898   265.3
    4948   261.8    4958     262    4968   262.8  4995.4  261.23  4995.8  259.93
  4996.3   259.5  5002.2  258.76  5003.6   259.3  5006.6  261.44  5007.3   262.8
  5017.3   262.5  5037.3   263.1  5077.3   261.3  5097.3   262.7  5137.3   261.7
  5197.3   263.4  5227.3   262.3  5277.3   266.7  5307.3   268.4  5357.3   272.2
  5360.3  272.14  5377.3   272.4  5387.3   273.4  5427.3   278.9  5446.4   280.8
#Mann= 6 , 1 , 0
 4828.00    0.22       0    4828   0.154       0  4995.4   0.054       0
  5006.6   0.154       0  5360.3   0.066       0  5446.4    0.22       0
Bank Sta=4995.40,5006.60
Exp/Cntr=0.3,0.1

Type RM Length L Ch R = 1 ,132897.3,430.9,430.9,430.9
BEGIN DESCRIPTION:
Cross Section Moccasin Creek 72.5
END DESCRIPTION:
#Sta/Elev= 30
  4698.4   277.6  4728.4   274.2  4758.4   272.6  4778.4   269.2  4798.4   267.7
  4808.4     266  4838.4   264.9  4868.4   265.1  4918.4   262.8  4978.4   261.8
  4988.4   260.5  4995.4  259.93  4995.8  258.63  4996.3   258.2  5002.2  257.46
  5003.6     258  5006.6  260.14  5042.2   260.5  5072.2   262.1  5081.7  262.15
  5092.2   262.2  5125.6  266.59  5142.2     268  5162.2   268.6  5172.2   269.8
  5212.2   270.3  5272.2   271.9  5312.2   272.1  5342.2   273.7  5393.3   277.2
#Mann= 7 , 1 , 0
 4698.40    0.22       0  4698.4   0.154       0  4995.4   0.054       0
  5006.6   0.154       0  5081.7   0.066       0  5125.6   0.154       0
  5393.3    0.22       0
Bank Sta=4995.40,5006.60
Exp/Cntr=0.3,0.1

Type RM Length L Ch R = 1 ,132466.4,360.5,360.5,360.5
BEGIN DESCRIPTION:
Cross Section Moccasin Creek 72.0
END DESCRIPTION:
#Sta/Elev= 30
  4582.8     273  4602.8   272.8  4702.8   268.4  4722.8   266.9  4782.8   265.4
  4802.8   265.5  4862.8   261.4  4872.8     261  4902.8   261.3  4962.8     261
  4982.8   260.4  4992.8   259.8  4995.4  259.87  4995.8  258.57  4996.3  258.14
  4999.5  257.86  5002.2   257.4  5003.6  257.94  5004.3  258.57  5006.6  260.08
    5008   260.4    5028   260.1    5088   261.3    5128   260.5    5138   260.7
    5148   261.7    5168   267.1    5178   268.3    5188     270  5216.2   275.3
#Mann= 5 , 1 , 0
 4582.80    0.22       0  4582.8   0.154       0  4995.4   0.054       0
  5006.6   0.154       0  5216.2    0.22       0
Bank Sta=4995.40,5006.60
Exp/Cntr=0.3,0.1

Type RM Length L Ch R = 1 ,132105.9,166.9,166.9,166.9
BEGIN DESCRIPTION:
Cross Section Moccasin Creek XS166
END DESCRIPTION:
#Sta/Elev= 30
  4344.5   275.4  4414.5   268.5  4594.5   261.8  4614.5   262.3  4634.5   261.6
  4674.5     262  4694.5   261.3  4748.6   261.5  4798.6     262  4818.6   260.9
  4828.6   261.2  4838.6   261.9  4888.6   260.1  4918.6   260.7  4970.2  259.45
  4979.6  259.95  4984.1  260.19  4995.4  259.33  4995.8  258.03  4996.3   257.6
  5002.2  256.86  5003.6   257.4  5006.6  259.54  5015.2  260.65  5041.9  263.47
  5049.1   263.7  5066.5   266.4  5076.5   267.5  5136.5   270.1  5165.7   272.7
#Mann= 6 , 1 , 0
 4344.50    0.22       0  4344.5   0.154       0  4979.6    0.11       0
  4995.4   0.054       0  5006.6    0.11       0  5165.7    0.22       0
Bank Sta=4995.40,5006.60
Exp/Cntr=0.3,0.1

Type RM Length L Ch R = 1 ,131939.0,191.3,191.3,191.3
BEGIN DESCRIPTION:
Cross Section Moccasin Creek 71.3
END DESCRIPTION:
#Sta/Elev= 30
  4226.6     272  4356.6   268.2  4446.6   267.3  4481.8   267.2  4531.8   267.9
  4541.8   268.5  4596.6  268.48  4657.6   266.8  4694.4   266.8  4714.4   265.6
  4734.4   266.5  4744.4     266  4834.4   267.4  4889.9   266.5  4909.9   265.5
  4919.9   265.5  4969.9   261.9  4989.9   259.5  4995.4  259.25  4995.8  257.95
  4996.3  257.52  5002.2  256.78  5006.6  259.46    5021  259.53  5044.2   259.3
  5074.2   262.8  5094.2   264.1  5154.2   265.9  5199.5   268.8    5241     272
#Mann= 6 , 1 , 0
 4226.60      10       0  4596.6   0.154       0  4995.4   0.054       0
  5006.6   0.154       0    5021    0.11       0  5199.5    0.22       0
Bank Sta=4995.40,5006.60
Exp/Cntr=0.3,0.1

Type RM Length L Ch R = 1 ,131747.7,203.8,203.8,203.8
BEGIN DESCRIPTION:
Cross Section Moccasin Creek 71.0
END DESCRIPTION:
#Sta/Elev= 30
  4659.9   272.3  4709.9   265.9  4728.7  264.21  4749.9   262.8  4818.3   261.4
  4828.3   261.5  4858.3   259.8  4868.3   258.3  4920.2   259.3  4990.2   259.6
  4995.4  259.04  4995.8  257.74  4996.3  257.31  4999.5  257.03  5002.2  256.57
  5003.6  257.11  5004.3  257.74  5006.6  259.25  5011.9   259.1  5031.9   259.8
  5033.7  259.75  5061.9   258.9  5111.9   262.1  5131.9   262.7  5171.9   265.1
  5201.9   268.1  5241.9   270.7  5251.9     271  5253.7   271.2  5258.4     272
#Mann= 7 , 1 , 0
 4659.90    0.22       0  4659.9    0.11       0  4728.7   0.154       0
  4995.4   0.054       0  5006.6   0.154       0  5033.7    0.11       0
  5253.7   0.154       0
Bank Sta=4995.40,5006.60
Exp/Cntr=0.3,0.1