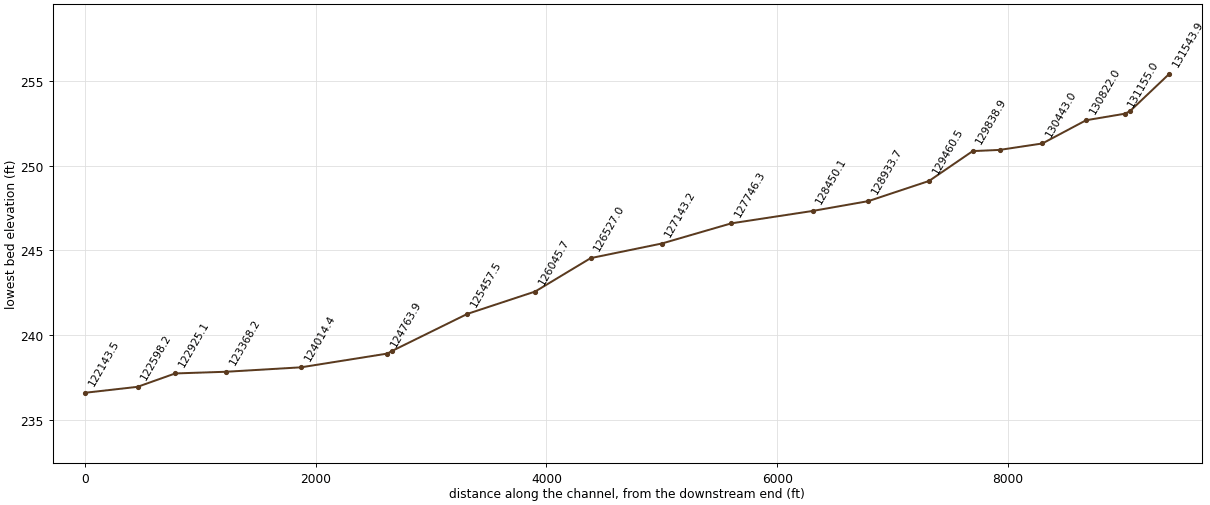
HEC-RAS study Moccasin_Creek_FINAL.prj: Moccasin Creek - Detail Study

--- Moccasin_Creek_FINAL.g01 (geometry) --- (continued)

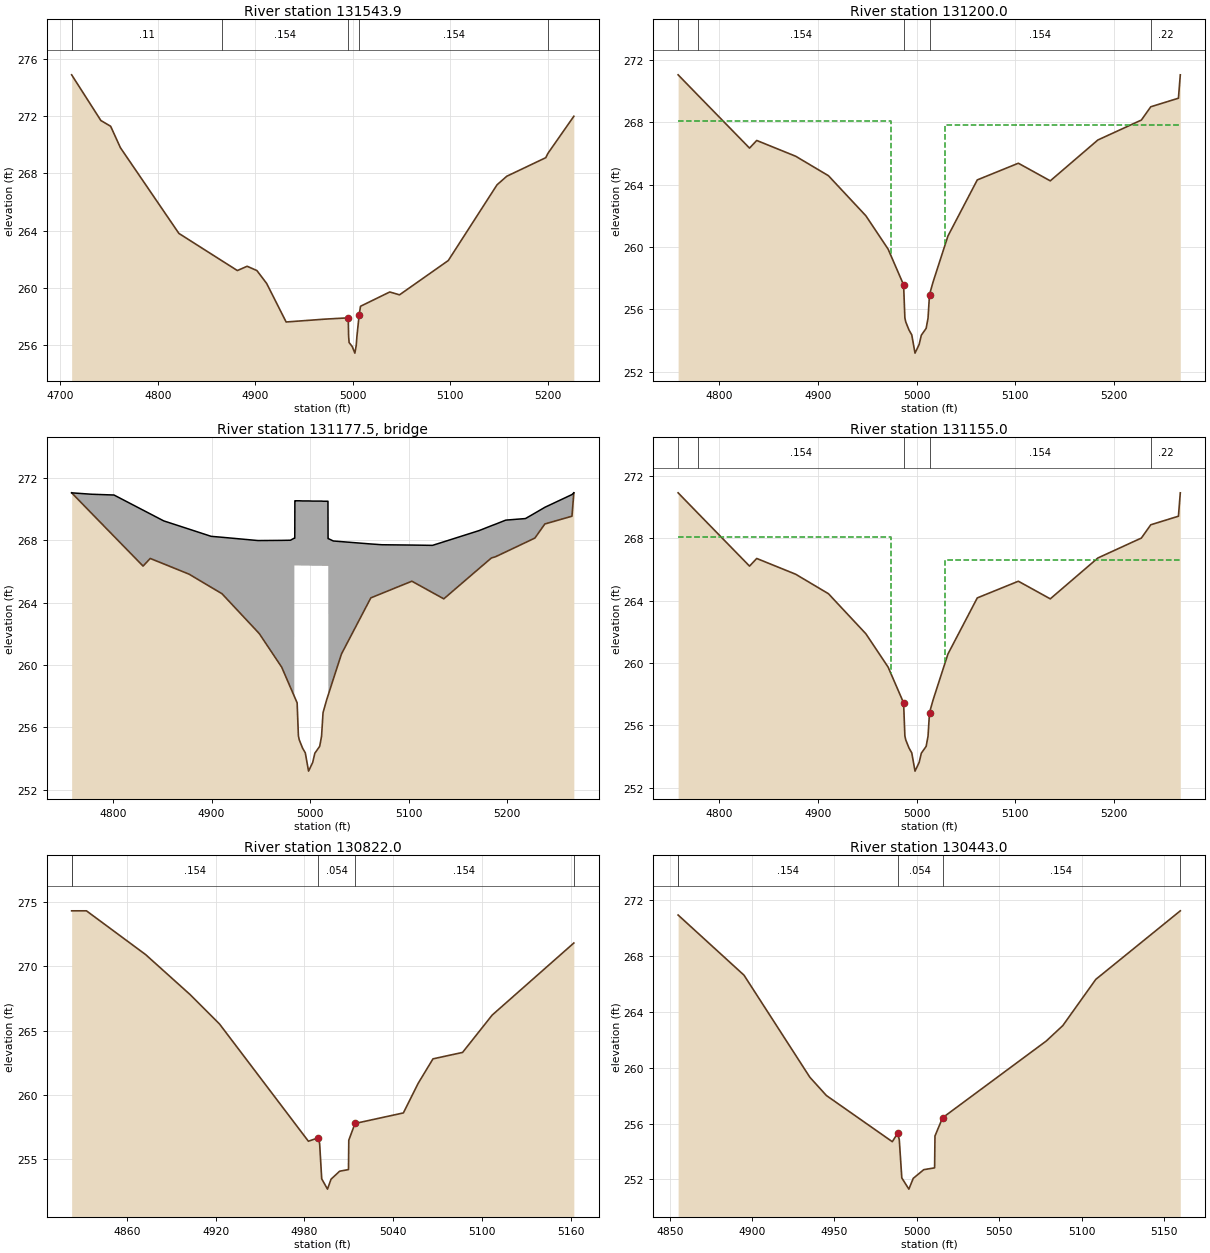
Type RM Length L Ch R = 1 ,131543.9,343.9,343.9,343.9
BEGIN DESCRIPTION:
Cross Section Moccasin Creek 70.0
END DESCRIPTION:
#Sta/Elev= 29
  4711.7   274.9  4741.7   271.7  4751.7   271.3  4761.7   269.8  4821.7   263.8
  4866.2  261.87  4881.7   261.2  4891.7   261.5  4901.7   261.2  4911.7   260.3
  4931.7   257.6  4971.7   257.8  4995.4  257.89  4995.8  256.59  4996.3  256.16
  4999.5  255.88  5002.2  255.42  5003.6  255.96  5004.3  256.59  5006.6   258.1
    5008   258.7    5038   259.7    5048   259.5    5098   261.9    5148   267.2
    5158   267.8    5198   269.1  5200.2   269.4  5226.8     272
#Mann= 6 , 1 , 0
 4711.70    0.22       0  4711.7    0.11       0  4866.2   0.154       0
  4995.4   0.054       0  5006.6   0.154       0  5200.2   0.154       0
Bank Sta=4995.40,5006.60
Exp/Cntr=0.5,0.3

Type RM Length L Ch R = 1 ,131200.0,45,45,45
BEGIN DESCRIPTION:
Upstream Section of Bridge/Culvert/Weir
END DESCRIPTION:
#Sta/Elev= 29
    4758  271.05    4778  269.75  4830.5  266.35  4837.8  266.84  4877.3  265.83
  4910.6  264.58  4948.6  262.01  4971.2  259.87  4986.9  257.58  4988.2  255.46
  4989.1   255.2  4992.4  254.68  4995.2  254.37  4998.5   253.2  5002.7  253.76
  5004.9  254.35  5009.8  254.79  5011.7  255.44  5013.2  256.95  5016.9  257.78
  5031.9  260.71  5061.7  264.31  5103.4  265.38  5135.8  264.25  5184.1  266.87
  5228.3  268.15  5237.8     269  5265.9  269.55  5267.8  271.05
#Mann= 5 , 1 , 0
 4758.00    0.22       0    4778   0.154       0  4986.9   0.054       0
  5013.2   0.154       0  5237.8    0.22       0
#XS Ineff= 2 , 0
       0    4974   268.1    5029       0   267.8
Bank Sta=4986.90,5013.20
Exp/Cntr=0.5,0.3

Type RM Length L Ch R = 3 ,131177.5,,,
BEGIN DESCRIPTION:
Pearces Rd
Structure ID: WK_MCCR7
END DESCRIPTION:
Bridge Culvert--1,0,-1,-1, 0
Deck Dist Width WeirC Skew NumUp NumDn MinLoCord MaxHiCord MaxSubmerge Is_Ogee
10,25,2.6,,56,56,,,0.95,0,1,1,,
    4758    4778    4801  4830.5  4837.8  4851.5  4877.3  4899.6  4910.6    4947
  4948.6  4971.2  4980.1  4983.9 4984.01  4984.1  4984.2 4984.49  4984.6 4984.71
  4986.9  4988.2  4989.1  4992.4  4995.2  4998.5  5002.7  5004.9  5009.8  5011.7
  5013.2  5016.9 5018.09  5018.2 5018.31  5018.4 5018.49  5018.6  5018.7  5023.7
  5031.9  5061.7  5072.9  5103.4  5124.3  5135.8  5171.7  5184.1  5188.3  5198.7
  5218.7  5228.3  5237.8  5238.3  5265.9  5267.8
  271.05  270.96  270.91  269.94   269.7  269.25  268.72  268.26   268.2  267.99
  267.99     268  268.01  268.14  268.14  268.14  268.14  268.14  270.54  270.54
  270.54  270.54  270.54  270.53  270.53  270.53  270.52  270.52  270.52  270.52
  270.51  270.51  270.51  270.51  268.11  268.11  268.11  268.11  268.11  267.96
  267.92  267.77  267.72   267.7  267.68  267.91  268.63  268.94  269.04   269.3
   269.4  269.75   270.1  270.12  270.94  271.05
  271.05  269.75  268.26  266.35  266.84  266.49  265.83  264.99  264.58  262.12
  262.01  259.87  258.57  258.02     258  266.39  266.39  266.39  266.39  266.39
  266.39  266.39  266.39  266.38  266.38  266.38  266.37  266.37  266.37  266.37
  266.36  266.36  266.36  266.36  266.36  266.36  266.36  258.11  258.13  259.11
  260.71  264.31   264.6  265.38  264.65  264.25   266.2  266.87  266.95  267.26
  267.86  268.15     269  269.05  269.55  271.05
    4758    4778    4801  4830.5  4837.8  4851.5  4877.3  4899.6  4910.6    4947
  4948.6  4971.2  4980.1  4983.9 4984.01  4984.1  4984.2 4984.49  4984.6 4984.71
  4986.9  4988.2  4989.1  4992.4  4995.2  4998.5  5002.7  5004.9  5009.8  5011.7
  5013.2  5016.9 5018.09  5018.2 5018.31  5018.4 5018.49  5018.6  5018.7  5023.7
  5031.9  5061.7  5072.9  5103.4  5124.3  5135.8  5171.7  5184.1  5188.3  5198.7
  5218.7  5228.3  5237.8  5238.3  5265.9  5267.8
     271  270.96  270.91  269.94   269.7  269.25  268.72  268.26   268.2  267.99
  267.99     268  268.01  268.14  268.14  268.14  268.14  268.14  270.54  270.54
  270.54  270.54  270.54  270.53  270.53  270.53  270.52  270.52  270.52  270.52
  270.51  270.51  270.51  270.51  268.11  268.11  268.11  268.11  268.11  267.96
  267.92  267.77  267.72   267.7  267.68  267.91  268.63  268.94  269.04   269.3
   269.4  269.75   270.1  270.12  270.94     271
  270.95  269.65  268.16  266.25  266.74  266.39  265.73  264.89  264.48  262.02
  261.91  259.77  258.47  257.92   257.9  266.29  266.29  266.29  266.29  266.29
  266.29  266.29  266.29  266.28  266.28  266.28  266.27  266.27  266.27  266.27
  266.26  266.26  266.26  266.26  266.26  266.26  266.26  258.01  258.03  259.01
  260.61  264.21   264.5  265.28  264.55  264.15   266.1  266.77  266.85  267.16
  267.76  268.05   268.9  268.95  269.45  270.95
BR Coef= 1 , 1 , 0 ,1.25, 0 ,,,0.8,0,2,0,
Wspro=,,,, 1 ,,,, 0 ,,,, 0 ,,,,-1 ,-1 ,-1 , 0 , 0 , 0 , 0 , 0
BC Design=,, 0 ,, 0 ,,,,,,
BR U #Sta/Elev= 56
    4758  271.05    4778  269.75    4801  268.26  4830.5  266.35  4837.8  266.84
  4851.5  266.49  4877.3  265.83  4899.6  264.99  4910.6  264.58    4947  262.12
  4948.6  262.01  4971.2  259.87  4980.1  258.57  4983.9  258.02 4984.01     258
  4984.1  257.99  4984.2  257.97 4984.49  257.93  4984.6  257.92 4984.71   257.9
  4986.9  257.58  4988.2  255.46  4989.1   255.2  4992.4  254.68  4995.2  254.37
  4998.5   253.2  5002.7  253.76  5004.9  254.35  5009.8  254.79  5011.7  255.44
  5013.2  256.95  5016.9  257.78 5018.09  258.01  5018.2  258.03 5018.31  258.06
  5018.4  258.07 5018.49  258.09  5018.6  258.11  5018.7  258.13  5023.7  259.11
  5031.9  260.71  5061.7  264.31  5072.9   264.6  5103.4  265.38  5124.3  264.65
  5135.8  264.25  5171.7   266.2  5184.1  266.87  5188.3  266.95  5198.7  267.26
  5218.7  267.86  5228.3  268.15  5237.8     269  5238.3  269.05  5265.9  269.55
  5267.8  271.05
BR U #Mann= 5
 4758.00    0.22    4778   0.154  4986.9   0.054  5013.2   0.154  5237.8    0.22
BR U Banks=4986.90,5013.20
BR D #Sta/Elev= 56
    4758  270.95    4778  269.65    4801  268.16  4830.5  266.25  4837.8  266.74
  4851.5  266.39  4877.3  265.73  4899.6  264.89  4910.6  264.48    4947  262.02
  4948.6  261.91  4971.2  259.77  4980.1  258.47  4983.9  257.92 4984.01   257.9
  4984.1  257.89  4984.2  257.87 4984.49  257.83  4984.6  257.82 4984.71   257.8
  4986.9  257.48  4988.2  255.36  4989.1   255.1  4992.4  254.58  4995.2  254.27
  4998.5   253.1  5002.7  253.66  5004.9  254.25  5009.8  254.69  5011.7  255.34
  5013.2  256.85  5016.9  257.68 5018.09  257.91  5018.2  257.93 5018.31  257.96
  5018.4  257.97 5018.49  257.99  5018.6  258.01  5018.7  258.03  5023.7  259.01
  5031.9  260.61  5061.7  264.21  5072.9   264.5  5103.4  265.28  5124.3  264.55
  5135.8  264.15  5171.7   266.1  5184.1  266.77  5188.3  266.85  5198.7  267.16
  5218.7  267.76  5228.3  268.05  5237.8   268.9  5238.3  268.95  5265.9  269.45
  5267.8  270.95
BR D #Mann= 5
 4758.00    0.22    4778   0.154  4986.9   0.054  5013.2   0.154  5237.8    0.22
BR D Banks=4986.90,5013.20

Type RM Length L Ch R = 1 ,131155.0,333,333,333
BEGIN DESCRIPTION:
Downstream Section of Bridge/Culvert/Weir
END DESCRIPTION:
#Sta/Elev= 29
    4758  270.91    4778  269.61  4830.5  266.21  4837.8   266.7  4877.3  265.69
  4910.6  264.44  4948.6  261.87  4971.2  259.73  4986.9  257.44  4988.2  255.32
  4989.1  255.06  4992.4  254.54  4995.2  254.23  4998.5  253.06  5002.7  253.62
  5004.9  254.21  5009.8  254.65  5011.7   255.3  5013.2  256.81  5016.9  257.64
  5031.9  260.57  5061.7  264.17  5103.4  265.24  5135.8  264.11  5184.1  266.73
  5228.3  268.01  5237.8  268.86  5265.9  269.41  5267.8  270.91
#Mann= 5 , 1 , 0
 4758.00    0.22       0    4778   0.154       0  4986.9   0.054       0
  5013.2   0.154       0  5237.8    0.22       0
#XS Ineff= 2 , 0
       0    4974   268.1    5029       0   266.6
Bank Sta=4986.90,5013.20
Exp/Cntr=0.5,0.3

Type RM Length L Ch R = 1 ,130822.0,379,379,379
BEGIN DESCRIPTION:
Cross Section Moccasin Creek 69.5
END DESCRIPTION:
#Sta/Elev= 21
  4822.7   274.3  4832.7   274.3  4872.7   270.9  4902.7   267.8  4922.7   265.5
  4982.7   256.4  4989.4  256.67  4990.3  256.22  4991.7  253.48  4995.6  252.68
    4998  253.45  5003.8  254.07  5009.8   254.2    5010  256.48  5014.2  257.78
  5046.9   258.6  5056.9   260.9  5066.9   262.8  5086.9   263.3  5106.9   266.2
  5162.1   271.8
#Mann= 5 , 1 , 0
 4822.70    0.22       0  4822.7   0.154       0  4989.4   0.054       0
  5014.2   0.154       0  5162.1    0.22       0
Bank Sta=4989.40,5014.20
Exp/Cntr=0.3,0.1

Type RM Length L Ch R = 1 ,130443.0,371.4,371.4,371.4
BEGIN DESCRIPTION:
Cross Section Moccasin Creek 69.0
END DESCRIPTION:
#Sta/Elev= 18
  4855.1   270.9  4895.1   266.6  4935.1   259.3  4945.1     258  4985.1   254.7
 4988.34   255.3 4989.33  254.85 4990.87  252.11 4995.16  251.31  4997.8  252.08
 5004.18   252.7 5010.78  252.83    5011  255.11 5015.62  256.41  5078.6   261.9
  5088.6     263  5108.6   266.3  5159.9   271.2
#Mann= 5 , 1 , 0
 4855.10    0.22       0  4855.1   0.154       0 4988.34   0.054       0
 5015.62   0.154       0  5159.9    0.22       0
Bank Sta=4988.34,5015.62
Exp/Cntr=0.3,0.1

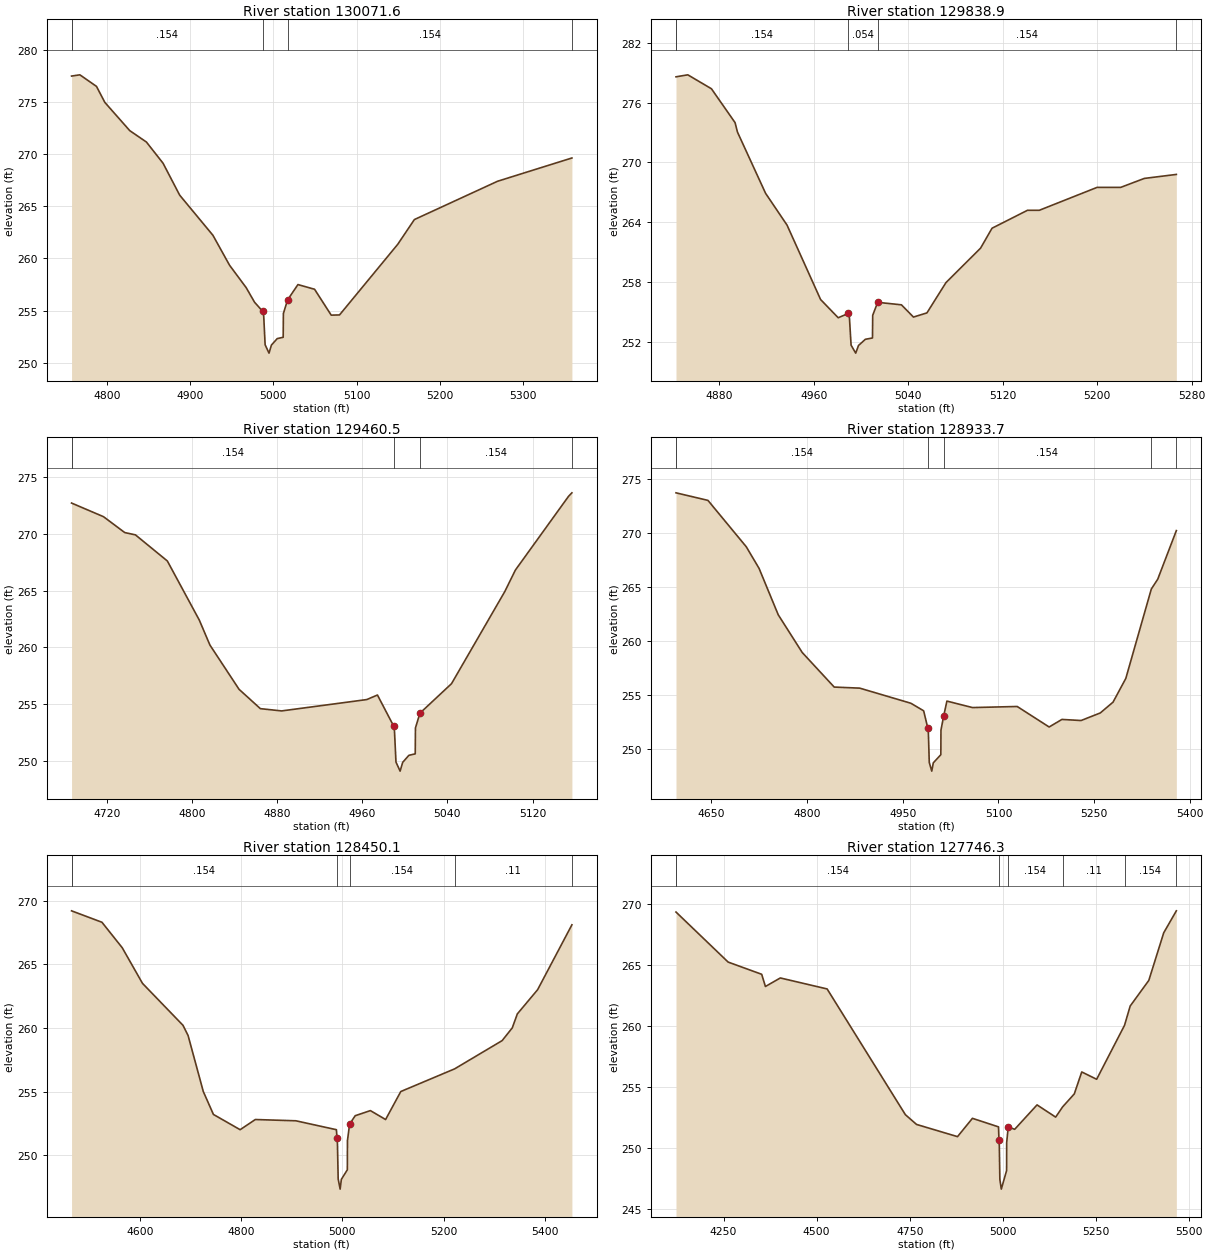
Type RM Length L Ch R = 1 ,130071.6,232.7,232.7,232.7
BEGIN DESCRIPTION:
Cross Section Moccasin Creek 68.0 (HWM location)
END DESCRIPTION:
#Sta/Elev= 29
  4757.3  277.48  4767.3   277.6  4787.3  276.49  4797.3  274.96  4827.3  272.25
  4847.3  271.16  4867.3  269.13  4887.3  266.07  4927.3  262.22  4947.3  259.35
  4967.3   257.2  4977.3  255.81 4987.28  254.92 4988.36  254.47 4990.04  251.73
 4994.72  250.93  4997.6   251.7 5004.56  252.32 5011.76  252.45    5012  254.73
 5017.04  256.03  5029.5   257.5  5049.5  257.05  5069.5  254.57  5079.5  254.59
  5149.5  261.36  5169.5  263.73  5269.5   267.4  5358.9  269.63
#Mann= 5 , 1 , 0
 4757.30    0.22       0  4757.3   0.154       0 4987.28   0.054       0
 5017.04   0.154       0  5358.9    0.22       0
Bank Sta=4987.28,5017.04
Exp/Cntr=0.3,0.1

Type RM Length L Ch R = 1 ,129838.9,378.4,378.4,378.4
BEGIN DESCRIPTION:
Cross Section Moccasin Creek XS260
END DESCRIPTION:
#Sta/Elev= 30
  4843.5   278.6  4853.5   278.8  4873.5   277.4  4893.5     274  4895.5  273.06
  4919.3  266.91  4937.5  263.71  4965.9  256.24  4980.8  254.41  4989.4  254.85
  4990.3   254.4  4991.7  251.66  4995.6  250.86    4998  251.63  5003.8  252.25
  5009.8  252.38    5010  254.66  5014.2  255.96  5034.3  255.71  5044.5  254.48
  5055.9   254.9    5072  257.94  5101.3   261.4    5111   263.4    5141   265.2
    5151   265.2  5199.9   267.5  5219.9   267.5  5239.9   268.4    5267   268.8
#Mann= 5 , 1 , 0
 4843.50    0.22       0  4843.5   0.154       0  4989.4   0.054       0
  5014.2   0.154       0    5267    0.22       0
Bank Sta=4989.40,5014.20
Exp/Cntr=0.3,0.1

Type RM Length L Ch R = 1 ,129460.5,526.8,526.8,526.8
BEGIN DESCRIPTION:
Cross Section Moccasin Creek 67.0
END DESCRIPTION:
#Sta/Elev= 26
  4686.9   272.7  4716.9   271.5  4736.9   270.1  4746.9   269.9  4776.9   267.6
  4806.9   262.4  4816.9   260.2  4844.3   256.3  4864.3   254.6  4884.3   254.4
  4964.3   255.4  4974.3   255.8  4989.4  253.09  4990.3  252.64  4991.7   249.9
  4995.6   249.1    4998  249.87  5003.8  250.49  5009.8  250.62    5010   252.9
  5014.2   254.2  5043.9   256.8  5093.9   264.9  5103.9   266.8  5153.9   273.3
    5157   273.6
#Mann= 5 , 1 , 0
 4686.90    0.22       0  4686.9   0.154       0  4989.4   0.054       0
  5014.2   0.154       0    5157    0.22       0
Bank Sta=4989.40,5014.20
Exp/Cntr=0.3,0.1

Type RM Length L Ch R = 1 ,128933.7,483.6,483.6,483.6
BEGIN DESCRIPTION:
Cross Section Moccasin Creek 66.0
END DESCRIPTION:
#Sta/Elev= 30
  4595.3   273.7  4645.3     273  4705.3   268.7  4725.3   266.7  4755.3   262.4
  4792.9   258.9  4842.9   255.7  4882.9   255.6  4962.9   254.2  4982.9   253.5
  4989.4   251.9  4990.3  251.45  4991.7  248.71  4995.6  247.91    4998  248.68
  5009.8  249.43    5010  251.71  5014.2  253.01  5019.3   254.4  5059.3   253.8
  5129.3   253.9  5179.3     252  5199.3   252.7  5229.3   252.6  5259.3   253.3
  5279.3   254.3  5299.3   256.5  5339.2  264.78  5349.3   265.7  5378.4   270.2
#Mann= 6 , 1 , 0
 4595.30    0.22       0  4595.3   0.154       0  4989.4   0.054       0
  5014.2   0.154       0  5339.2   0.066       0  5378.4    0.22       0
Bank Sta=4989.40,5014.20
Exp/Cntr=0.3,0.1

Type RM Length L Ch R = 1 ,128450.1,703.8,703.8,703.8
BEGIN DESCRIPTION:
Cross Section Moccasin Creek 65.0
END DESCRIPTION:
#Sta/Elev= 30
  4465.5   269.2  4525.5   268.3  4565.5   266.3  4605.5   263.5  4685.5   260.2
  4695.5   259.4  4725.5     255  4745.5   253.2  4798.2     252  4828.2   252.8
  4908.2   252.7  4988.2     252  4989.4  251.32  4990.3  250.87  4991.7  248.13
  4995.6  247.33    4998   248.1  5009.8  248.85    5010  251.13  5014.2  252.43
  5025.3   253.1  5055.3   253.5  5085.3   252.8  5115.3     255  5221.5  256.78
  5315.3     259  5335.3     260  5345.3   261.1  5385.3     263    5453   268.1
#Mann= 6 , 1 , 0
 4465.50    0.22       0  4465.5   0.154       0  4989.4   0.054       0
  5014.2   0.154       0  5221.5    0.11       0    5453    0.22       0
Bank Sta=4989.40,5014.20
Exp/Cntr=0.3,0.1

Type RM Length L Ch R = 1 ,127746.3,603.1,603.1,603.1
BEGIN DESCRIPTION:
Cross Section Moccasin Creek 64.0
END DESCRIPTION:
#Sta/Elev= 30
  4122.5   269.3  4262.5   265.2  4352.5   264.2  4362.5   263.2  4402.5   263.9
  4528.1     263  4738.1   252.7  4768.1   251.9  4878.1   250.9  4918.1   252.4
  4988.1   251.7  4989.4  250.59  4990.3  250.14  4991.7   247.4  4995.6   246.6
  5009.8  248.12    5010   250.4  5014.2   251.7  5031.5   251.5  5091.5   253.5
  5141.5   252.5  5160.2  253.34  5191.5   254.4  5211.5   256.2  5251.5   255.6
  5326.3  260.02  5341.5   261.6  5391.5   263.7  5431.5   267.6  5465.4   269.4
#Mann= 7 , 1 , 0
 4122.50    0.22       0  4122.5   0.154       0  4989.4   0.054       0
  5014.2   0.154       0  5160.2    0.11       0  5326.3   0.154       0
  5465.4      10       0
Bank Sta=4989.40,5014.20
Exp/Cntr=0.3,0.1

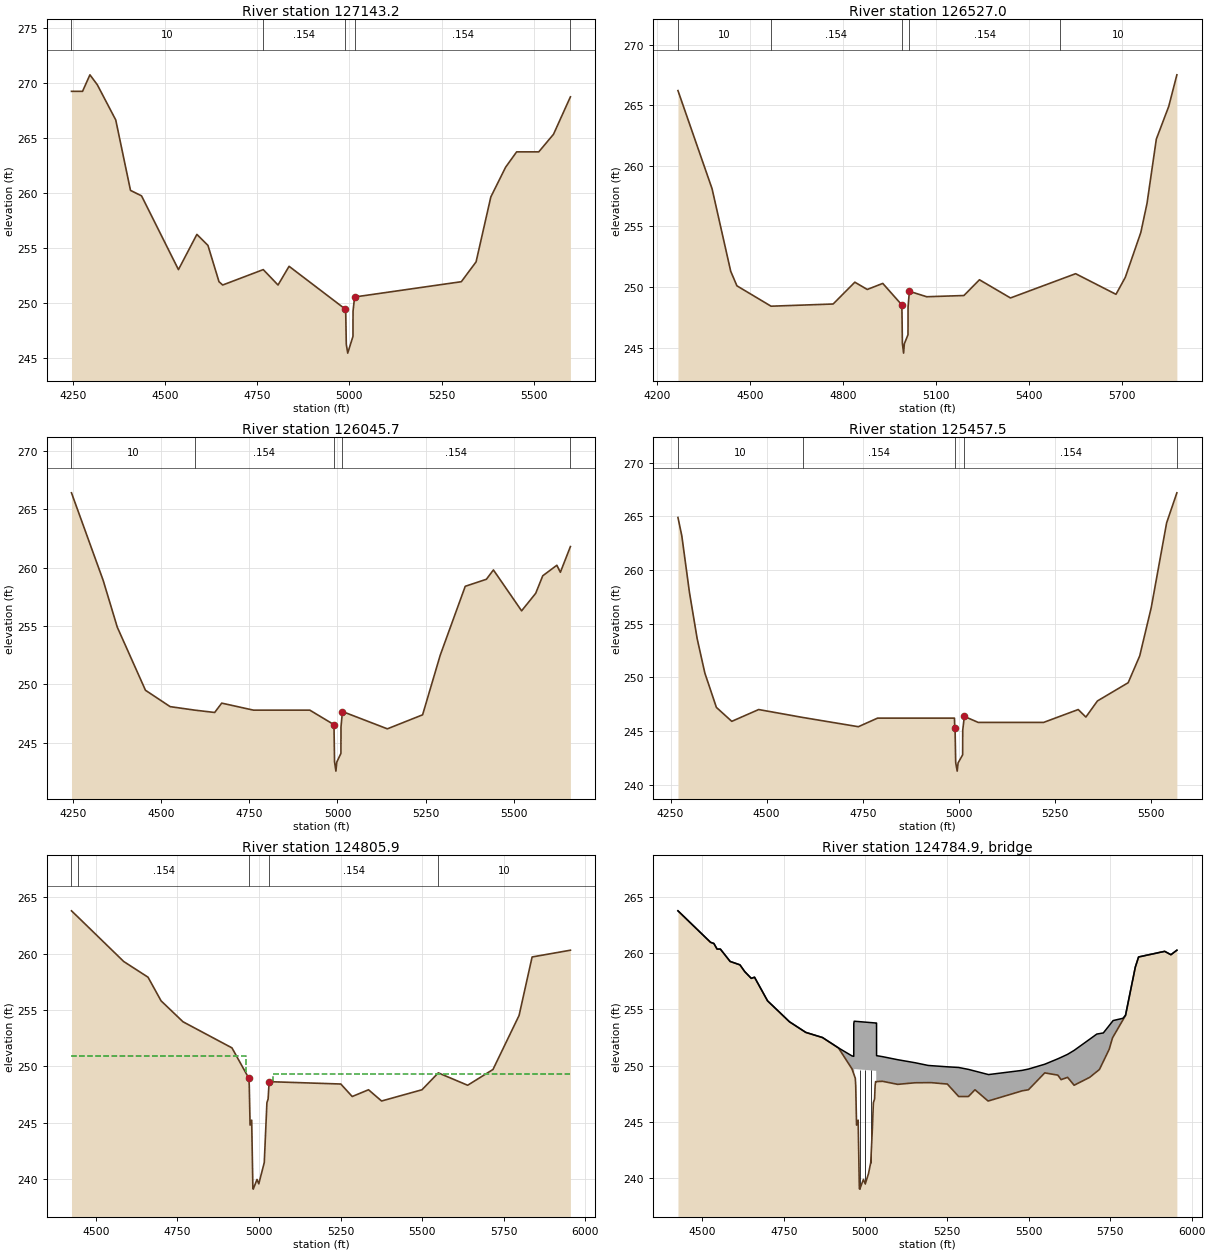
Type RM Length L Ch R = 1 ,127143.2,616.2,616.2,616.2
BEGIN DESCRIPTION:
Cross Section Moccasin Creek 63.0
END DESCRIPTION:
#Sta/Elev= 30
  4246.6   269.2  4276.6   269.2  4296.6   270.7  4316.6   269.8  4366.6   266.6
  4406.6   260.2  4436.6   259.7  4536.6     253  4586.6   256.2  4616.6   255.2
  4646.6   251.9  4656.6   251.6  4766.6     253  4806.6   251.6  4836.6   253.3
  4989.4   249.4  4990.3  248.95  4991.7  246.21  4995.6  245.41  5009.8  246.93
    5010  249.21  5014.2  250.51  5303.6   251.9  5343.6   253.7  5383.6   259.6
  5423.6   262.3  5453.6   263.7  5513.6   263.7  5553.6   265.3  5599.4   268.7
#Mann= 5 , 1 , 0
 4246.60      10       0  4766.6   0.154       0  4989.4   0.054       0
  5014.2   0.154       0  5599.4    0.22       0
Bank Sta=4989.40,5014.20
Exp/Cntr=0.3,0.1

Type RM Length L Ch R = 1 ,126527.0,481.3,481.3,481.3
BEGIN DESCRIPTION:
Cross Section Moccasin Creek 62.0
END DESCRIPTION:
#Sta/Elev= 30
  4268.5   266.2  4378.5   258.1  4438.5   251.3  4458.5   250.1  4568.5  248.42
  4768.5   248.6  4838.5   250.4  4878.5   249.8  4928.5   250.3  4989.4  248.54
  4990.3  248.09  4991.7  245.35  4995.6  244.55    4998  245.32  5009.8  246.07
    5010  248.35  5014.2  249.65    5070   249.2    5190   249.3    5240   250.6
    5340   249.1  5498.5  250.61    5550   251.1    5680   249.4    5710   250.8
    5760   254.5    5780   256.9    5810   262.2    5850   264.9  5876.2   267.5
#Mann= 5 , 1 , 0
 4268.50      10       0  4568.5   0.154       0  4989.4   0.054       0
  5014.2   0.154       0  5498.5      10       0
Bank Sta=4989.40,5014.20
Exp/Cntr=0.3,0.1

Type RM Length L Ch R = 1 ,126045.7,588.2,588.2,588.2
BEGIN DESCRIPTION:
Cross Section Moccasin Creek 61.0
END DESCRIPTION:
#Sta/Elev= 30
  4245.1   266.4  4335.1   258.9  4375.1   254.9  4455.1   249.5  4525.1   248.1
  4595.1   247.8  4651.5   247.6  4671.5   248.4  4761.5   247.8  4921.5   247.8
  4989.4  246.57  4990.3  246.12  4991.7  243.38  4995.6  242.58    4998  243.35
  5009.8   244.1    5010  246.38  5014.2  247.68  5141.6   246.2  5241.6   247.4
  5291.6   252.5  5362.6   258.4  5422.6     259  5442.6   259.8  5522.6   256.3
  5562.6   257.8  5582.6   259.3  5622.6   260.2  5632.6   259.6  5661.1   261.8
#Mann= 5 , 1 , 0
 4245.10      10       0  4595.1   0.154       0  4989.4   0.054       0
  5014.2   0.154       0  5661.1    0.22       0
Bank Sta=4989.40,5014.20
Exp/Cntr=0.3,0.1

Type RM Length L Ch R = 1 ,125457.5,651.6,651.6,651.6
BEGIN DESCRIPTION:
Cross Section Moccasin Creek 60.0
END DESCRIPTION:
#Sta/Elev= 30
  4269.2   264.9  4279.2   263.2  4299.2   257.9  4319.2   253.6  4339.2   250.4
  4369.2   247.2  4409.2   245.9  4479.2     247  4594.2  246.26  4738.5   245.4
  4788.5   246.2  4988.5   246.2  4989.4  245.25  4990.3   244.8  4991.7  242.06
  4995.6  241.26    4998  242.03  5009.8  242.78    5010  245.06  5014.2  246.36
  5050.4   245.8  5220.4   245.8  5310.4     247  5330.4   246.3  5360.4   247.8
  5440.4   249.5  5470.4     252  5500.4   256.5  5540.4   264.4  5567.1   267.2
#Mann= 5 , 1 , 0
 4269.20      10       0  4594.2   0.154       0  4989.4   0.054       0
  5014.2   0.154       0  5567.1    0.22       0
Bank Sta=4989.40,5014.20
Exp/Cntr=0.5,0.3

Type RM Length L Ch R = 1 ,124805.9,42,42,42
BEGIN DESCRIPTION:
Upstream Section of Bridge/Culvert/Weir
END DESCRIPTION:
#Sta/Elev= 30
  4425.3  263.81  4446.5  263.22  4585.3  259.31    4660  257.91    4700  255.81
  4767.2  253.95  4917.3  251.63    4969  248.93  4970.3  248.27  4972.8  244.77
  4977.7  245.21  4981.4  239.13  4982.6  239.08    4994  239.94  4999.5  239.55
  5016.3  241.44  5024.4  246.76  5028.1  247.09  5031.2  248.63  5250.9  248.42
  5285.9  247.31  5335.9  247.91  5375.9  246.91  5499.8  247.91  5549.8  249.41
  5639.8  248.31  5717.4  249.71  5797.4  254.51  5837.4  259.71  5954.8  260.31
#Mann= 5 , 1 , 0
 4425.30   0.154       0  4446.5   0.154       0    4969   0.054       0
  5031.2   0.154       0  5549.8      10       0
#XS Ineff= 2 , 0
       0    4959   250.9    5043       0   249.3
Bank Sta=4969.00,5031.20
Exp/Cntr=0.5,0.3

Type RM Length L Ch R = 3 ,124784.9,,,
BEGIN DESCRIPTION:
Williams-White Rd
Structure ID: FRMCCR6
END DESCRIPTION:
Bridge Culvert--1,0,-1,-1, 0
Deck Dist Width WeirC Skew NumUp NumDn MinLoCord MaxHiCord MaxSubmerge Is_Ogee
10,22,2.6,, 56, 56,,,0.95,0,1,1,,
  4425.3  4525.3  4535.3  4545.3  4555.3  4585.3  4615.3    4630    4650    4660
    4700  4767.2  4816.9  4868.4  4917.3  4958.7  4964.1 4964.19  4964.3 4965.61
  4965.7 5033.09  5033.2  5034.1 5034.21  5052.8  5099.1  5152.6  5192.5  5250.9
  5285.9  5315.9  5335.9  5375.9  5377.6  5479.8  5499.8  5549.8  5589.8  5599.8
  5619.8  5639.8  5687.4  5709.3  5717.4  5729.3  5747.4  5757.4  5759.3  5789.3
  5797.4  5827.4  5837.4  5917.4  5936.5  5954.8
  263.75  260.95  260.85  260.35  260.35  259.25  258.95  258.35  257.75  257.85
  255.75  253.89  252.95  252.49  251.57  250.86  250.82  250.83  253.73  253.94
  253.94  253.78  253.78  253.78  250.88  250.79  250.52  250.25  250.01  249.89
  249.83  249.66  249.51  249.21   249.2  249.57  249.69  250.12   250.6  250.73
     251  251.35  252.34   252.8  252.84   252.9  253.56  253.93     254   254.2
  254.48  258.75  259.65  260.15  259.85  260.25
  263.75  260.95  260.85  260.35  260.35  259.25  258.95  258.35  257.75  257.85
  255.75  253.89  252.95  252.49  251.57  249.71  249.27  249.26  249.25  249.15
  249.69  249.53  248.57  248.57  248.57   248.6  248.33  248.47  248.48  248.36
  247.25  247.25  247.85  246.85  246.86  247.75  247.85  249.35  249.15  248.75
  248.95  248.25  248.95  249.46  249.65  250.36  251.45  252.45  252.55  254.05
  254.45  258.75  259.65  260.15  259.85  260.25
  4425.3  4525.3  4535.3  4545.3  4555.3  4585.3  4615.3    4630    4650    4660
    4700  4767.2  4816.9  4868.4  4917.3  4958.7  4964.1 4964.19  4964.3 4965.61
  4965.7 5033.09  5033.2  5034.1 5034.21  5052.8  5099.1  5152.6  5192.5  5250.9
  5285.9  5315.9  5335.9  5375.9  5377.6  5479.8  5499.8  5549.8  5589.8  5599.8
  5619.8  5639.8  5687.4  5709.3  5717.4  5729.3  5747.4  5757.4  5759.3  5789.3
  5797.4  5827.4  5837.4  5917.4  5936.5  5954.8
   263.7  260.91  260.81  260.31  260.31  259.21  258.91  258.31  257.71  257.81
  255.71  253.85  252.91  252.45  251.53  250.86  250.82  250.83  253.73  253.94
  253.94  253.78  253.78  253.78  250.88  250.79  250.52  250.25  250.01  249.89
  249.83  249.66  249.51  249.21   249.2  249.57  249.69  250.12   250.6  250.73
     251  251.35  252.34   252.8  252.84   252.9  253.56  253.93     254   254.2
  254.48  258.71  259.61  260.11  259.81   260.2
  263.65  260.85  260.75  260.25  260.25  259.15  258.85  258.25  257.65  257.75
  255.65  253.79  252.85  252.39  251.47  249.61  249.17  249.16  249.15  249.05
  249.59  249.43  248.47  248.47  248.47   248.5  248.23  248.37  248.38  248.26
  247.15  247.15  247.75  246.75  246.76  247.65  247.75  249.25  249.05  248.65
  248.85  248.15  248.85  249.36  249.55  250.26  251.35  252.35  252.45  253.95
  254.35  258.65  259.55  260.05  259.75  260.15
Pier Skew, UpSta & Num, DnSta & Num=,4982.6, 2 ,4982.6, 2 , 0 , 0 , 0 ,,
       1       1
  238.04  250.65
       1       1
  237.94  250.55
Pier Skew, UpSta & Num, DnSta & Num=,4999.5, 2 ,4999.5, 2 , 0 , 0 , 0 ,,
       1       1
  238.53  250.61
       1       1
  238.43  250.51
Pier Skew, UpSta & Num, DnSta & Num=,5016.3, 2 ,5016.3, 2 , 0 , 0 , 0 ,,
       1       1
  240.31  250.57
       1       1
  240.21  250.47
BR Coef= 1 , 1 , 0 ,1.25, 0 ,,,0.8,0,2,0,
Wspro=,,,, 1 ,,,, 0 ,,,, 0 ,,,,-1 ,-1 ,-1 , 0 , 0 , 0 , 0 , 0
BC Design=,, 0 ,, 0 ,,,,,,
BR U #Sta/Elev= 107
  4425.3  263.75  4446.5  263.16  4525.3  260.95  4535.3  260.85  4545.3  260.35
  4555.3  260.35  4585.3  259.25  4606.5  259.04  4615.3  258.95  4616.5   258.9
    4630  258.35    4650  257.75    4660  257.85    4700  255.75  4706.5  255.57
  4716.8  255.29  4765.7  253.93  4767.2  253.89  4816.1  252.97  4816.9  252.95
    4865  252.52  4868.4  252.49  4913.9  251.63  4917.3  251.57  4958.7  249.71
  4964.1  249.27 4964.19  249.26  4964.3  249.25 4964.41  249.24  4965.5  249.16
 4965.61  249.15  4965.7  249.14  4965.8  249.13    4969  248.87  4970.3  248.21
  4972.8  244.71  4977.7  245.15  4981.4  239.07  4982.6  239.02    4994  239.88
  4999.5  239.49  5009.4  240.39  5016.3  241.38  5020.9  244.12  5024.4   246.7
  5028.1  247.03  5029.7   248.2  5031.2  248.57    5033  248.57 5033.09  248.57
  5033.2  248.57  5033.3  248.57 5033.99  248.57  5034.1  248.57 5034.21  248.57
  5035.9  248.58  5052.8   248.6  5088.9  248.39  5099.1  248.33  5140.4  248.44
  5152.6  248.47  5192.5  248.48  5201.8  248.48  5245.5  248.37  5250.9  248.36
  5285.9  247.25  5295.9  247.25  5315.9  247.25  5335.9  247.85  5375.9  246.85
  5377.6  246.86  5467.6  247.64  5479.8  247.75  5499.8  247.85  5517.6  248.38
  5549.8  249.35  5567.6  249.26  5589.8  249.15  5599.8  248.75  5619.8  248.95
  5627.6  248.68  5639.8  248.25  5687.4  248.95  5709.3  249.46  5717.4  249.65
  5729.3  250.36  5747.4  251.45  5757.4  252.45  5759.3  252.55  5789.3  254.05
  5797.4  254.45  5809.3  256.16  5819.3  257.59  5827.4  258.75  5829.3  258.92
  5837.4  259.65  5849.3  259.72  5859.3  259.79  5869.3  259.85  5879.3  259.91
  5889.3  259.97  5899.3  260.04  5909.3   260.1  5917.4  260.15  5929.3  259.96
  5936.5  259.85  5954.8  260.25
BR U #Mann= 5
 4425.30   0.154  4446.5   0.154    4969   0.054  5031.2   0.154  5549.8      10
BR U Banks=4969.00,5031.20
BR D #Sta/Elev= 107
  4425.3  263.65  4446.5  263.06  4525.3  260.85  4535.3  260.75  4545.3  260.25
  4555.3  260.25  4585.3  259.15  4606.5  258.94  4615.3  258.85  4616.5   258.8
    4630  258.25    4650  257.65    4660  257.75    4700  255.65  4706.5  255.47
  4716.8  255.19  4765.7  253.83  4767.2  253.79  4816.1  252.87  4816.9  252.85
    4865  252.42  4868.4  252.39  4913.9  251.53  4917.3  251.47  4958.7  249.61
  4964.1  249.17 4964.19  249.16  4964.3  249.15 4964.41  249.14  4965.5  249.06
 4965.61  249.05  4965.7  249.04  4965.8  249.03    4969  248.77  4970.3  248.11
  4972.8  244.61  4977.7  245.05  4981.4  238.97  4982.6  238.92    4994  239.78
  4999.5  239.39  5009.4  240.29  5016.3  241.28  5020.9  244.02  5024.4   246.6
  5028.1  246.93  5029.7   248.1  5031.2  248.47    5033  248.47 5033.09  248.47
  5033.2  248.47  5033.3  248.47 5033.99  248.47  5034.1  248.47 5034.21  248.47
  5035.9  248.48  5052.8   248.5  5088.9  248.29  5099.1  248.23  5140.4  248.34
  5152.6  248.37  5192.5  248.38  5201.8  248.38  5245.5  248.27  5250.9  248.26
  5285.9  247.15  5295.9  247.15  5315.9  247.15  5335.9  247.75  5375.9  246.75
  5377.6  246.76  5467.6  247.54  5479.8  247.65  5499.8  247.75  5517.6  248.28
  5549.8  249.25  5567.6  249.16  5589.8  249.05  5599.8  248.65  5619.8  248.85
  5627.6  248.58  5639.8  248.15  5687.4  248.85  5709.3  249.36  5717.4  249.55
  5729.3  250.26  5747.4  251.35  5757.4  252.35  5759.3  252.45  5789.3  253.95
  5797.4  254.35  5809.3  256.06  5819.3  257.49  5827.4  258.65  5829.3  258.82
  5837.4  259.55  5849.3  259.62  5859.3  259.69  5869.3  259.75  5879.3  259.81
  5889.3  259.87  5899.3  259.94  5909.3     260  5917.4  260.05  5929.3  259.86
  5936.5  259.75  5954.8  260.15
BR D #Mann= 5
 4425.30   0.154  4446.5   0.154    4969   0.054  5031.2   0.154  5549.8      10
BR D Banks=4969.00,5031.20

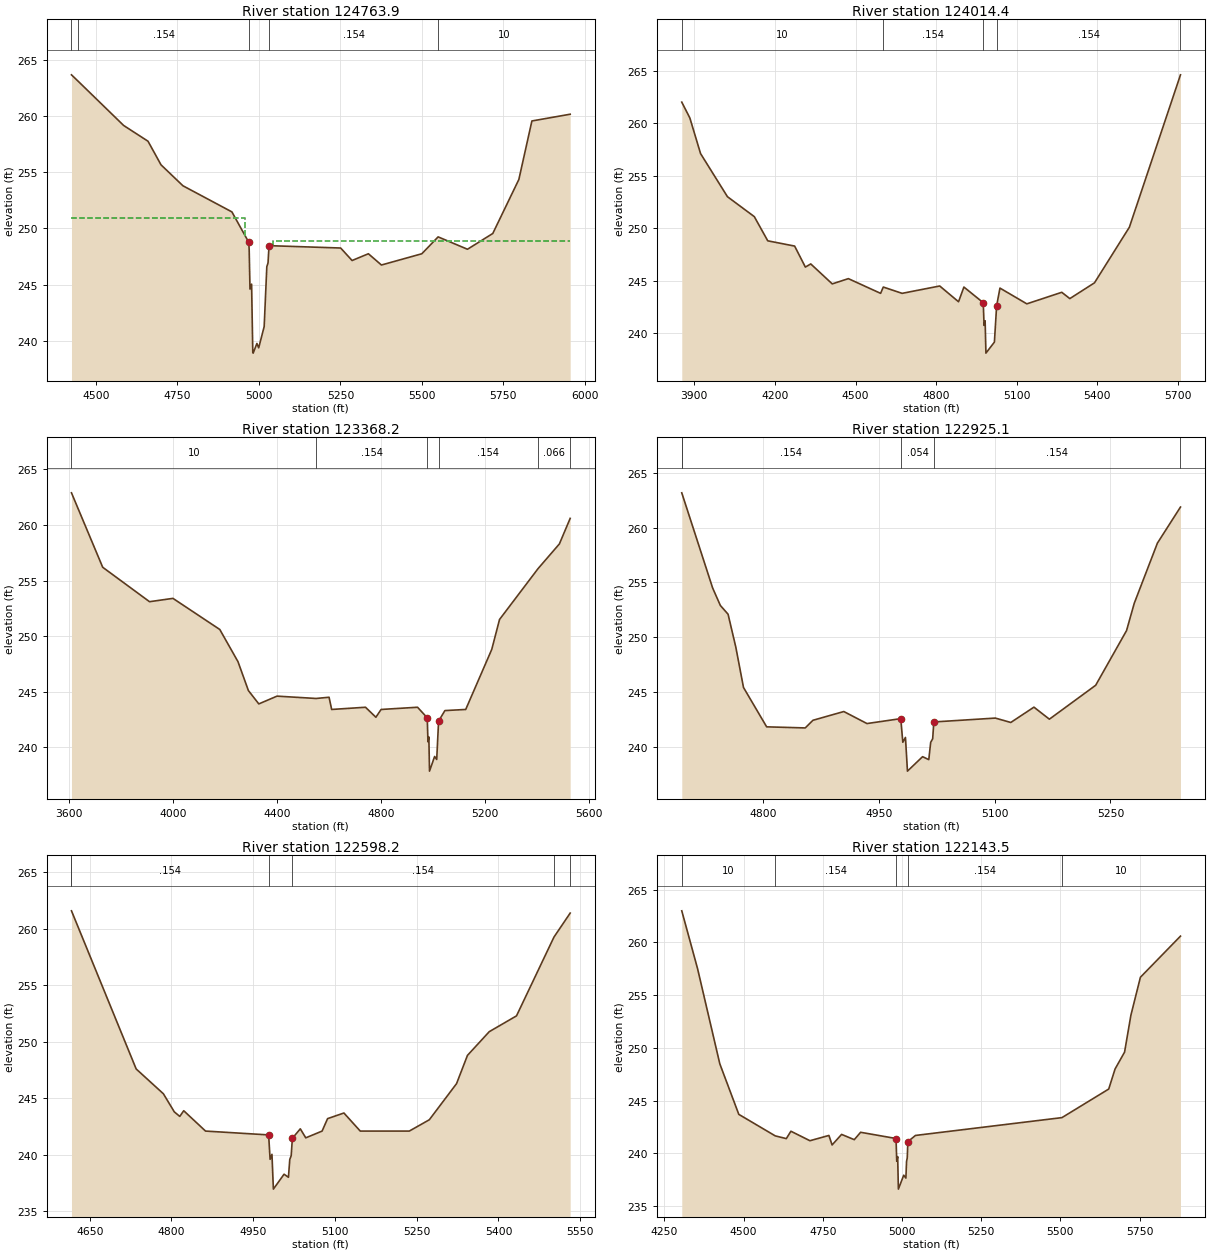
Type RM Length L Ch R = 1 ,124763.9,749.5,749.5,749.5
BEGIN DESCRIPTION:
Downstream Section of Bridge/Culvert/Weir
END DESCRIPTION:
#Sta/Elev= 30
  4425.3  263.65  4446.5  263.06  4585.3  259.15    4660  257.75    4700  255.65
  4767.2  253.79  4917.3  251.47    4969  248.77  4970.3  248.11  4972.8  244.61
  4977.7  245.05  4981.4  238.97  4982.6  238.92    4994  239.78  4999.5  239.39
  5016.3  241.28  5024.4   246.6  5028.1  246.93  5031.2  248.47  5250.9  248.26
  5285.9  247.15  5335.9  247.75  5375.9  246.75  5499.8  247.75  5549.8  249.25
  5639.8  248.15  5717.4  249.55  5797.4  254.35  5837.4  259.55  5954.8  260.15
#Mann= 5 , 1 , 0
 4425.30   0.154       0  4446.5   0.154       0    4969   0.054       0
  5031.2   0.154       0  5549.8      10       0
#XS Ineff= 2 , 0
       0    4959   250.9    5043       0   248.9
Bank Sta=4969.00,5031.20
Exp/Cntr=0.5,0.3

Type RM Length L Ch R = 1 ,124014.4,646.2,646.2,646.2
BEGIN DESCRIPTION:
Cross Section Moccasin Creek 58.0
END DESCRIPTION:
#Sta/Elev= 30
  3853.2     262  3883.2   260.5  3923.2   257.1  4023.2     253  4123.2   251.1
  4173.2   248.8  4273.2   248.3  4313.2   246.3  4333.2   246.6  4413.2   244.7
  4473.2   245.2  4593.2   243.8  4603.2   244.4  4673.2   243.8  4813.2   244.5
  4883.2     243  4903.2   244.4  4975.2  242.91 4978.24  240.75 4982.16  241.19
 4985.12  238.11 5016.72  239.16 5024.96  242.61  5037.4   244.3  5137.4   242.8
  5267.4   243.9  5297.4   243.3  5389.1   244.8  5519.1   250.1  5709.2   264.6
#Mann= 5 , 1 , 0
 3853.20      10       0  4603.2   0.154       0  4975.2   0.054       0
 5024.96   0.154       0  5709.2    0.22       0
Bank Sta=4975.20,5024.96
Exp/Cntr=0.3,0.1

Type RM Length L Ch R = 1 ,123368.2,443.1,443.1,443.1
BEGIN DESCRIPTION:
Cross Section Moccasin Creek 57.0
END DESCRIPTION:
#Sta/Elev= 30
  3610.9   262.9  3730.9   256.2  3910.9   253.1  4000.9   253.4  4180.9   250.6
  4250.9   247.7  4290.9   245.1  4330.9   243.9  4400.9   244.6  4550.9  244.39
  4600.9   244.5  4610.9   243.4  4740.9   243.6  4780.9   242.7  4800.9   243.4
  4940.9   243.6  4978.3  242.65 4980.96  240.49 4984.39  240.93 4986.98  237.85
 5006.58  239.17 5014.63   238.9 5021.84  242.35  5046.1   243.3  5126.1   243.4
  5226.1   248.8  5256.1   251.5  5403.9  256.07  5486.1   258.3  5527.6   260.6
#Mann= 6 , 1 , 0
 3610.90      10       0  4550.9   0.154       0  4978.3   0.054       0
 5021.84   0.154       0  5403.9   0.066       0  5527.6    0.22       0
Bank Sta=4978.30,5021.84
Exp/Cntr=0.3,0.1

Type RM Length L Ch R = 1 ,122925.1,326.9,326.9,326.9
BEGIN DESCRIPTION:
Cross Section Moccasin Creek 56.0
END DESCRIPTION:
#Sta/Elev= 30
  4694.5   263.2  4734.5   254.5  4744.5   252.9  4754.5   252.1  4764.5   249.1
  4774.5   245.4  4804.5   241.8  4854.5   241.7  4864.5   242.4  4904.5   243.2
  4934.5   242.1  4978.3  242.55 4980.96  240.39 4984.39  240.83 4986.98  237.75
 5006.58  239.07 5014.63   238.8 5017.08  240.38 5019.67  240.71 5020.79  241.88
 5021.84  242.25  5100.9   242.6  5120.9   242.2  5150.9   243.6  5170.9   242.5
  5230.9   245.6  5270.9   250.6  5280.9   253.1  5310.9   258.6  5340.8   261.9
#Mann= 5 , 1 , 0
 4694.50    0.22       0  4694.5   0.154       0  4978.3   0.054       0
 5021.84   0.154       0  5340.8    0.22       0
Bank Sta=4978.30,5021.84
Exp/Cntr=0.3,0.1

Type RM Length L Ch R = 1 ,122598.2,454.7,454.7,454.7
BEGIN DESCRIPTION:
Cross Section Moccasin Creek 55.5
END DESCRIPTION:
#Sta/Elev= 30
  4616.5   261.6  4735.2   247.6  4785.2   245.4  4805.2   243.8  4815.2   243.4
  4822.5   243.9  4862.5   242.1  4978.3  241.76 4980.96   239.6 4984.39  240.04
 4986.98  236.96 5006.58  238.28 5014.63  238.01 5017.08  239.59 5019.67  239.92
 5021.84  241.46  5036.4   242.3  5046.4   241.5  5076.4   242.1  5086.4   243.2
  5116.4   243.7  5146.4   242.1  5236.4   242.1  5273.1   243.1  5323.1   246.3
  5343.1   248.8  5383.1   250.9  5433.1   252.3  5501.9  259.28  5531.6   261.4
#Mann= 6 , 1 , 0
 4616.50    0.22       0  4616.5   0.154       0  4978.3   0.054       0
 5021.84   0.154       0  5501.9   0.066       0  5531.6    0.22       0
Bank Sta=4978.30,5021.84
Exp/Cntr=0.3,0.1

Type RM Length L Ch R = 1 ,122143.5,407,407,407
BEGIN DESCRIPTION:
Cross Section Moccasin Creek 55.0
END DESCRIPTION:
#Sta/Elev= 30
  4305.1     263  4355.1   257.5  4425.1   248.5  4485.1   243.7  4600.1  241.66
  4635.1   241.4  4649.6   242.1  4709.6   241.2  4769.6   241.7  4779.6   240.8
  4809.6   241.8  4849.6   241.3  4869.6     242  4981.4  241.41 4983.68  239.25
 4986.62  239.69 4988.84  236.61 5005.64  237.93 5012.54  237.66 5014.64  239.24
 5016.86  239.57 5018.72  241.11  5042.8   241.7  5505.1  243.39  5652.8   246.1
  5672.8     248  5702.8   249.6  5722.8   253.1  5752.8   256.7  5879.3   260.6
#Mann= 5 , 1 , 0
 4305.10      10       0  4600.1   0.154       0  4981.4   0.054       0
 5018.72   0.154       0  5505.1      10       0
Bank Sta=4981.40,5018.72
Exp/Cntr=0.3,0.1