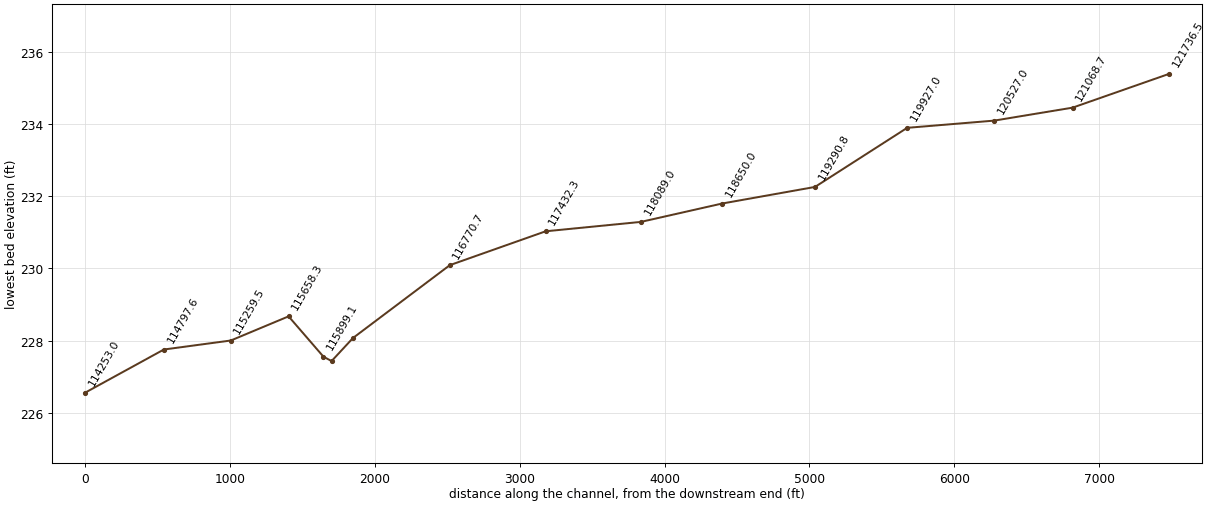
HEC-RAS study Moccasin_Creek_FINAL.prj: Moccasin Creek - Detail Study

--- Moccasin_Creek_FINAL.g01 (geometry) --- (continued)

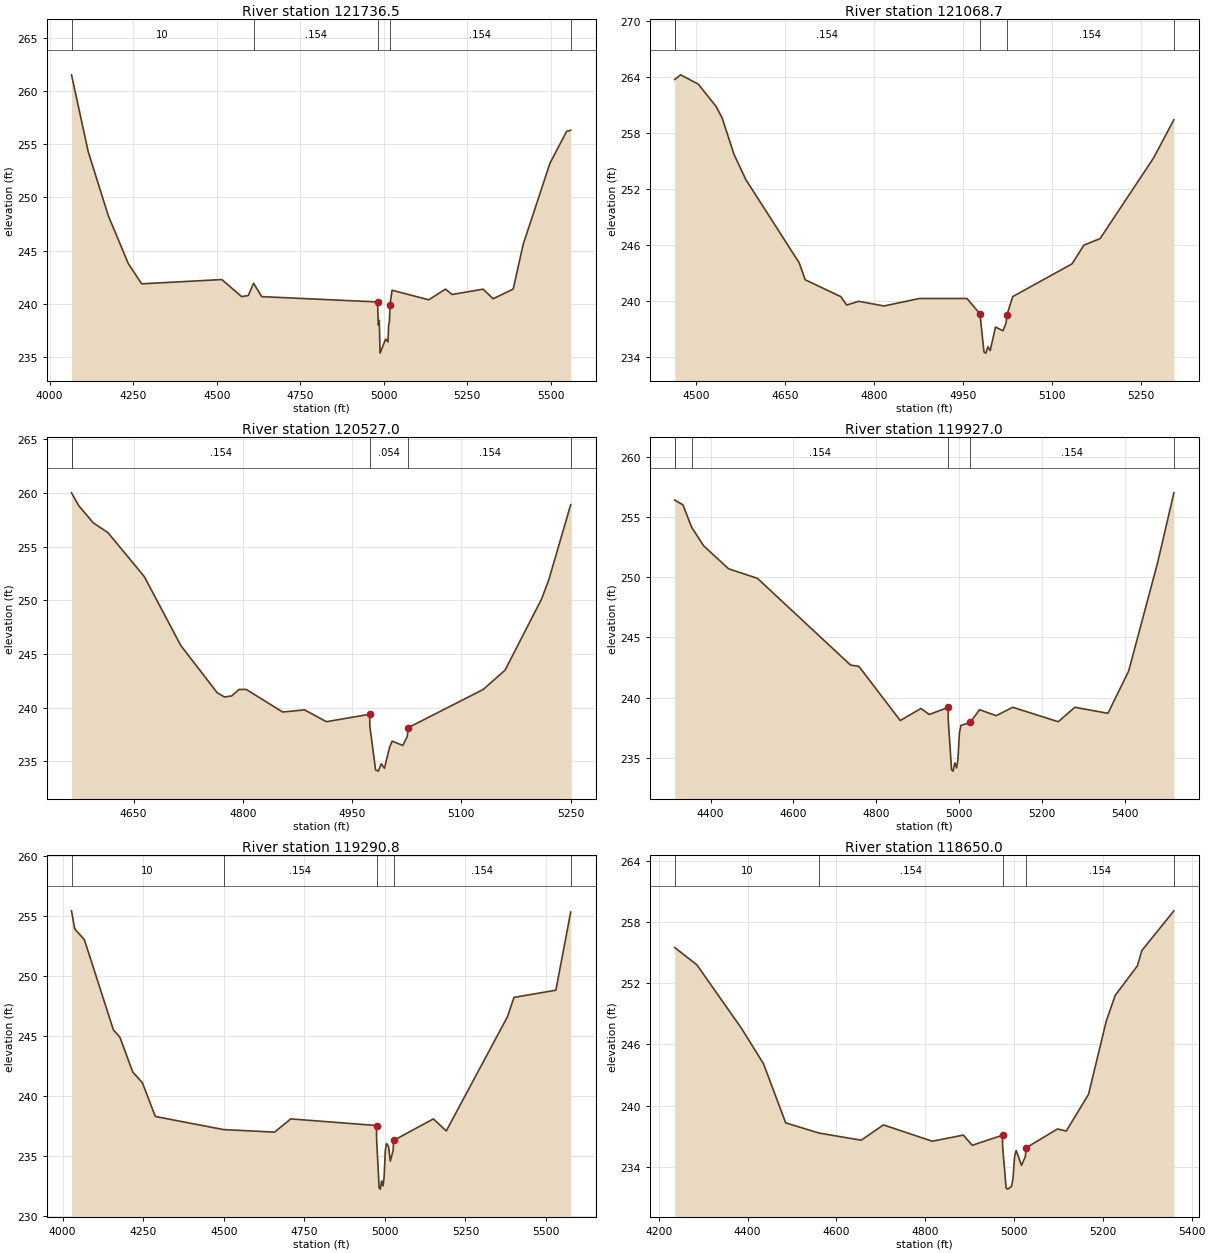
Type RM Length L Ch R = 1 ,121736.5,667.8,667.8,667.8
BEGIN DESCRIPTION:
Cross Section Moccasin Creek 54.0
END DESCRIPTION:
#Sta/Elev= 30
  4065.4   261.5  4115.4   254.3  4175.4   248.3  4235.4   243.8  4275.4   241.9
  4515.4   242.3  4574.5   240.7  4594.5   240.8  4610.4  241.96  4634.5   240.7
  4981.4   240.2 4983.68  238.04 4986.62  238.48 4988.84   235.4 5005.64  236.72
 5012.54  236.45 5014.64  238.03 5016.86  238.36 5018.72   239.9  5024.7   241.3
  5134.7   240.4  5184.7   241.4  5204.7   240.9  5297.3   241.4  5327.3   240.5
  5387.3   241.4  5417.3   245.6  5497.3   253.2  5547.3   256.2  5559.5   256.3
#Mann= 5 , 1 , 0
 4065.40      10       0  4610.4   0.154       0  4981.4   0.054       0
 5018.72   0.154       0  5559.5    0.22       0
Bank Sta=4981.40,5018.72
Exp/Cntr=0.3,0.1

Type RM Length L Ch R = 1 ,121068.7,541.7,541.7,541.7
BEGIN DESCRIPTION:
Cross Section Moccasin Creek 53.5
END DESCRIPTION:
#Sta/Elev= 30
  4463.3   263.7  4473.3   264.2  4503.3   263.2  4533.3   260.8  4543.3   259.6
  4563.3   255.7  4583.3     253  4673.3   244.1  4683.3   242.3  4743.3   240.5
  4753.3   239.6  4773.3     240  4816.1   239.5  4876.1   240.3  4956.1   240.3
 4977.98  238.66 4984.76  234.57 4987.94  234.46 4991.42  235.14  4995.2  234.73
  5004.2  237.25 5016.74  236.85 5021.96  237.67 5023.28  238.51  5033.2   240.5
  5133.2     244  5153.2     246  5180.5   246.7  5270.5   255.3  5304.9   259.4
#Mann= 5 , 1 , 0
 4463.30    0.22       0  4463.3   0.154       0 4977.98   0.054       0
 5023.28   0.154       0  5304.9    0.22       0
Bank Sta=4977.98,5023.28
Exp/Cntr=0.3,0.1

Type RM Length L Ch R = 1 ,120527.0,600,600,600
BEGIN DESCRIPTION:
Cross Section Moccasin Creek 53.0
END DESCRIPTION:
#Sta/Elev= 30
  4564.7     260  4574.7   258.8  4594.7   257.2  4614.7   256.3  4664.7   252.2
  4714.7   245.8  4764.7   241.4  4774.7     241  4784.7   241.1  4794.7   241.7
  4804.7   241.7  4854.7   239.6  4884.7   239.8  4914.7   238.7  4974.1  239.39
 4974.31   238.3 4982.22  234.21 4985.93   234.1 4989.99  234.78  4994.4  234.37
 5001.33   236.3  5004.9  236.89 5019.53  236.49 5025.62  237.31 5027.16  238.15
    5130   241.7    5160   243.5    5210   250.1    5220   251.9  5250.1   258.9
#Mann= 5 , 1 , 0
 4564.70    0.22       0  4564.7   0.154       0  4974.1   0.054       0
 5027.16   0.154       0  5250.1    0.22       0
Bank Sta=4974.10,5027.16
Exp/Cntr=0.3,0.1

Type RM Length L Ch R = 1 ,119927.0,636.2,636.2,636.2
BEGIN DESCRIPTION:
Cross Section Moccasin Creek 52.0
END DESCRIPTION:
#Sta/Elev= 30
  4313.4   256.4  4333.4     256  4354.1  254.16  4383.4   252.6  4443.4   250.7
  4513.4   249.9  4738.3   242.7  4758.3   242.6  4858.3   238.1  4908.3   239.1
  4928.3   238.6  4974.1  239.19 4974.31   238.1 4982.22  234.01 4985.93   233.9
 4989.99  234.58  4994.4  234.17 4997.62  234.89 5001.33   237.1  5004.9  237.69
 5027.16  237.95    5050     239    5090   238.5    5130   239.2    5240     238
    5280   239.2    5360   238.7    5410   242.2    5480   251.2  5519.3     257
#Mann= 6 , 1 , 0
 4313.40    0.22       0  4313.4   0.066       0  4354.1   0.154       0
  4974.1   0.054       0 5027.16   0.154       0  5519.3    0.22       0
Bank Sta=4974.10,5027.16
Exp/Cntr=0.3,0.1

Type RM Length L Ch R = 1 ,119290.8,640.8,640.8,640.8
BEGIN DESCRIPTION:
Cross Section Moccasin Creek 51.0
END DESCRIPTION:
#Sta/Elev= 30
  4027.9   255.4  4037.9   253.9  4067.9     253  4157.9   245.5  4177.9   244.9
  4217.9     242  4247.9   241.1  4287.9   238.3  4499.9  237.21  4657.9     237
  4707.9   238.1  4974.1  237.55 4974.31  236.46 4982.22  232.37 4985.93  232.26
 4989.99  232.94  4994.4  232.53 4997.62  233.25 5001.33  235.46  5004.9  236.05
 5011.41  235.82 5016.94  234.59 5025.62  235.47 5027.16  236.31  5150.5   238.1
  5190.5   237.1  5380.5   246.6  5400.5   248.2  5530.5   248.8  5576.5   255.3
#Mann= 5 , 1 , 0
 4027.90      10       0  4499.9   0.154       0  4974.1   0.054       0
 5027.16   0.154       0  5576.5    0.22       0
Bank Sta=4974.10,5027.16
Exp/Cntr=0.3,0.1

Type RM Length L Ch R = 1 ,118650.0,561,561,561
BEGIN DESCRIPTION:
Cross Section Moccasin Creek 50.0
END DESCRIPTION:
#Sta/Elev= 30
  4235.9   255.5  4285.9   253.8  4385.9   247.6  4435.9   244.1  4485.9   238.3
  4560.9   237.3  4655.9   236.6  4705.9   238.1  4815.9   236.5  4885.9   237.1
  4905.9   236.1  4974.1  237.09 4974.31     236 4982.22  231.91 4985.93   231.8
  4994.4  232.07 4997.62  232.79 5001.33     235  5004.9  235.59 5016.94  234.13
 5025.62  235.01 5027.16  235.85  5097.8   237.7  5117.8   237.5  5167.8   241.1
  5207.8   248.3  5227.8   250.8  5277.8   253.7  5287.8   255.2    5360   259.1
#Mann= 5 , 1 , 0
 4235.90      10       0  4560.9   0.154       0  4974.1   0.054       0
 5027.16   0.154       0    5360    0.22       0
Bank Sta=4974.10,5027.16
Exp/Cntr=0.3,0.1

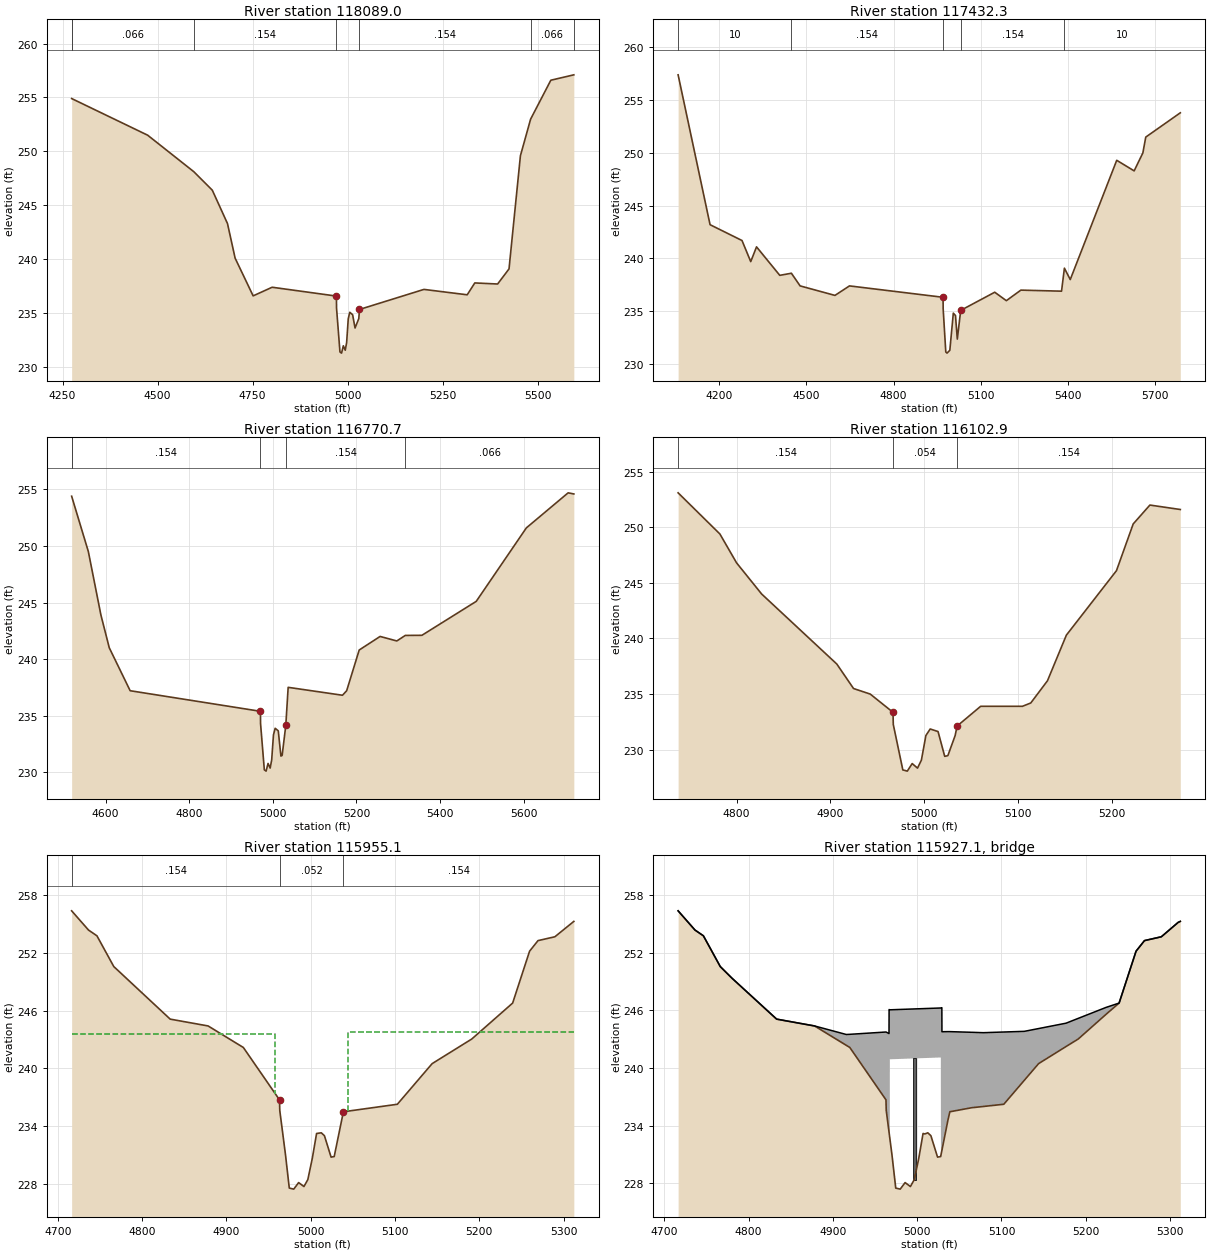
Type RM Length L Ch R = 1 ,118089.0,656.7,656.7,656.7
BEGIN DESCRIPTION:
Cross Section Moccasin Creek 49.0
END DESCRIPTION:
#Sta/Elev= 30
  4273.9   254.9  4473.9   251.5  4595.1  248.12  4643.9   246.4  4683.9   243.3
  4703.9   240.1  4751.3   236.6  4801.3   237.4  4970.4  236.58 4970.64  235.49
 4979.68   231.4 4983.92  231.29 4988.56  231.97  4993.6  231.56 4997.28  232.28
 5001.52  234.49  5005.6  235.08 5013.04  234.85 5019.36  233.62 5029.28   234.5
 5031.04  235.34  5200.6   237.2  5314.4   236.7  5334.4   237.8  5394.4   237.7
  5424.4   239.1  5454.4   249.6  5481.2  252.99  5534.4   256.6  5594.9   257.1
#Mann= 7 , 1 , 0
 4273.90    0.22       0  4273.9   0.066       0  4595.1   0.154       0
  4970.4   0.054       0 5031.04   0.154       0  5481.2   0.066       0
  5594.9    0.22       0
Bank Sta=4970.40,5031.04
Exp/Cntr=0.3,0.1

Type RM Length L Ch R = 1 ,117432.3,661.6,661.6,661.6
BEGIN DESCRIPTION:
Cross Section Moccasin Creek 48.0
END DESCRIPTION:
#Sta/Elev= 30
  4058.1   257.4  4168.1   243.2  4278.1   241.7  4308.1   239.7  4328.1   241.1
  4408.1   238.4  4448.1   238.6  4478.1   237.4  4598.1   236.5  4648.1   237.4
  4970.4  236.32 4970.64  235.23 4979.68  231.14 4983.92  231.03  4993.6   231.3
  5005.6  234.82 5013.04  234.59 5019.36  232.36 5031.04  235.08  5148.2   236.8
  5188.2     236  5238.2     237  5378.2   236.9  5388.1  239.08  5408.2     238
  5568.2   249.3  5628.2   248.3  5658.2     250  5668.2   251.5  5787.1   253.8
#Mann= 5 , 1 , 0
 4058.10      10       0  4448.1   0.154       0  4970.4   0.054       0
 5031.04   0.154       0  5388.1      10       0
Bank Sta=4970.40,5031.04
Exp/Cntr=0.3,0.1

Type RM Length L Ch R = 1 ,116770.7,667.8,667.8,667.8
BEGIN DESCRIPTION:
Cross Section Moccasin Creek 47.0
END DESCRIPTION:
#Sta/Elev= 30
  4518.6   254.4  4558.6   249.5  4588.6   243.9  4608.6     241  4658.6   237.2
  4970.4  235.38 4970.64  234.29 4979.68   230.2 4983.92  230.09 4988.56  230.77
  4993.6  230.36 4997.28  231.08 5001.52  233.29  5005.6  233.88 5013.04  233.65
 5019.36  231.42 5022.32  231.48 5031.04  234.14  5036.7   237.5  5166.7   236.8
  5176.7   237.2  5206.7   240.8  5256.7     242  5296.7   241.6    5317  242.09
  5356.7   242.1  5486.7   245.1  5606.7   251.6  5706.7   254.7  5720.3   254.6
#Mann= 5 , 1 , 0
 4518.60    0.22       0  4518.6   0.154       0  4970.4   0.054       0
 5031.04   0.154       0    5317   0.066       0
Bank Sta=4970.40,5031.04
Exp/Cntr=0.3,0.1

Type RM Length L Ch R = 1 ,116102.9,147.8,147.8,147.8
BEGIN DESCRIPTION:
Cross Section Moccasin Creek 46.0
END DESCRIPTION:
#Sta/Elev= 30
 4737.72   253.1 4782.22   249.4 4800.02   246.8 4826.72     244 4906.82   237.7
 4924.62   235.5 4942.42     235  4966.7  233.36 4966.97  232.27 4977.14  228.18
 4981.91  228.07 4987.13  228.75  4992.8  228.34 4996.94  229.06 5001.71  231.27
  5006.3  231.86 5014.67  231.63 5021.78   229.4 5025.11  229.46 5032.94  231.28
 5034.92  232.12 5060.08   233.9 5104.58   233.9 5113.48   234.2 5131.28   236.2
 5151.39   240.3 5204.79   246.1 5222.59   250.3 5240.39     252 5272.79   251.6
#Mann= 3 , 1 , 0
 4737.72   0.154       0  4966.7   0.054       0 5034.92   0.154       0
Bank Sta=4966.70,5034.92
Exp/Cntr=0.5,0.3

Type RM Length L Ch R = 1 ,115955.1,56,56,56
BEGIN DESCRIPTION:
Upstream Section of Bridge/Culvert/Weir
END DESCRIPTION:
#Sta/Elev= 30
  4716.4  256.39  4736.4  254.39  4746.4  253.79  4766.4  250.59  4833.3  245.12
  4878.3  244.41  4920.1  242.17    4963  236.72  4963.3  235.63  4970.1  231.01
  4974.6  227.54  4979.9  227.43  4985.7  228.11    4992   227.7  4996.6  228.42
  5001.9  230.63    5007  233.22  5012.6  233.29  5016.3  232.99  5024.2  230.76
  5027.9  230.82  5038.8  235.48  5102.8  236.26  5144.1  240.49  5191.1  243.05
  5239.6  246.79  5259.7  252.19  5269.7  253.29  5289.7  253.69  5312.2  255.29
#Mann= 3 , 1 , 0
 4716.40   0.154       0    4963   0.052       0  5038.8   0.154       0
#XS Ineff= 2 , 0
       0    4958   243.6    5044       0   243.8
Bank Sta=4963.00,5038.80
Exp/Cntr=0.5,0.3

Type RM Length L Ch R = 3 ,115927.1,,,
BEGIN DESCRIPTION:
Sheppard School Rd
Structure ID: WK_MCCR5
END DESCRIPTION:
Bridge Culvert--1,0,-1,-1, 0
Deck Dist Width WeirC Skew NumUp NumDn MinLoCord MaxHiCord MaxSubmerge Is_Ogee
10,36,2.6,, 35, 35,,,0.95,0,1,1,,
  4716.4  4736.4  4746.4  4766.4  4780.3  4833.3  4878.3    4916  4920.1    4963
  4963.3 4966.59  4966.7 4967.51  4967.6 5028.09  5028.2  5029.3 5029.41  5036.6
  5038.8  5064.7  5078.6  5102.8  5127.1  5144.1  5176.7  5191.1  5224.1  5239.6
  5259.7  5269.7  5289.7  5309.7  5312.2
  256.35  254.35  253.75  250.55  249.34  245.08  244.37  243.48   243.5  243.74
  243.73  243.58  246.08  246.05  246.05  246.24  246.24  246.27  243.77  243.78
  243.78  243.71  243.67  243.74  243.81   244.1  244.66  245.16   246.3  246.75
  252.15  253.25  253.65  255.15  255.25
  256.35  254.35  253.75  250.55  249.34  245.08  244.37  242.35  242.13  236.68
  235.59  233.35  233.28  232.73   240.9  241.09  230.91  231.39  231.44   234.6
  235.44  235.86  235.99  236.22  238.71  240.45  242.23  243.01  245.58  246.75
  252.15  253.25  253.65  255.15  255.25
  4716.4  4736.4  4746.4  4766.4  4780.3  4833.3  4878.3    4916  4920.1    4963
  4963.3 4966.59  4966.7 4967.51  4967.6 5028.09  5028.2  5029.3 5029.41  5036.6
  5038.8  5064.7  5078.6  5102.8  5127.1  5144.1  5176.7  5191.1  5224.1  5239.6
  5259.7  5269.7  5289.7  5309.7  5312.2
   256.3   254.3   253.7   250.5   249.3  245.04  244.33  243.48   243.5  243.74
  243.73  243.58  246.08  246.05  246.05  246.24  246.24  246.27  243.77  243.78
  243.78  243.71  243.67  243.74  243.81   244.1  244.66  245.16   246.3  246.71
   252.1   253.2   253.6   255.1   255.2
  256.25  254.25  253.65  250.45  249.24  244.98  244.27  242.25  242.03  236.58
  235.49  233.25  233.18  232.63   240.8  240.99  230.81  231.29  231.34   234.5
  235.34  235.76  235.89  236.12  238.61  240.35  242.13  242.91  245.48  246.65
  252.05  253.15  253.55  255.05  255.15
Pier Skew, UpSta & Num, DnSta & Num=,4996.6, 2 ,4996.6, 2 , 0 , 0 , 0 ,,
       3       3
  227.15     242
       3       3
  227.05   241.9
BR Coef= 1 , 1 , 0 ,1.25, 0 ,,,0.8,0,2,0,
Wspro=,,,, 1 ,,,, 0 ,,,, 0 ,,,,-1 ,-1 ,-1 , 0 , 0 , 0 , 0 , 0
BC Design=,, 0 ,, 0 ,,,,,,
BR U #Sta/Elev= 61
  4716.4  256.35  4736.4  254.35  4746.4  253.75  4766.4  250.55  4773.6  249.92
  4780.3  249.34  4820.8  246.08  4833.3  245.08  4868.5  244.52  4878.3  244.37
    4916  242.35  4920.1  242.13  4962.6  236.73    4963  236.68  4963.3  235.59
 4966.59  233.35  4966.7  233.28 4966.81  233.21  4967.4   232.8 4967.51  232.73
  4967.6  232.67  4967.7   232.6  4970.1  230.97  4974.6   227.5  4979.9  227.39
  4985.7  228.07    4992  227.66  4996.6  228.38  5001.9  230.59    5007  233.18
  5009.1  233.13  5012.6  233.25  5016.3  232.95  5024.2  230.72  5027.9  230.78
    5028  230.82 5028.09  230.86  5028.2  230.91  5028.3  230.96 5029.19  231.35
  5029.3  231.39 5029.41  231.44  5030.3  231.83  5036.6   234.6  5038.8  235.44
  5064.7  235.86  5078.6  235.99  5102.8  236.22  5127.1  238.71  5144.1  240.45
  5176.7  242.23  5191.1  243.01  5223.5  245.53  5224.1  245.58  5239.6  246.75
  5239.7  246.78  5259.7  252.15  5269.7  253.25  5289.7  253.65  5309.7  255.15
  5312.2  255.25
BR U #Mann= 3
 4716.40   0.154    4963   0.052  5038.8   0.154
BR U Banks=4963.00,5038.80
BR D #Sta/Elev= 61
  4716.4  256.25  4736.4  254.25  4746.4  253.65  4766.4  250.45  4773.6  249.82
  4780.3  249.24  4820.8  245.98  4833.3  244.98  4868.5  244.42  4878.3  244.27
    4916  242.25  4920.1  242.03  4962.6  236.63    4963  236.58  4963.3  235.49
 4966.59  233.25  4966.7  233.18 4966.81  233.11  4967.4   232.7 4967.51  232.63
  4967.6  232.57  4967.7   232.5  4970.1  230.87  4974.6   227.4  4979.9  227.29
  4985.7  227.97    4992  227.56  4996.6  228.28  5001.9  230.49    5007  233.08
  5009.1  233.03  5012.6  233.15  5016.3  232.85  5024.2  230.62  5027.9  230.68
    5028  230.72 5028.09  230.76  5028.2  230.81  5028.3  230.86 5029.19  231.25
  5029.3  231.29 5029.41  231.34  5030.3  231.73  5036.6   234.5  5038.8  235.34
  5064.7  235.76  5078.6  235.89  5102.8  236.12  5127.1  238.61  5144.1  240.35
  5176.7  242.13  5191.1  242.91  5223.5  245.43  5224.1  245.48  5239.6  246.65
  5239.7  246.68  5259.7  252.05  5269.7  253.15  5289.7  253.55  5309.7  255.05
  5312.2  255.15
BR D #Mann= 3
 4716.40   0.154    4963   0.052  5038.8   0.154
BR D Banks=4963.00,5038.80

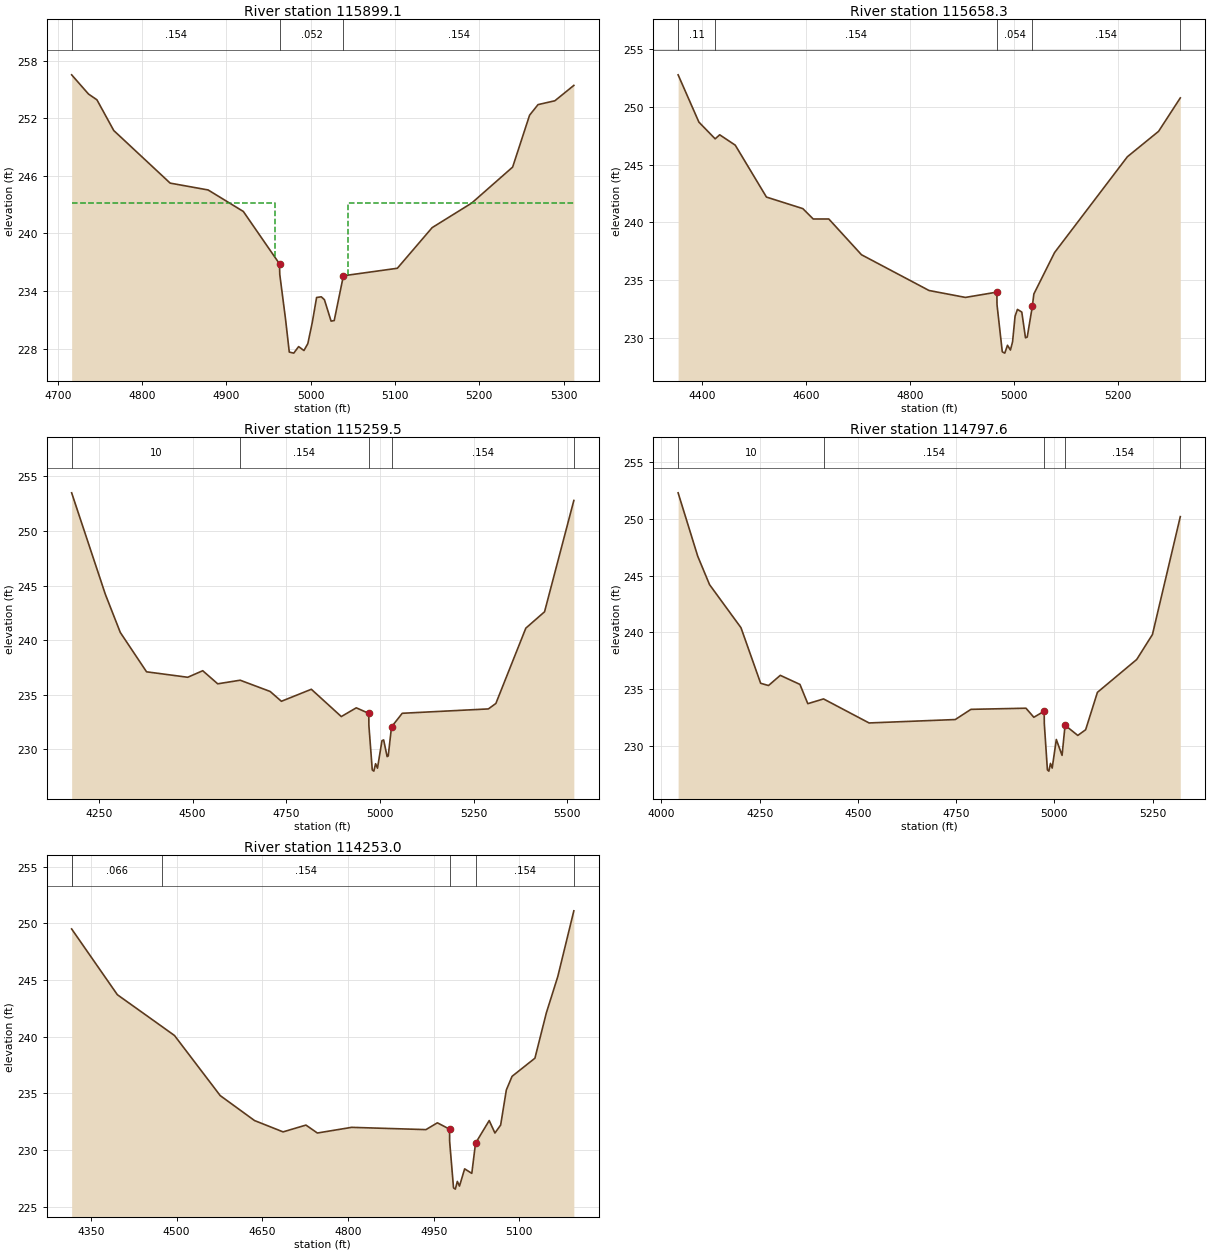
Type RM Length L Ch R = 1 ,115899.1,240.8,240.8,240.8
BEGIN DESCRIPTION:
Downstream Section of Bridge/Culvert/Weir
END DESCRIPTION:
#Sta/Elev= 30
  4716.4  256.51  4736.4  254.51  4746.4  253.91  4766.4  250.71  4833.3  245.24
  4878.3  244.53  4920.1  242.29    4963  236.84  4963.3  235.75  4970.1  231.13
  4974.6  227.66  4979.9  227.55  4985.7  228.23    4992  227.82  4996.6  228.54
  5001.9  230.75    5007  233.34  5012.6  233.41  5016.3  233.11  5024.2  230.88
  5027.9  230.94  5038.8   235.6  5102.8  236.38  5144.1  240.61  5191.1  243.17
  5239.6  246.91  5259.7  252.31  5269.7  253.41  5289.7  253.81  5312.2  255.41
#Mann= 3 , 1 , 0
 4716.40   0.154       0    4963   0.052       0  5038.8   0.154       0
#XS Ineff= 2 , 0
       0    4958   243.2    5044       0   243.2
Bank Sta=4963.00,5038.80
Exp/Cntr=0.5,0.3

Type RM Length L Ch R = 1 ,115658.3,398.8,398.8,398.8
BEGIN DESCRIPTION:
Cross Section Moccasin Creek 45.0
END DESCRIPTION:
#Sta/Elev= 30
  4353.3   252.8  4393.3   248.7  4424.6  247.25  4433.3   247.6  4463.3   246.7
  4523.3   242.2  4593.3   241.2  4613.3   240.3  4643.3   240.3  4706.2   237.2
  4836.2   234.1  4906.2   233.5  4966.7  233.96 4966.97  232.87 4977.14  228.78
 4981.91  228.67 4987.13  229.35  4992.8  228.94 4996.94  229.66 5001.71  231.87
  5006.3  232.46 5014.67  232.23 5021.78     230 5025.11  230.06 5034.92  232.72
  5037.9   233.8  5077.9   237.4  5217.9   245.7  5277.9   247.9  5319.7   250.8
#Mann= 6 , 1 , 0
 4353.30    0.22       0  4353.3    0.11       0  4424.6   0.154       0
  4966.7   0.054       0 5034.92   0.154       0  5319.7    0.22       0
Bank Sta=4966.70,5034.92
Exp/Cntr=0.3,0.1

Type RM Length L Ch R = 1 ,115259.5,461.9,461.9,461.9
BEGIN DESCRIPTION:
Cross Section Moccasin Creek 44.0
END DESCRIPTION:
#Sta/Elev= 30
    4177   253.5    4267   244.2    4307   240.7    4377   237.1    4487   236.6
    4527   237.2    4567     236    4627  236.33    4707   235.3    4737   234.4
    4817   235.5    4897     233    4937   233.8  4970.4  233.29 4970.64   232.2
 4979.68  228.11 4983.92     228 4988.56  228.68  4993.6  228.27  5005.6  230.79
 5010.08  230.86 5019.36  229.33 5022.32  229.39 5031.04  232.05  5059.7   233.3
  5289.7   233.7  5309.7   234.2  5389.7   241.1  5439.7   242.6  5517.9   252.8
#Mann= 5 , 1 , 0
 4177.00      10       0    4627   0.154       0  4970.4   0.055       0
 5031.04   0.154       0  5517.9    0.22       0
Bank Sta=4970.40,5031.04
Exp/Cntr=0.3,0.1

Type RM Length L Ch R = 1 ,114797.6,544.6,544.6,544.6
BEGIN DESCRIPTION:
Cross Section Moccasin Creek 43.0
END DESCRIPTION:
#Sta/Elev= 30
  4042.5   252.3  4092.5   246.7  4122.5   244.2  4202.5   240.4  4252.5   235.5
  4272.5   235.3  4302.5   236.2  4352.5   235.4  4372.5   233.7  4412.5  234.12
  4528.4     232  4747.7   232.3  4787.7   233.2  4927.7   233.3  4947.7   232.5
  4974.1  233.04 4974.31  231.95 4982.22  227.86 4985.93  227.75 4989.99  228.43
  4994.4  228.02  5004.9  230.54 5019.53  229.14 5027.16   231.8  5059.5   230.9
  5079.5   231.4  5109.5   234.7  5209.5   237.6  5249.5   239.8  5320.4   250.2
#Mann= 5 , 1 , 0
 4042.50      10       0  4412.5   0.154       0  4974.1   0.055       0
 5027.16   0.154       0  5320.4    0.22       0
Bank Sta=4974.10,5027.16
Exp/Cntr=0.3,0.1

Type RM Length L Ch R = 1 ,114253.0,527,527,527
BEGIN DESCRIPTION:
Cross Section Moccasin Creek 42.5
END DESCRIPTION:
#Sta/Elev= 30
  4316.5   249.5  4396.5   243.7  4474.1  240.91  4496.5   240.1  4576.5   234.8
  4636.5   232.6  4686.5   231.6  4726.5   232.2  4746.5   231.5  4806.5     232
  4936.5   231.8  4956.5   232.4  4977.8  231.84 4977.98  230.75 4984.76  226.66
 4987.94  226.55 4991.42  227.23  4995.2  226.82  5004.2  228.34 5016.74  227.94
 5023.28   230.6  5047.2   232.6  5057.2   231.5  5067.2   232.2  5077.2   235.3
  5087.2   236.5  5127.2   238.1  5147.2   242.1  5167.2   245.3  5195.3   251.1
#Mann= 6 , 1 , 0
 4316.50    0.22       0  4316.5   0.066       0  4474.1   0.154       0
  4977.8   0.055       0 5023.28   0.154       0  5195.3    0.22       0
Bank Sta=4977.80,5023.28
Exp/Cntr=0.3,0.1