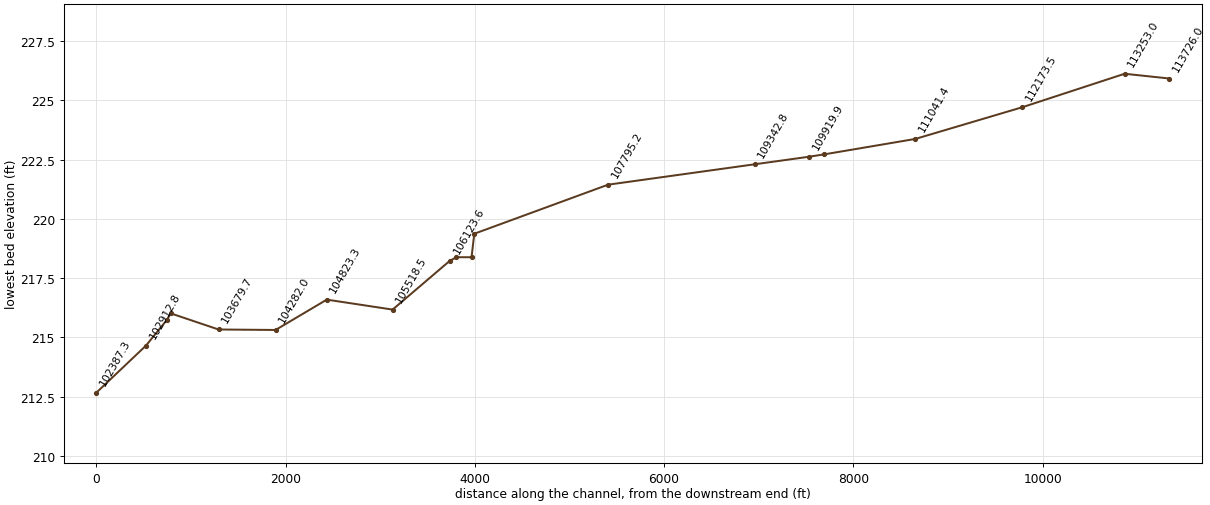
HEC-RAS study Moccasin_Creek_FINAL.prj: Moccasin Creek - Detail Study

--- Moccasin_Creek_FINAL.g01 (geometry) --- (continued)

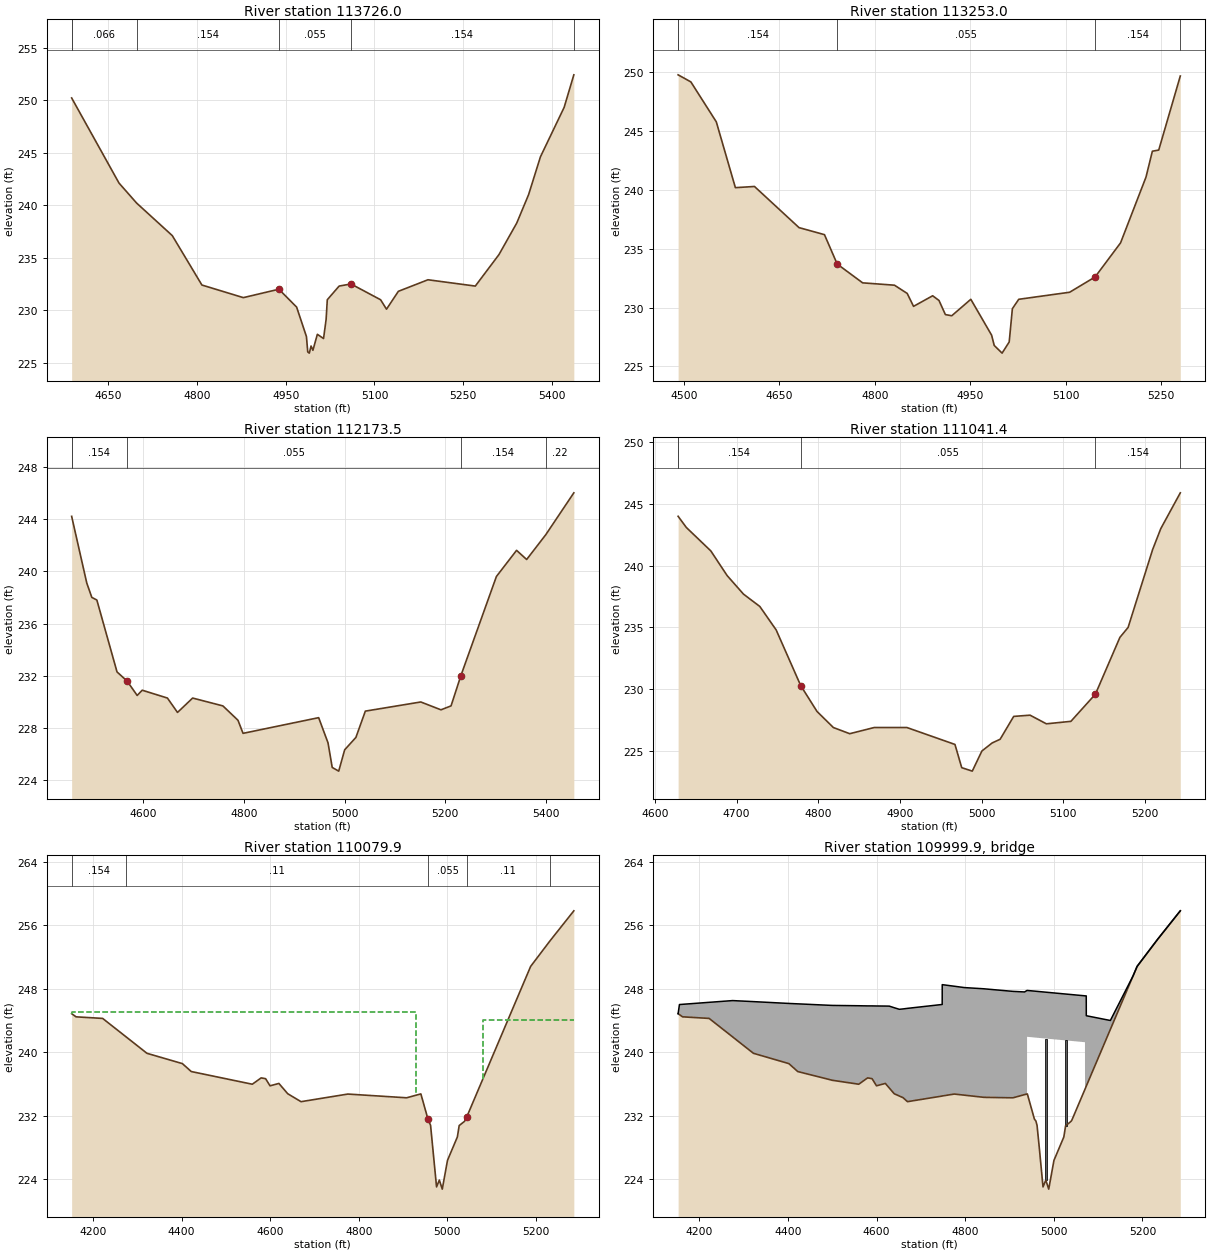
Type RM Length L Ch R = 1 ,113726.0,473,473,473
BEGIN DESCRIPTION:
Cross Section Moccasin Creek 42.0 (End of Bunn Lake)
END DESCRIPTION:
#Sta/Elev= 30
  4588.5   250.2  4668.5   242.1  4698.2   240.2  4758.5   237.1  4808.5   232.4
  4878.5   231.2  4938.5     232  4968.5   230.3 4985.05   227.5  4987.3  226.03
 4989.95  225.92 4992.85   226.6    4996  226.19  5003.5  227.71 5013.95  227.31
  5018.3  229.13  5020.3     231  5040.3   232.3  5060.3   232.5  5110.3     231
  5120.3   230.1  5140.3   231.8  5190.3   232.9  5270.3   232.3  5310.3   235.3
  5340.3   238.3  5360.3     241  5380.3   244.6  5420.3   249.3  5436.7   252.4
#Mann= 6 , 1 , 0
 4588.50    0.22       0  4588.5   0.066       0  4698.2   0.154       0
  4938.5   0.055       0  5060.3   0.154       0  5436.7    0.22       0
Bank Sta=4938.50,5060.30
Exp/Cntr=0.3,0.1

Type RM Length L Ch R = 1 ,113253.0,1079.5,1079.5,1079.5
BEGIN DESCRIPTION:
Cross Section Moccasin Creek 41.0 (Bunn Lake)
END DESCRIPTION:
#Sta/Elev= 30
    4491   249.8    4511   249.2    4551   245.8    4581   240.2    4611   240.3
    4681   236.8    4721   236.2    4741   233.7    4781   232.1    4831   231.9
    4851   231.2    4861   230.1    4891     231    4901   230.6    4911   229.4
    4921   229.3    4951   230.7 4983.65  227.65  4987.8  226.77 5000.15  226.12
  5011.3  227.07  5016.3   229.9  5026.3   230.7  5106.3   231.3  5146.3   232.6
  5186.3   235.5  5226.3   241.1  5236.3   243.3  5246.3   243.4  5280.2   249.7
#Mann= 5 , 1 , 0
 4491.00    0.22       0    4491   0.154       0    4741   0.055       0
  5146.3   0.154       0  5280.2    0.22       0
Bank Sta=4741.00,5146.30
Exp/Cntr=0.3,0.1

Type RM Length L Ch R = 1 ,112173.5,1132.1,1132.1,1132.1
BEGIN DESCRIPTION:
Cross Section Moccasin Creek 39.0 (Bunn Lake)
END DESCRIPTION:
#Sta/Elev= 30
  4458.7   244.2  4488.7   239.1  4498.7     238  4508.7   237.8  4548.7   232.3
  4568.7   231.6  4588.7   230.5  4598.7   230.9  4648.7   230.3  4668.7   229.2
  4698.7   230.3  4758.7   229.7  4788.7   228.6  4798.7   227.6  4948.7   228.8
  4967.3  226.87  4975.6  224.99  4988.5  224.71  5000.3  226.34  5022.6  227.29
  5041.3   229.3  5151.3     230  5191.3   229.4  5211.3   229.7  5230.7     232
  5301.3   239.6  5341.3   241.6  5361.3   240.9  5399.3   242.8  5454.9     246
#Mann= 5 , 1 , 0
 4458.70    0.22       0  4458.7   0.154       0  4568.7   0.055       0
  5230.7   0.154       0  5399.3    0.22       0
Bank Sta=4568.70,5230.70
Exp/Cntr=0.3,0.1

Type RM Length L Ch R = 1 ,111041.4,961.5,961.5,961.5
BEGIN DESCRIPTION:
Cross Section Moccasin Creek 37.0 (Bunn Lake)
END DESCRIPTION:
#Sta/Elev= 29
  4628.5     244  4638.5   243.1  4668.5   241.2  4688.5   239.2  4708.5   237.7
  4728.5   236.7  4748.5   234.8  4778.5   230.3  4798.5   228.2  4818.5   226.9
  4838.5   226.4  4868.5   226.9  4908.5   226.9  4967.3  225.53  4975.6  223.65
  4988.5  223.37  5000.3     225  5012.8  225.65  5022.6  225.95  5039.2   227.8
  5059.2   227.9  5079.2   227.2  5109.2   227.4  5139.2   229.6  5169.2   234.2
  5179.2     235  5209.2   241.3  5219.2     243  5243.1   245.9
#Mann= 5 , 1 , 0
 4628.50    0.22       0  4628.5   0.154       0  4778.5   0.055       0
  5139.2   0.154       0  5243.1    0.22       0
Bank Sta=4778.50,5139.20
Exp/Cntr=0.5,0.3

Type RM Length L Ch R = 1 ,110079.9,160,160,160
BEGIN DESCRIPTION:
Upstream Section of Bridge/Culvert/Weir
END DESCRIPTION:
#Sta/Elev= 30
  4151.9  244.85  4161.9  244.45  4221.9  244.25  4274.9  241.92  4321.9  239.85
  4401.9  238.55  4421.9  237.55  4559.7  235.95  4579.7  236.75  4589.7  236.65
  4599.7  235.75  4619.7  236.05  4639.7  234.75  4669.7  233.75  4775.3  234.71
  4908.1  234.24  4940.2  234.73  4956.2  231.55  4962.1  230.77  4975.6     223
  4981.9  223.86  4988.5  222.72  5000.3  226.35  5022.6   229.3  5026.7  230.74
  5038.8  231.27  5044.2  231.88    5188  250.81  5231.1  253.99  5285.5  257.82
#Mann= 5 , 1 , 0
 4151.90   0.154       0  4274.9    0.11       0  4956.2   0.055       0
  5044.2    0.11       0  5231.1   0.154       0
#XS Ineff= 2 , 0
       0    4929     245    5080       0   244.1
Bank Sta=4956.20,5044.20
Exp/Cntr=0.5,0.3

Type RM Length L Ch R = 3 ,109999.9,,,
BEGIN DESCRIPTION:
US Hwy 64
Structure ID: WK_MCCR4, WK_MCCR3
END DESCRIPTION:
Bridge Culvert--1,0,-1,-1, 0
Deck Dist Width WeirC Skew NumUp NumDn MinLoCord MaxHiCord MaxSubmerge Is_Ogee
10,140,2.6,, 37, 37,,,0.95,0,1,1,,
  4151.9  4154.9  4161.9  4221.9  4274.9  4321.9  4401.9  4421.9  4499.7  4559.7
  4579.7  4589.7  4599.7  4619.7  4628.6  4639.7  4651.3  4659.7  4669.7 4747.99
  4748.1  4775.3  4798.1  4841.6  4908.1    4934 4939.51  4939.6 5070.29  5070.4
  5073.2 5073.31  5127.6  5179.1    5188  5234.6  5285.5
  244.85     246  246.03  246.28   246.5  246.37  246.14  246.09  245.89  245.85
  245.83  245.83  245.82  245.81   245.8   245.6   245.4  245.45  245.52  246.01
  248.51  248.31  248.14  247.99  247.66  247.59  247.78  247.78   247.1   247.1
  247.09  244.59  243.99  249.64  250.81  254.25  257.82
  244.85  244.73  244.45  244.25  241.92  239.85  238.55  237.55  236.45  235.95
  236.75  236.65  235.75  236.05  235.47  234.75  234.46  234.25  233.75  234.46
  234.46  234.71  234.57   234.3  234.24  234.64  234.72  241.93  241.25  235.33
   235.7  235.71  242.86  249.64  250.81  254.25  257.82
  4151.9  4154.9  4161.9  4221.9  4274.9  4321.9  4401.9  4421.9  4499.7  4559.7
  4579.7  4589.7  4599.7  4619.7  4628.6  4639.7  4651.3  4659.7  4669.7 4747.99
  4748.1  4775.3  4798.1  4841.6  4908.1    4934 4939.51  4939.6 5070.29  5070.4
  5073.2 5073.31  5127.6  5179.1    5188  5234.6  5285.5
   244.8     246  246.03  246.28   246.5  246.37  246.14  246.09  245.89  245.85
  245.83  245.83  245.82  245.81   245.8   245.6   245.4  245.45  245.52  246.01
  248.51  248.31  248.14  247.99  247.66  247.59  247.78  247.78   247.1   247.1
  247.09  244.59  243.99   249.6  250.77  254.21  257.77
  244.76  244.64  244.36  244.16  241.83  239.76  238.46  237.46  236.36  235.86
  236.66  236.56  235.66  235.96  235.38  234.66  234.37  234.16  233.66  234.37
  234.37  234.62  234.48  234.21  234.15  234.55  234.63  241.84  241.16  235.24
  235.61  235.62  242.77  249.55  250.72  254.16  257.73
Pier Skew, UpSta & Num, DnSta & Num=,4981.9, 2 ,4981.9, 2 , 0 , 0 , 0 ,,
       4       4
  222.51  242.72
       4       4
  222.42  242.63
Pier Skew, UpSta & Num, DnSta & Num=,5026.7, 2 ,5026.7, 2 , 0 , 0 , 0 ,,
       4       4
  229.04  242.49
       4       4
  228.95   242.4
BR Coef= 1 , 1 , 0 ,1.25, 0 ,,,0.8,0,2,0,
Wspro=,,,, 1 ,,,, 0 ,,,, 0 ,,,,-1 ,-1 ,-1 , 0 , 0 , 0 , 0 , 0
BC Design=,, 0 ,, 0 ,,,,,,
BR U #Sta/Elev= 67
  4151.9  244.85  4154.9  244.73  4161.9  244.45  4221.9  244.25  4274.9  241.92
  4321.9  239.85  4401.9  238.55  4421.9  237.55  4488.6  236.61  4499.7  236.45
  4559.7  235.95  4579.7  236.75  4589.7  236.65  4599.7  235.75  4619.7  236.05
  4628.6  235.47  4639.7  234.75  4651.3  234.46  4659.7  234.25  4669.7  233.75
 4747.99  234.46  4748.1  234.46 4748.21  234.46  4748.5  234.47  4775.3  234.71
  4798.1  234.57  4841.6   234.3  4847.5  234.29  4902.8  234.24  4908.1  234.24
    4934  234.64  4939.4  234.72 4939.51  234.72  4939.6  234.72  4939.7  234.72
  4940.2  234.73  4956.2  231.55  4959.5  231.31  4962.1  230.77  4967.3  227.88
  4975.6     223  4981.9  223.86  4988.5  222.72  5000.3  226.35  5012.8     228
  5022.6   229.3  5026.7  230.74  5032.7  230.98  5038.8  231.27  5040.5   231.4
  5044.2  231.88  5070.2   235.3 5070.29  235.31  5070.4  235.33  5070.5  235.34
 5073.09  235.68  5073.2   235.7 5073.31  235.71  5078.9  236.45  5127.6  242.86
  5179.1  249.64    5188  250.81  5227.9  253.76  5231.1  253.99  5234.6  254.25
  5282.3   257.6  5285.5  257.82
BR U #Mann= 5
 4151.90   0.154  4274.9    0.11  4956.2   0.055  5044.2    0.11  5231.1   0.154
BR U Banks=4956.20,5044.20
BR D #Sta/Elev= 67
  4151.9  244.76  4154.9  244.64  4161.9  244.36  4221.9  244.16  4274.9  241.83
  4321.9  239.76  4401.9  238.46  4421.9  237.46  4488.6  236.52  4499.7  236.36
  4559.7  235.86  4579.7  236.66  4589.7  236.56  4599.7  235.66  4619.7  235.96
  4628.6  235.38  4639.7  234.66  4651.3  234.37  4659.7  234.16  4669.7  233.66
 4747.99  234.37  4748.1  234.37 4748.21  234.37  4748.5  234.38  4775.3  234.62
  4798.1  234.48  4841.6  234.21  4847.5   234.2  4902.8  234.15  4908.1  234.15
    4934  234.55  4939.4  234.63 4939.51  234.63  4939.6  234.63  4939.7  234.63
  4940.2  234.64  4956.2  231.46  4959.5  231.22  4962.1  230.68  4967.3  227.79
  4975.6  222.91  4981.9  223.77  4988.5  222.63  5000.3  226.26  5012.8  227.91
  5022.6  229.21  5026.7  230.65  5032.7  230.89  5038.8  231.18  5040.5  231.31
  5044.2  231.79  5070.2  235.21 5070.29  235.22  5070.4  235.24  5070.5  235.25
 5073.09  235.59  5073.2  235.61 5073.31  235.62  5078.9  236.36  5127.6  242.77
  5179.1  249.55    5188  250.72  5227.9  253.67  5231.1   253.9  5234.6  254.16
  5282.3  257.51  5285.5  257.73
BR D #Mann= 5
 4151.90   0.154  4274.9    0.11  4956.2   0.055  5044.2    0.11  5231.1   0.154
BR D Banks=4956.20,5044.20

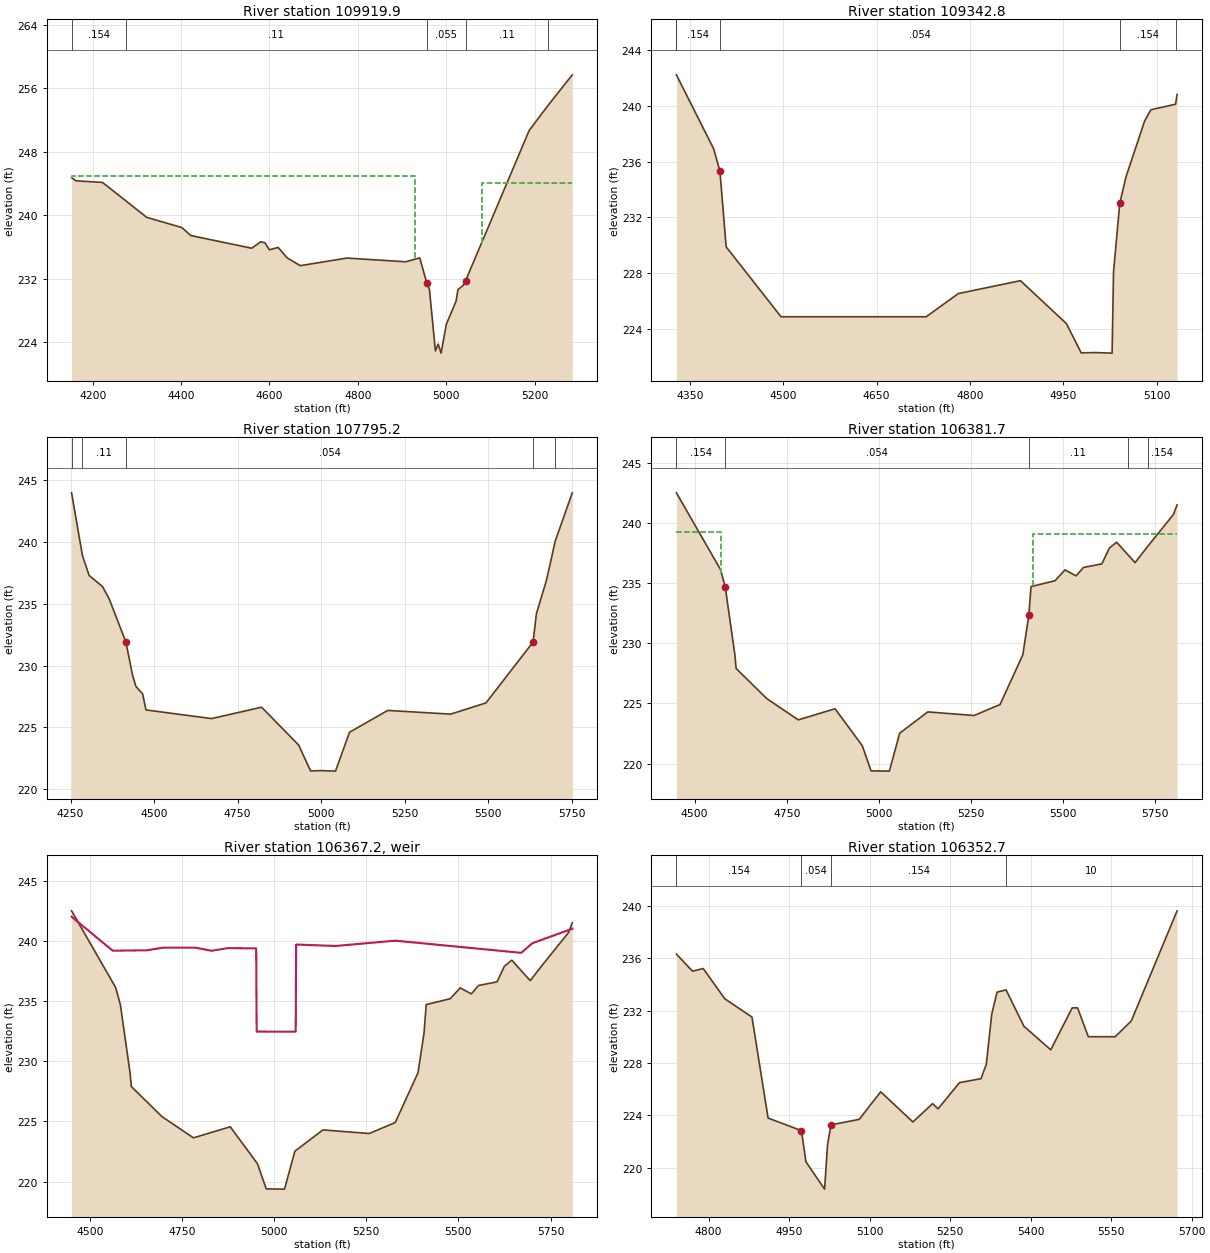
Type RM Length L Ch R = 1 ,109919.9,577.1,577.1,577.1
BEGIN DESCRIPTION:
Downstream Section of Bridge/Culvert/Weir
END DESCRIPTION:
#Sta/Elev= 30
  4151.9  244.75  4161.9  244.35  4221.9  244.15  4274.9  241.82  4321.9  239.75
  4401.9  238.45  4421.9  237.45  4559.7  235.85  4579.7  236.65  4589.7  236.55
  4599.7  235.65  4619.7  235.95  4639.7  234.65  4669.7  233.65  4775.3  234.61
  4908.1  234.14  4940.2  234.63  4956.2  231.45  4962.1  230.67  4975.6   222.9
  4981.9  223.76  4988.5  222.62  5000.3  226.25  5022.6   229.2  5026.7  230.64
  5038.8  231.17  5044.2  231.78    5188  250.71  5231.1  253.89  5285.5  257.72
#Mann= 5 , 1 , 0
 4151.90   0.154       0  4274.9    0.11       0  4956.2   0.055       0
  5044.2    0.11       0  5231.1   0.154       0
#XS Ineff= 2 , 0
       0    4929     245    5080       0   244.1
Bank Sta=4956.20,5044.20
Exp/Cntr=0.5,0.3

Type RM Length L Ch R = 1 ,109342.8,1547.6,1547.6,1547.6
BEGIN DESCRIPTION:
Cross Section Moccasin Creek 34.0 (Bunn Lake)
END DESCRIPTION:
#Sta/Elev= 19
    4328   242.2    4388   236.9    4398   235.3    4408   229.9  4496.2   224.9
  4729.6   224.9  4781.4  226.56  4881.2  227.48  4955.1  224.41  4978.8  222.32
  5001.2  222.34  5028.5   222.3  5030.8   228.1  5040.8     233  5050.8   234.9
  5080.8   238.9  5090.8   239.7  5130.6   240.1    5133   240.8
#Mann= 5 , 1 , 0
 4328.00   0.154       0    4328   0.154       0    4398   0.054       0
  5040.8   0.154       0  5130.6   0.154       0
Bank Sta=4398.00,5040.80
Exp/Cntr=0.3,0.1

Type RM Length L Ch R = 1 ,107795.2,1413.5,1413.5,1413.5
BEGIN DESCRIPTION:
Cross Section Moccasin Creek 31.0 (Bunn Lake)
END DESCRIPTION:
#Sta/Elev= 25
  4253.2     244  4285.8   238.9  4305.8   237.3  4345.8   236.4  4365.8   235.4
  4415.8   231.9  4435.8   229.2  4445.8   228.3  4465.8   227.7  4475.8   226.4
  4672.1   225.7  4821.8  226.62 4932.65  223.55  4968.2  221.46  5001.8  221.48
 5042.75  221.44 5084.75  224.59 5199.05  226.36  5387.3  226.06 5493.05  226.97
  5633.9   231.9  5643.9   234.2  5673.9   236.9  5700.4   240.1  5751.2     244
#Mann= 5 , 1 , 0
 4253.20   0.154       0  4285.8    0.11       0  4415.8   0.054       0
  5633.9    0.11       0  5700.4   0.154       0
Bank Sta=4415.80,5633.90
Exp/Cntr=0.5,0.3

Type RM Length L Ch R = 1 ,106381.7,29,29,29
BEGIN DESCRIPTION:
Upstream Section of Bridge/Culvert/Weir
END DESCRIPTION:
#Sta/Elev= 30
  4450.8  242.49  4570.4  236.12  4583.3  234.67  4609.6  228.99  4612.8   227.9
  4695.8   225.4  4781.4  223.63  4881.2  224.55  4955.1  221.48  4978.8  219.39
  5028.5  219.37  5056.5  222.52  5132.7  224.29  5258.2  223.99  5328.7   224.9
  5390.5  229.03  5406.8  232.32  5412.8   234.7    5478  235.19    5505  236.09
    5535  235.59    5555  236.29    5605  236.59    5625  237.89    5645  238.39
  5675.5  237.35    5695  236.69    5729  238.03    5799  240.69    5809  241.49
#Mann= 5 , 1 , 0
 4450.80   0.154       0  4583.3   0.054       0  5406.8    0.11       0
  5675.5   0.154       0    5729   0.154       0
#XS Ineff= 2 , 0
       0    4573   239.2    5417       0   239.1
Bank Sta=4583.30,5406.80
Exp/Cntr=0.5,0.3

Type RM Length L Ch R = 5 ,106367.2,,,
BEGIN DESCRIPTION:
DAM u/s of NC 39
Structure ID: FRMCCR2A
END DESCRIPTION:
#Inline Weir SE= 17
  4450.8     242  4562.3  239.18  4655.3  239.21  4699.1  239.43  4786.6  239.43
  4830.8  239.17  4874.3  239.39  4951.6  239.37  4952.8  232.46  5056.5  232.45
  5058.8  232.45  5059.9  239.69  5166.7  239.57  5329.2  240.01  5670.7     239
  5700.7   239.8    5809     241
IW Dist,WD,Coef,Skew,MaxSub,Min_El,Is_Ogee,SpillHt,DesHd
10.0,9.0,3.0,,0.95,, 0 ,,,1.9,1.9,

Type RM Length L Ch R = 1 ,106352.7,159.1,159.1,159.1
BEGIN DESCRIPTION:
Cross Section FIELD_DS
Located At: DAM US NC 39
END DESCRIPTION:
#Sta/Elev= 30
  4740.1   236.3  4770.1     235  4790.1   235.2  4830.1   232.9  4880.9   231.5
  4910.9   223.8 4973.05  222.84 4981.45  220.46 5016.17  218.38  5021.7  221.78
    5028  223.28  5080.7   223.7  5120.7   225.8  5180.7   223.5  5217.5   224.9
  5227.5   224.5  5267.5   226.5  5307.5   226.8  5317.5   227.9  5327.5   231.7
  5337.5   233.4  5354.3  233.57  5387.5   230.8  5437.5     229  5477.5   232.2
  5487.5   232.2  5507.5     230  5557.5     230  5587.5   231.2  5672.9   239.6
#Mann= 4 , 1 , 0
 4740.10   0.154       0 4973.05   0.054       0    5028   0.154       0
  5354.3      10       0
Bank Sta=4973.05,5028.00
Exp/Cntr=0.5,0.3

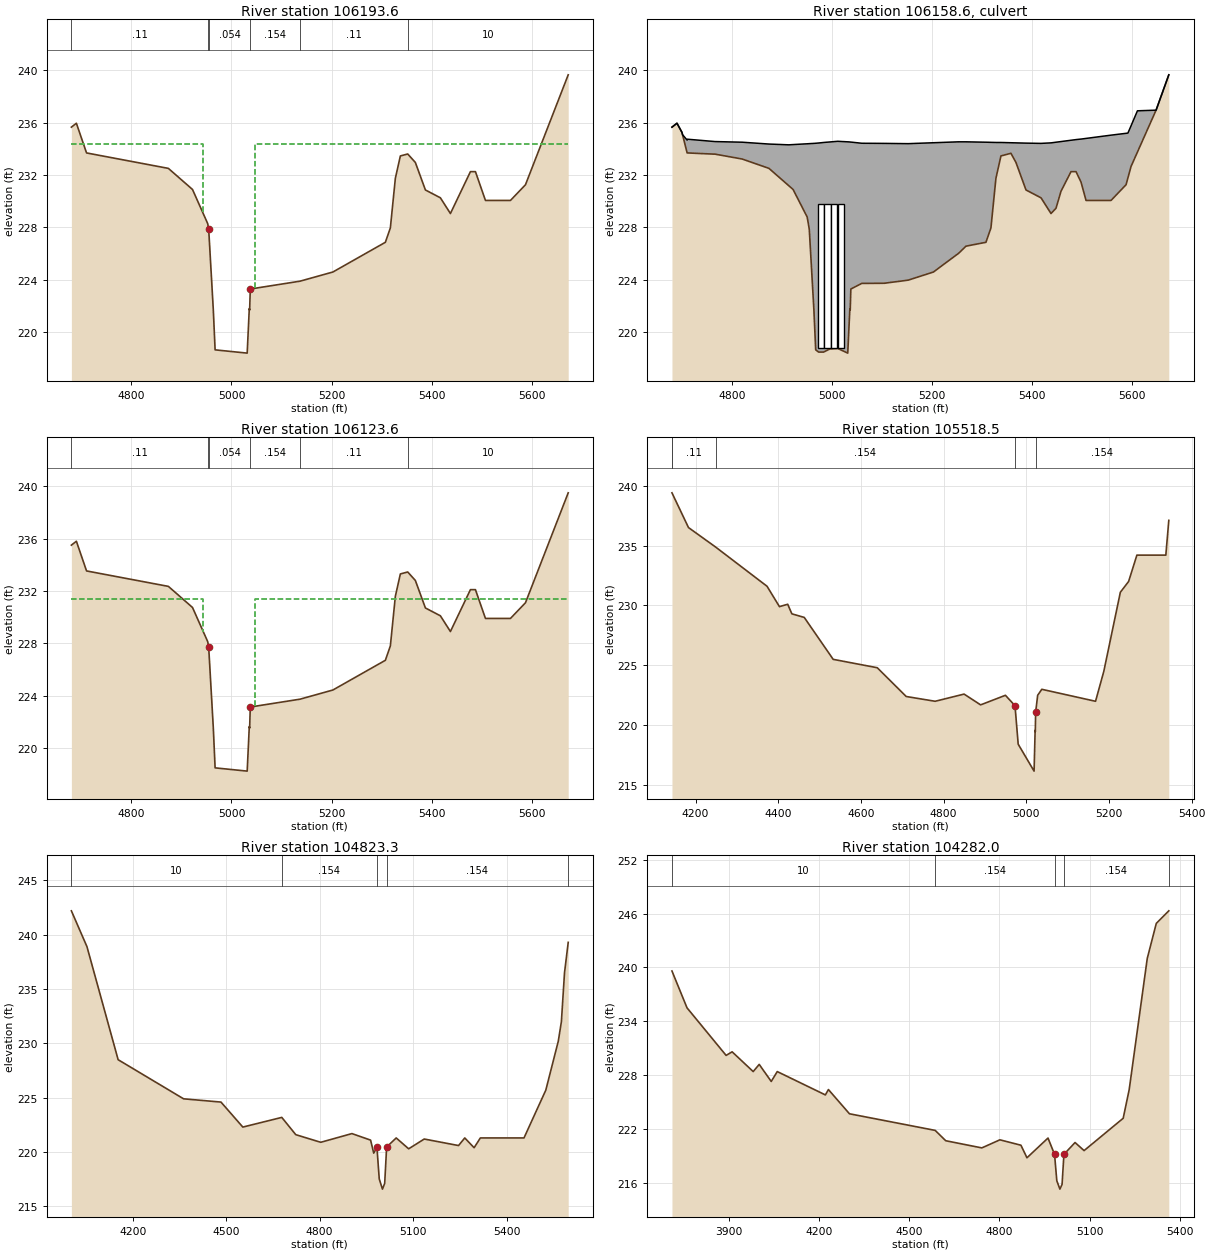
Type RM Length L Ch R = 1 ,106193.6,70,70,70
BEGIN DESCRIPTION:
Upstream Section of Bridge/Culvert/Weir
END DESCRIPTION:
#Sta/Elev= 30
  4680.1  235.65  4690.1  235.95  4710.4  233.68  4873.9   232.5  4922.1  230.89
  4952.6  228.27  4954.5  227.84  4963.7  221.69  4967.3  218.63  5031.4  218.38
  5035.6  221.78  5036.3  221.67  5037.6  223.28  5137.1  223.88  5202.7  224.58
  5307.5  226.85  5317.5  227.95  5327.5  231.75  5337.5  233.45  5352.2   233.6
  5367.5  232.95  5387.5  230.85  5417.5  230.25  5437.5  229.05  5477.5  232.25
  5487.5  232.25  5507.5  230.05  5557.5  230.05  5587.5  231.25  5672.9  239.65
#Mann= 6 , 1 , 0
 4680.10    0.11       0  4952.6   0.154       0  4954.5   0.054       0
  5037.6   0.154       0  5137.1    0.11       0  5352.2      10       0
#XS Ineff= 2 , 0
       0    4944   234.4    5048       0   234.4
Bank Sta=4954.50,5037.60
Exp/Cntr=0.5,0.3

Type RM Length L Ch R = 2 ,106158.6,,,
BEGIN DESCRIPTION:
NC 39
Structure ID: FRMCCR2
END DESCRIPTION:
Bridge Culvert--1,0,-1,-1, 0
Deck Dist Width WeirC Skew NumUp NumDn MinLoCord MaxHiCord MaxSubmerge Is_Ogee
10,50,3,, 51, 51,,,0.95,0,1,1,,
  4680.1  4690.1  4700.1  4701.2  4710.4  4711.1  4765.8  4820.7  4873.9  4913.7
  4922.1  4950.3  4954.5  4963.7  4967.3  4973.2  4983.2  4995.7  5011.2  5031.4
  5035.6  5036.3  5037.6  5059.5  5104.5  5152.3  5202.7    5253  5267.5  5307.5
  5317.5  5327.5  5337.5  5357.5  5367.5  5387.5  5417.5  5437.5  5447.5  5457.5
  5477.5  5487.5  5497.5  5507.5  5557.5  5587.5  5591.2  5597.5  5610.2  5647.5
  5672.9
  235.65  235.95  235.25  235.08  234.66  234.73  234.55   234.5  234.36   234.3
  234.32  234.38  234.39  234.41  234.42  234.44  234.48  234.52  234.57  234.53
  234.52  234.51  234.51  234.42  234.41  234.39  234.46  234.53  234.53   234.5
  234.49  234.48  234.48  234.46  234.45  234.43  234.41  234.45   234.5  234.55
  234.65   234.7  234.74  234.79  235.04  235.18   235.2  235.76   236.9  236.95
  239.65
  235.65  235.95  235.25  235.08  233.68  233.68  233.59  233.21   232.5  231.17
  230.89  228.78  227.84  221.69  218.63  218.46  218.46   218.7  218.74  218.38
  221.78  221.67  223.28  223.71  223.72  223.96  224.58  226.01  226.55  226.85
  227.95  231.75  233.45  233.65  232.95  230.85  230.25  229.05  229.45  230.75
  232.25  232.25  231.45  230.05  230.05  231.25  231.77  232.65  233.74  236.95
  239.65
  4680.1  4690.1  4700.1  4701.2  4710.4  4711.1  4765.8  4820.7  4873.9  4913.7
  4922.1  4950.3  4954.5  4963.7  4967.3  4973.2  4983.2  4995.7  5011.2  5031.4
  5035.6  5036.3  5037.6  5059.5  5104.5  5152.3  5202.7    5253  5267.5  5307.5
  5317.5  5327.5  5337.5  5357.5  5367.5  5387.5  5417.5  5437.5  5447.5  5457.5
  5477.5  5487.5  5497.5  5507.5  5557.5  5587.5  5591.2  5597.5  5610.2  5647.5
  5672.9
   235.6   235.9   235.2  235.04  234.66  234.73  234.55   234.5  234.36   234.3
  234.32  234.38  234.39  234.41  234.42  234.44  234.48  234.52  234.57  234.53
  234.52  234.51  234.51  234.42  234.41  234.39  234.46  234.53  234.53   234.5
  234.49  234.48  234.48  234.46  234.45  234.43  234.41  234.45   234.5  234.55
  234.65   234.7  234.74  234.79  235.04  235.18   235.2  235.76   236.9   236.9
   239.6
  235.55  235.85  235.15  234.98  233.58  233.58  233.49  233.11   232.4  231.07
  230.79  228.68  227.74  221.59  218.53  218.36  218.36   218.6  218.64  218.28
  221.68  221.57  223.18  223.61  223.62  223.86  224.48  225.91  226.45  226.75
  227.85  231.65  233.35  233.55  232.85  230.75  230.15  228.95  229.35  230.65
  232.15  232.15  231.35  229.95  229.95  231.15  231.67  232.55  233.64  236.85
  239.55
BR Coef= 1 , 0 , 0 ,1.25, 0 ,,,0.8,-1,2,0,
Wspro=,,,, 1 ,,,, 0 ,,,, 0 ,,,,-1 ,-1 ,-1 , 0 , 0 , 0 , 0 , 0
Culvert=2,11.0,13.0,50.0,0.015,0.4,1.0,8,1,218.76,4977.70,218.66,4977.70,Culvert #1  ,0,10
Culvert=2,11.0,13.0,50.0,0.015,0.4,1.0,8,1,218.76,4991.00,218.66,4991.00,Culvert #2  ,0,10
Culvert=2,11.0,13.0,50.0,0.015,0.4,1.0,8,1,218.76,5004.20,218.66,5004.20,Culvert #3  ,0,10
Culvert=2,11.0,13.0,50.0,0.015,0.4,1.0,8,1,218.76,5017.70,218.66,5017.70,Culvert #4  ,0,10
BC Design=,, 0 ,, 0 ,,,,,,
BR U #Sta/Elev= 65
  4680.1  235.65  4690.1  235.95  4700.1  235.25  4701.2  235.08  4710.4  233.68
  4711.1  233.68  4762.9  233.59  4765.8  233.59  4812.4  233.27  4820.7  233.21
  4862.7  232.65  4873.9   232.5  4913.7  231.17  4922.1  230.89  4950.3  228.78
  4952.6  228.27  4954.5  227.84  4963.5  221.82  4963.7  221.69  4967.3  218.63
  4973.2  218.46  4983.2  218.46  4995.7   218.7  5011.2  218.74  5017.9  218.62
  5031.4  218.38  5035.6  221.78  5036.3  221.67  5037.6  223.28  5059.5  223.71
  5069.4  223.71  5104.5  223.72  5120.1   223.8  5137.1  223.88  5152.3  223.96
  5171.1  224.19  5202.7  224.58    5223  225.16    5253  226.01  5267.5  226.55
  5272.3  226.59  5307.5  226.85  5317.5  227.95  5327.5  231.75  5337.5  233.45
  5352.2   233.6  5357.5  233.65  5367.5  232.95  5387.5  230.85  5417.5  230.25
  5426.5  229.71  5437.5  229.05  5447.5  229.45  5457.5  230.75  5477.5  232.25
  5487.5  232.25  5497.5  231.45  5507.5  230.05  5557.5  230.05  5587.5  231.25
  5591.2  231.77  5597.5  232.65  5610.2  233.74  5647.5  236.95  5672.9  239.65
BR U #Mann= 6
 4680.10    0.11  4952.6   0.154  4954.5   0.054  5037.6   0.154  5137.1    0.11
  5352.2      10
BR U Banks=4954.50,5037.60
BR D #Sta/Elev= 65
  4680.1  235.55  4690.1  235.85  4700.1  235.15  4701.2  234.98  4710.4  233.58
  4711.1  233.58  4762.9  233.49  4765.8  233.49  4812.4  233.17  4820.7  233.11
  4862.7  232.55  4873.9   232.4  4913.7  231.07  4922.1  230.79  4950.3  228.68
  4952.6  228.17  4954.5  227.74  4963.5  221.72  4963.7  221.59  4967.3  218.53
  4973.2  218.36  4983.2  218.36  4995.7   218.6  5011.2  218.64  5017.9  218.52
  5031.4  218.28  5035.6  221.68  5036.3  221.57  5037.6  223.18  5059.5  223.61
  5069.4  223.61  5104.5  223.62  5120.1   223.7  5137.1  223.78  5152.3  223.86
  5171.1  224.09  5202.7  224.48    5223  225.06    5253  225.91  5267.5  226.45
  5272.3  226.49  5307.5  226.75  5317.5  227.85  5327.5  231.65  5337.5  233.35
  5352.2   233.5  5357.5  233.55  5367.5  232.85  5387.5  230.75  5417.5  230.15
  5426.5  229.61  5437.5  228.95  5447.5  229.35  5457.5  230.65  5477.5  232.15
  5487.5  232.15  5497.5  231.35  5507.5  229.95  5557.5  229.95  5587.5  231.15
  5591.2  231.67  5597.5  232.55  5610.2  233.64  5647.5  236.85  5672.9  239.55
BR D #Mann= 6
 4680.10    0.11  4952.6   0.154  4954.5   0.054  5037.6   0.154  5137.1    0.11
  5352.2      10
BR D Banks=4954.50,5037.60

Type RM Length L Ch R = 1 ,106123.6,605.1,605.1,605.1
BEGIN DESCRIPTION:
Downstream Section of Bridge/Culvert/Weir
END DESCRIPTION:
#Sta/Elev= 30
  4680.1   235.5  4690.1   235.8  4710.4  233.53  4873.9  232.35  4922.1  230.74
  4952.6  228.12  4954.5  227.69  4963.7  221.54  4967.3  218.48  5031.4  218.23
  5035.6  221.63  5036.3  221.52  5037.6  223.13  5137.1  223.73  5202.7  224.43
  5307.5   226.7  5317.5   227.8  5327.5   231.6  5337.5   233.3  5352.2  233.45
  5367.5   232.8  5387.5   230.7  5417.5   230.1  5437.5   228.9  5477.5   232.1
  5487.5   232.1  5507.5   229.9  5557.5   229.9  5587.5   231.1  5672.9   239.5
#Mann= 6 , 1 , 0
 4680.10    0.11       0  4952.6   0.154       0  4954.5   0.054       0
  5037.6   0.154       0  5137.1    0.11       0  5352.2      10       0
#XS Ineff= 2 , 0
       0    4944   231.4    5048       0   231.4
Bank Sta=4954.50,5037.60
Exp/Cntr=0.5,0.3

Type RM Length L Ch R = 1 ,105518.5,695.2,695.2,695.2
BEGIN DESCRIPTION:
Cross Section Moccasin Creek 28.0
END DESCRIPTION:
#Sta/Elev= 30
  4142.9   239.4  4182.9   236.5  4248.3  234.88  4372.9   231.6  4402.9   229.9
  4422.9   230.1  4432.9   229.3  4462.9     229  4532.9   225.5  4639.5   224.8
  4709.5   222.4  4779.5     222  4849.5   222.6  4889.5   221.7  4949.5   222.5
  4972.7  221.63 4980.38  218.42 5018.84  216.17 5021.36  219.57 5021.78  219.46
 5022.56  221.07  5027.5   222.5  5037.5     223  5167.5     222  5187.5   224.5
  5227.5   231.1  5247.5     232  5267.5   234.2  5337.5   234.2  5344.7   237.1
#Mann= 5 , 1 , 0
 4142.90    0.22       0  4142.9    0.11       0  4248.3   0.154       0
  4972.7   0.054       0 5022.56   0.154       0
Bank Sta=4972.70,5022.56
Exp/Cntr=0.3,0.1

Type RM Length L Ch R = 1 ,104823.3,541.3,541.3,541.3
BEGIN DESCRIPTION:
Cross Section Moccasin Creek 27.0
END DESCRIPTION:
#Sta/Elev= 30
  4003.4   242.2  4053.4   238.9  4153.4   228.5  4363.4   224.9  4483.4   224.6
  4553.4   222.3  4678.4  223.19  4723.4   221.6  4803.4   220.9  4903.4   221.7
  4963.4   221.1  4973.4   219.9  4983.7  220.45  4991.1  217.53  5001.4  216.59
  5008.6  217.12  5014.8  220.46  5045.5   221.3  5085.5   220.3  5135.5   221.2
  5245.5   220.6  5265.5   221.3  5295.5   220.4  5315.5   221.3  5455.5   221.3
  5525.5   225.7  5565.5   230.2  5575.5     232  5585.5   236.5  5597.4   239.3
#Mann= 5 , 1 , 0
 4003.40      10       0  4678.4   0.154       0  4983.7   0.054       0
  5014.8   0.154       0  5597.4    0.22       0
Bank Sta=4983.70,5014.80
Exp/Cntr=0.3,0.1

Type RM Length L Ch R = 1 ,104282.0,602.3,602.3,602.3
BEGIN DESCRIPTION:
Cross Section Moccasin Creek 26.0
END DESCRIPTION:
#Sta/Elev= 30
  3711.9   239.6  3761.9   235.5  3891.9   230.2  3911.9   230.6  3981.9   228.4
  4001.9   229.2  4041.9   227.3  4061.9   228.4  4221.9   225.8  4231.9   226.4
  4301.9   223.7  4586.9  221.85  4621.9   220.7  4741.9   219.9  4801.9   220.8
  4871.9   220.2  4891.9   218.8  4961.9     221  4983.7  219.17  4991.1  216.25
  5001.4  215.31  5008.6  215.84  5014.8  219.18  5051.8   220.5  5081.8   219.6
  5211.8   223.2  5231.8   226.4  5291.8     241  5321.8   244.9  5363.4   246.3
#Mann= 5 , 1 , 0
 3711.90      10       0  4586.9   0.154       0  4983.7   0.054       0
  5014.8   0.154       0  5363.4    0.22       0
Bank Sta=4983.70,5014.80
Exp/Cntr=0.3,0.1

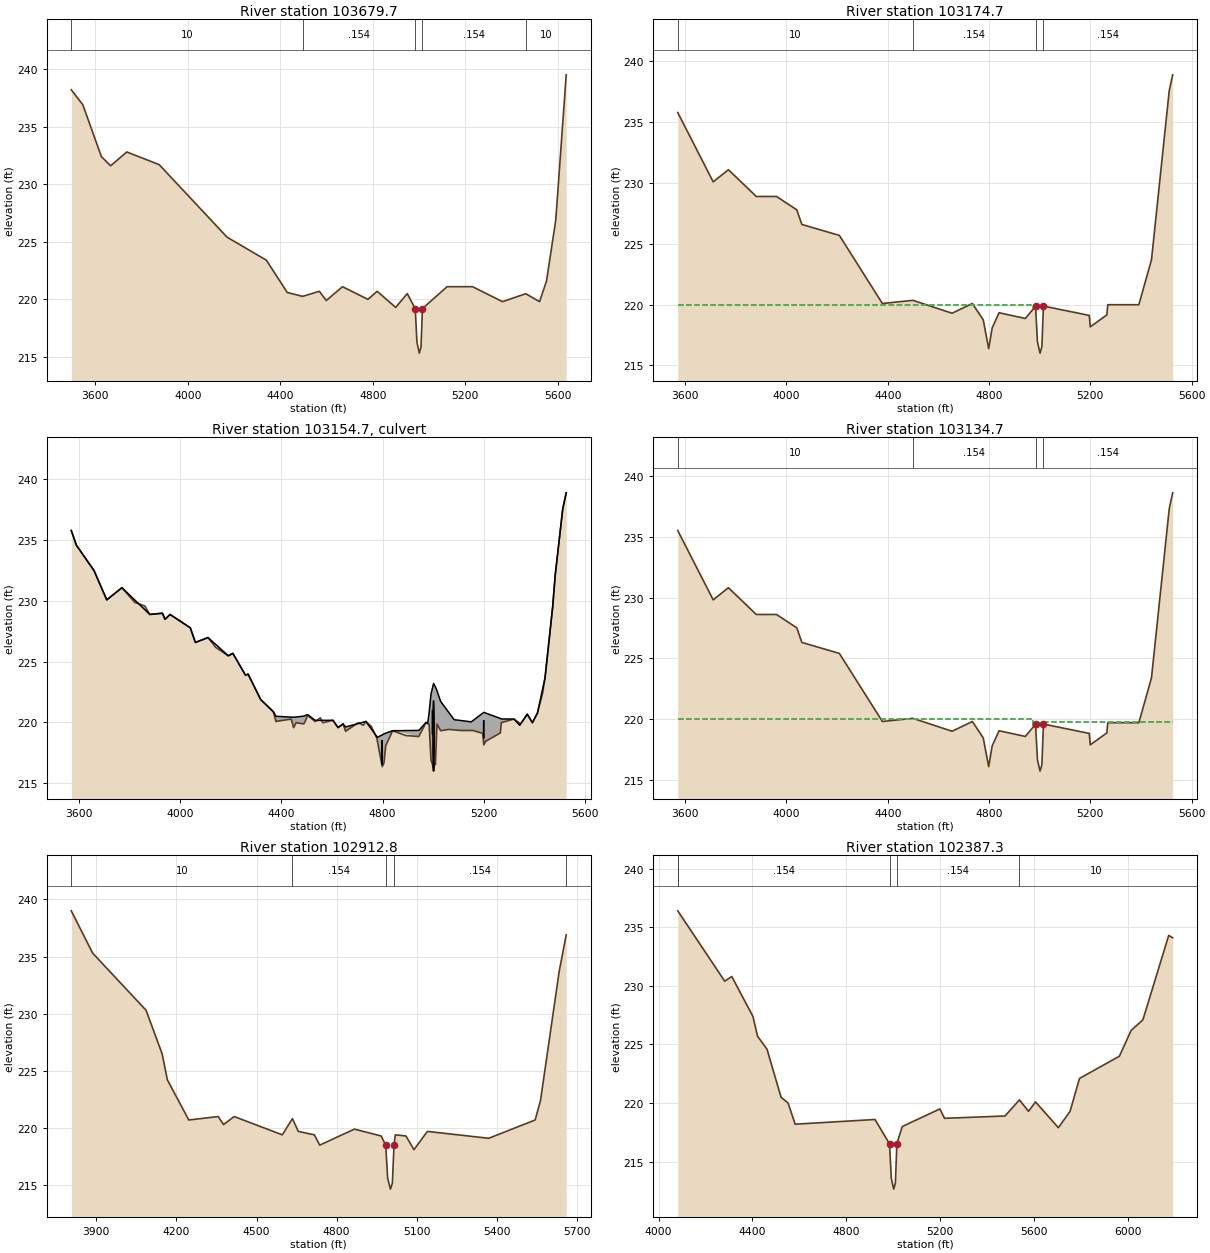
Type RM Length L Ch R = 1 ,103679.7,505,505,505
BEGIN DESCRIPTION:
Cross Section Moccasin Creek 25.0
END DESCRIPTION:
#Sta/Elev= 30
  3496.6   238.2  3546.6   236.9  3626.6   232.4  3666.6   231.6  3736.6   232.8
  3876.6   231.7  4170.2   225.4  4340.2   223.4  4430.2   220.6  4496.6  220.26
  4569.1   220.7  4599.1   219.9  4669.1   221.1  4779.1     220  4819.1   220.7
  4899.1   219.3  4949.1   220.5  4983.7  219.19  4991.1  216.27  5001.4  215.33
  5008.6  215.86  5014.8   219.2  5121.3   221.1  5231.3   221.1  5361.3   219.8
  5461.6  220.49  5521.3   219.8  5551.3   221.6  5591.3   226.9  5636.4   239.5
#Mann= 5 , 1 , 0
 3496.60      10       0  4496.6   0.154       0  4983.7   0.054       0
  5014.8   0.154       0  5461.6      10       0
Bank Sta=4983.70,5014.80
Exp/Cntr=0.5,0.3

Type RM Length L Ch R = 1 ,103174.7,40,40,40
BEGIN DESCRIPTION:
Upstream Section of Bridge/Culvert/Weir
END DESCRIPTION:
#Sta/Elev= 30
  3570.9  235.79  3710.9  230.09  3770.9  231.09  3880.9  228.89  3960.9  228.89
  4040.9  227.79  4060.9  226.59  4208.9  225.69  4378.9  220.09  4499.4  220.35
  4654.1  219.29  4734.1  220.09    4777  218.75  4798.7  216.38  4812.3  218.08
  4839.6  219.33  4943.4  218.86  4983.7  219.87  4991.1  216.95  5001.4  216.01
  5008.6  216.54  5014.8  219.88  5195.8  219.11  5199.7  218.17  5265.1  219.15
  5268.8  219.99  5391.5  219.99  5441.5  223.69  5511.5  237.59  5525.1  238.89
#Mann= 4 , 1 , 0
 3570.90      10       0  4499.4   0.154       0  4983.7   0.054       0
  5014.8   0.154       0
#XS Ineff= 2 , 0
       0    4973     220    5025       0   219.8
Bank Sta=4983.70,5014.80
Exp/Cntr=0.5,0.3

Type RM Length L Ch R = 2 ,103154.7,,,
BEGIN DESCRIPTION:
Farm Road
Structure ID: FRMCCR 160
END DESCRIPTION:
Bridge Culvert--1,0,-1,-1, 0
Deck Dist Width WeirC Skew NumUp NumDn MinLoCord MaxHiCord MaxSubmerge Is_Ogee
10,20,3,, 60, 60,,,0.95,0,1,1,,
  3570.9  3590.9  3660.9  3710.9  3770.9  3880.9  3930.9  3940.9  3960.9  4040.9
  4060.9  4110.9  4190.9  4208.9  4258.9  4268.9  4318.9  4368.9  4378.9  4438.9
  4448.9  4488.9  4504.1  4534.1  4604.1  4624.1  4644.1  4654.1  4734.1  4779.5
  4798.7  4805.7  4812.3  4839.6  4943.4  4971.6  4978.1  4983.7  4991.1  5001.5
  5005.9  5008.6  5014.8  5029.3  5082.6  5150.2  5195.8  5199.7  5265.1  5268.8
  5318.8  5341.5  5371.5  5391.5  5411.5  5441.5  5471.5  5481.5  5511.5  5525.1
  235.78  234.58  232.48  230.08  231.08  228.88  228.98  228.48  228.88  227.78
  226.58  226.98  225.48  225.68  223.88  223.98  221.88  220.88  220.51  220.44
  220.43  220.52  220.65  220.17  220.18  219.58  219.88  219.63  220.08  218.78
  218.98  219.06  219.12  219.32  219.35     220  219.92  220.79  222.33  223.21
  223.03  222.93  222.61  221.73  220.23  220.05  220.77  220.83  220.33  220.29
  220.28  219.78  220.68  219.98  220.78  223.68  229.48  232.08  237.58  238.88
  235.78  234.58  232.48  230.08  231.08  228.88  228.98  228.48  228.88  227.78
  226.58  226.98  225.48  225.68  223.88  223.98  221.88  220.88  220.08  220.28
  219.58  219.88  220.58  220.08  220.18  219.58  219.88  219.28  220.08  218.47
  216.37  216.69  218.07  219.32  218.85     220  219.92  219.86  216.94  216.02
  216.73  216.53  219.87  219.32  219.39  219.34   219.1  218.16  219.14  219.98
  220.28  219.78  220.68  219.98  220.78  223.68  229.48  232.08  237.58  238.88
  3570.9  3590.9  3660.9  3710.9  3770.9  3880.9  3930.9  3940.9  3960.9  4040.9
  4060.9  4110.9  4190.9  4208.9  4258.9  4268.9  4318.9  4368.9  4378.9  4438.9
  4448.9  4488.9  4504.1  4534.1  4604.1  4624.1  4644.1  4654.1  4734.1  4779.5
  4798.7  4805.7  4812.3  4839.6  4943.4  4971.6  4978.1  4983.7  4991.1  5001.5
  5005.9  5008.6  5014.8  5029.3  5082.6  5150.2  5195.8  5199.7  5265.1  5268.8
  5318.8  5341.5  5371.5  5391.5  5411.5  5441.5  5471.5  5481.5  5511.5  5525.1
   235.7   234.5   232.4  230.02  231.01  228.81  228.91  228.41  228.81  227.71
  226.51  226.91  225.41  225.61  223.81  223.91  221.87  220.81  220.51  220.44
  220.43  220.52  220.65  220.17  220.11  219.51  219.81  219.63  220.01  218.78
  218.98  219.06  219.12  219.26  219.35  219.93  219.85  220.79  222.33  223.21
  223.03  222.93  222.61  221.73  220.23  220.05  220.77  220.83  220.33  220.29
  220.21  219.71  220.61   219.9   220.7   223.6   229.4     232   237.5   238.8
  235.61  234.41  232.31  229.91  230.91  228.71  228.81  228.31  228.71  227.61
  226.41  226.81  225.31  225.51  223.71  223.81  221.71  220.71  219.91  220.11
  219.41  219.71  220.41  219.91  220.01  219.41  219.71  219.11  219.91   218.3
   216.2  216.52   217.9  219.15  218.68  219.83  219.75  219.69  216.77  215.85
  216.56  216.36   219.7  219.15  219.22  219.17  218.93  217.99  218.97  219.81
  220.11  219.61  220.51  219.81  220.61  223.51  229.31  231.91  237.41  238.71
BR Coef= 1 , 0 , 0 ,1.25, 0 ,,,0.8,-1,2,0,
Wspro=,,,, 1 ,,,, 0 ,,,, 0 ,,,,-1 ,-1 ,-1 , 0 , 0 , 0 , 0 , 0
Culvert=1,2.0,,20.0,0.024,0.9,1.0,2,3,216.54,4798.00,216.45,4798.00,Culvert #1  ,0,10
Culvert=1,2.0,,20.0,0.024,0.9,1.0,2,3,219.01,4997.00,218.82,4997.00,Culvert #2  ,0,10
Culvert=1,5.8,,20.0,0.024,0.9,1.0,2,3,216.00,5001.30,215.83,5001.30,Culvert #3  ,0,10
Culvert=1,1.5,,20.0,0.024,0.9,1.0,2,3,218.69,5199.20,218.74,5199.20,Culvert #4  ,0,10
BC Design=,, 0 ,, 0 ,,,,,,
BR U #Sta/Elev= 127
  3570.9  235.78  3590.9  234.58  3660.9  232.48  3674.4  231.83  3694.4  230.87
  3710.9  230.08  3734.4  230.47  3770.9  231.08  3794.4  230.52  3814.4  230.04
  3820.9  229.88  3834.4  229.78  3854.4  229.63  3860.9  229.58  3880.9  228.88
  3884.4  228.89  3914.4  228.95  3930.9  228.98  3940.9  228.48  3944.4  228.55
  3960.9  228.88  3974.4  228.69  3984.4  228.56  4040.9  227.78  4054.4  226.97
  4060.9  226.58  4110.9  226.98  4140.9  226.18  4184.4  225.57  4190.9  225.48
  4194.4  225.52  4198.9  225.58  4204.4  225.63  4208.9  225.68  4258.9  223.88
  4268.9  223.98  4318.9  221.88  4324.4  221.77  4334.4  221.57  4368.9  220.88
  4378.9  220.08    4381  220.09  4438.9  220.28  4448.9  219.58  4458.9  219.98
    4481  219.91  4488.9  219.88  4494.1  220.08  4499.4  220.34    4501  220.43
  4504.1  220.58  4534.1  220.08  4538.6  220.15  4554.1  220.38  4564.1  219.98
  4578.6  220.05  4588.6   220.1  4598.6  220.15  4604.1  220.18  4624.1  219.58
  4628.6  219.65  4644.1  219.88  4648.6  219.61  4654.1  219.28  4670.7  219.51
  4690.7  219.79  4704.1  219.98  4724.1  219.78  4729.9  219.95  4734.1  220.08
  4755.3  219.68    4777  218.74  4779.5  218.47  4798.7  216.37  4805.7  216.69
  4812.3  218.07    4829  218.83  4839.6  219.32  4878.1  219.03  4891.7  218.93
  4927.7  218.87  4943.4  218.85  4971.6     220  4978.1  219.92  4983.7  219.86
  4989.6  217.54  4991.1  216.94  4991.5  216.91  4997.1  216.55  5001.4     216
  5001.5  216.02  5005.9  216.73  5008.6  216.53  5010.4  217.51  5011.5   218.1
  5014.8  219.87  5028.6  219.35  5029.3  219.32  5062.1  219.43  5082.6  219.39
  5110.8  219.34  5150.2  219.34  5157.3  219.34  5195.8   219.1  5199.7  218.16
  5207.1  218.45  5207.2  218.45  5265.1  219.14  5268.8  219.98  5289.9  220.11
  5318.8  220.28  5338.6  219.98  5338.8  219.98  5341.5  219.78  5358.6  220.29
    5364  220.46  5371.5  220.68    5374  220.59    5384  220.24  5391.5  219.98
  5411.5  220.78  5431.5  222.38  5441.5  223.68  5471.5  229.48  5481.5  232.08
  5511.5  237.58  5525.1  238.88
BR U #Mann= 4
 3570.90      10  4499.4   0.154  4983.7   0.054  5014.8   0.154
BR U Banks=4983.70,5014.80
BR D #Sta/Elev= 127
  3570.9  235.61  3590.9  234.41  3660.9  232.31  3674.4  231.66  3694.4   230.7
  3710.9  229.91  3734.4   230.3  3770.9  230.91  3794.4  230.35  3814.4  229.87
  3820.9  229.71  3834.4  229.61  3854.4  229.46  3860.9  229.41  3880.9  228.71
  3884.4  228.72  3914.4  228.78  3930.9  228.81  3940.9  228.31  3944.4  228.38
  3960.9  228.71  3974.4  228.52  3984.4  228.39  4040.9  227.61  4054.4   226.8
  4060.9  226.41  4110.9  226.81  4140.9  226.01  4184.4   225.4  4190.9  225.31
  4194.4  225.35  4198.9  225.41  4204.4  225.46  4208.9  225.51  4258.9  223.71
  4268.9  223.81  4318.9  221.71  4324.4   221.6  4334.4   221.4  4368.9  220.71
  4378.9  219.91    4381  219.92  4438.9  220.11  4448.9  219.41  4458.9  219.81
    4481  219.74  4488.9  219.71  4494.1  219.91  4499.4  220.17    4501  220.26
  4504.1  220.41  4534.1  219.91  4538.6  219.98  4554.1  220.21  4564.1  219.81
  4578.6  219.88  4588.6  219.93  4598.6  219.98  4604.1  220.01  4624.1  219.41
  4628.6  219.48  4644.1  219.71  4648.6  219.44  4654.1  219.11  4670.7  219.34
  4690.7  219.62  4704.1  219.81  4724.1  219.61  4729.9  219.78  4734.1  219.91
  4755.3  219.51    4777  218.57  4779.5   218.3  4798.7   216.2  4805.7  216.52
  4812.3   217.9    4829  218.66  4839.6  219.15  4878.1  218.86  4891.7  218.76
  4927.7   218.7  4943.4  218.68  4971.6  219.83  4978.1  219.75  4983.7  219.69
  4989.6  217.37  4991.1  216.77  4991.5  216.74  4997.1  216.38  5001.4  215.83
  5001.5  215.85  5005.9  216.56  5008.6  216.36  5010.4  217.34  5011.5  217.93
  5014.8   219.7  5028.6  219.18  5029.3  219.15  5062.1  219.26  5082.6  219.22
  5110.8  219.17  5150.2  219.17  5157.3  219.17  5195.8  218.93  5199.7  217.99
  5207.1  218.28  5207.2  218.28  5265.1  218.97  5268.8  219.81  5289.9  219.94
  5318.8  220.11  5338.6  219.81  5338.8  219.81  5341.5  219.61  5358.6  220.12
    5364  220.29  5371.5  220.51    5374  220.42    5384  220.07  5391.5  219.81
  5411.5  220.61  5431.5  222.21  5441.5  223.51  5471.5  229.31  5481.5  231.91
  5511.5  237.41  5525.1  238.71
BR D #Mann= 4
 3570.90      10  4499.4   0.154  4983.7   0.054  5014.8   0.154
BR D Banks=4983.70,5014.80

Type RM Length L Ch R = 1 ,103134.7,221.9,221.9,221.9
BEGIN DESCRIPTION:
Downstream Section of Bridge/Culvert/Weir
END DESCRIPTION:
#Sta/Elev= 30
  3570.9  235.52  3710.9  229.82  3770.9  230.82  3880.9  228.62  3960.9  228.62
  4040.9  227.52  4060.9  226.32  4208.9  225.42  4378.9  219.82  4499.4  220.08
  4654.1  219.02  4734.1  219.82    4777  218.48  4798.7  216.11  4812.3  217.81
  4839.6  219.06  4943.4  218.59  4983.7   219.6  4991.1  216.68  5001.4  215.74
  5008.6  216.27  5014.8  219.61  5195.8  218.84  5199.7   217.9  5265.1  218.88
  5268.8  219.72  5391.5  219.72  5441.5  223.42  5511.5  237.32  5525.1  238.62
#Mann= 4 , 1 , 0
 3570.90      10       0  4499.4   0.154       0  4983.7   0.054       0
  5014.8   0.154       0
#XS Ineff= 2 , 0
       0    4973     220    5025       0   219.8
Bank Sta=4983.70,5014.80
Exp/Cntr=0.5,0.3

Type RM Length L Ch R = 1 ,102912.8,525.5,525.5,525.5
BEGIN DESCRIPTION:
Cross Section Moccasin Creek 24.0
END DESCRIPTION:
#Sta/Elev= 30
  3806.4     239  3886.4   235.3  4086.4   230.3  4146.4   226.5  4166.4   224.2
  4246.4   220.7  4356.4     221  4376.4   220.3  4416.4     221  4596.6   219.4
  4634.4  220.82  4656.6   219.7  4716.6   219.4  4736.6   218.5  4866.6   219.9
  4966.6   219.3  4983.7  218.51  4991.1  215.59  5001.4  214.65  5008.6  215.18
  5014.8  218.52  5019.6   219.4  5059.6   219.3  5089.6   218.1  5139.6   219.7
  5369.6   219.1  5543.3   220.7  5563.3   222.4  5633.3   233.7  5659.6   236.9
#Mann= 5 , 1 , 0
 3806.40      10       0  4634.4   0.154       0  4983.7   0.054       0
  5014.8   0.154       0  5659.6    0.22       0
Bank Sta=4983.70,5014.80
Exp/Cntr=0.3,0.1

Type RM Length L Ch R = 1 ,102387.3,580.8,580.8,580.8
BEGIN DESCRIPTION:
Cross Section Moccasin Creek 23.0
END DESCRIPTION:
#Sta/Elev= 30
  4081.7   236.4  4281.7   230.4  4311.7   230.8  4401.7   227.4  4421.7   225.7
  4461.7   224.6  4521.7   220.5  4551.7     220  4581.7   218.2  4921.7   218.6
  4983.7  216.52  4991.1   213.6  5001.4  212.66  5008.6  213.19  5014.8  216.53
  5037.9     218  5197.9   219.5  5217.9   218.7  5475.5   218.9  5536.7  220.27
  5575.5   219.3  5605.5   220.1  5702.6   217.9  5752.6   219.3  5792.6   222.1
  5962.6     224  6012.6   226.2  6062.6   227.1  6172.6   234.3  6189.5   234.1
#Mann= 5 , 1 , 0
 4081.70    0.22       0  4081.7   0.154       0  4983.7   0.054       0
  5014.8   0.154       0  5536.7      10       0
Bank Sta=4983.70,5014.80
Exp/Cntr=0.3,0.1