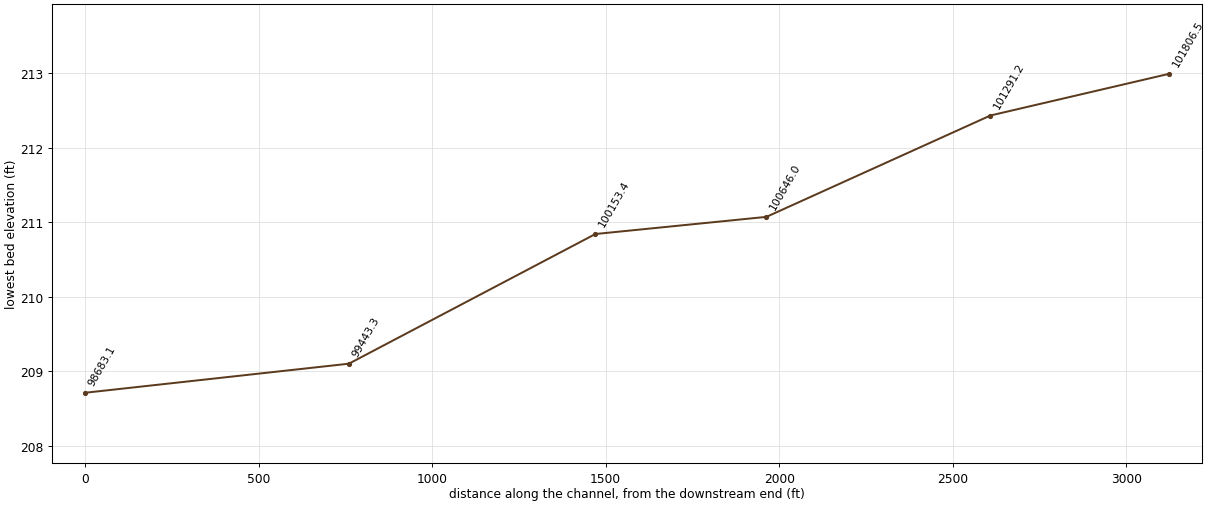
HEC-RAS study Moccasin_Creek_FINAL.prj: Moccasin Creek - Detail Study

--- Moccasin_Creek_FINAL.g01 (geometry) --- (continued)

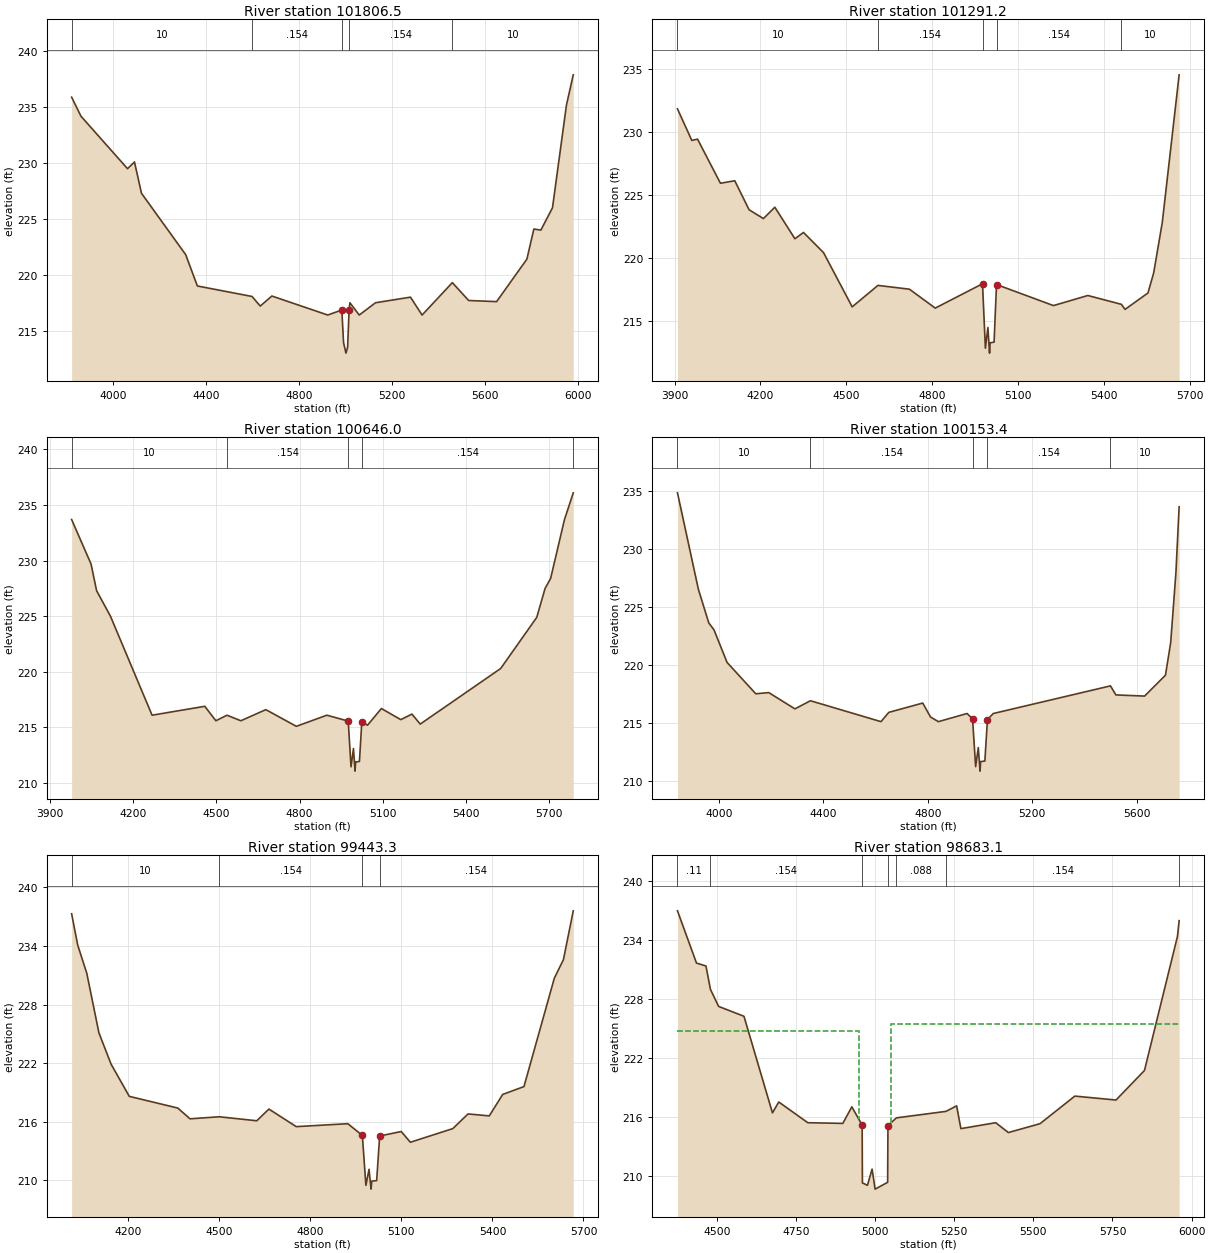
Type RM Length L Ch R = 1 ,101806.5,515.3,515.3,515.3
BEGIN DESCRIPTION:
Cross Section Moccasin Creek 22.0
END DESCRIPTION:
#Sta/Elev= 30
  3823.3   235.9  3863.3   234.2  4063.3   229.5  4093.3   230.1  4123.3   227.3
  4313.3   221.8  4363.3     219  4598.3  218.06  4633.3   217.2  4683.3   218.1
  4923.3   216.4  4983.7  216.85  4991.1  213.93  5001.4  212.99  5008.6  213.52
  5014.8  216.86  5018.4   217.5  5058.4   216.4  5128.4   217.5  5278.4     218
  5328.4   216.4  5458.3   219.3  5528.4   217.7  5648.4   217.6  5778.4   221.4
  5808.4   224.1  5838.4     224  5888.4     226  5948.4   235.2  5977.6   237.9
#Mann= 5 , 1 , 0
 3823.30      10       0  4598.3   0.154       0  4983.7   0.054       0
  5014.8   0.154       0  5458.3      10       0
Bank Sta=4983.70,5014.80
Exp/Cntr=0.3,0.1

Type RM Length L Ch R = 1 ,101291.2,645.2,645.2,645.2
BEGIN DESCRIPTION:
Cross Section Moccasin Creek 21.0
END DESCRIPTION:
#Sta/Elev= 30
  3910.4   231.8  3960.4   229.3  3980.4   229.4  4060.4   225.9  4110.4   226.1
  4160.4   223.8  4210.4   223.1  4250.4     224  4320.4   221.5  4350.4     222
  4420.4   220.4  4520.4   216.1  4610.4   217.8  4720.4   217.5  4810.4     216
 4975.52  217.93 4985.54  212.82 4994.36  214.46 5000.06  212.43 5002.04  213.25
  5015.9   213.3 5024.42  217.87  5223.3   216.2  5343.3     217  5460.4   216.3
  5473.3   215.9  5553.3   217.2  5573.3   218.8  5603.3   222.8  5662.1   234.5
#Mann= 5 , 1 , 0
 3910.40      10       0  4610.4   0.154       0 4975.52   0.054       0
 5024.42   0.154       0  5460.4      10       0
Bank Sta=4975.52,5024.42
Exp/Cntr=0.3,0.1

Type RM Length L Ch R = 1 ,100646.0,492.6,492.6,492.6
BEGIN DESCRIPTION:
Cross Section Moccasin Creek 20.0
END DESCRIPTION:
#Sta/Elev= 30
  3978.5   233.7  4048.5   229.7  4068.5   227.3  4118.5     225  4268.5   216.1
  4458.5   216.9  4498.5   215.6  4538.5   216.1  4588.5   215.6  4678.5   216.6
  4788.5   215.1  4898.5   216.1 4975.52  215.57 4985.54  211.46 4994.36   213.1
 5000.06  211.07 5002.04  211.89  5015.9  211.94 5024.42  215.51    5045   215.2
    5095   216.7    5165   215.7    5205   216.2    5235   215.3    5525   220.3
    5655   224.9    5685   227.5    5705   228.4    5755   233.7  5786.6   236.1
#Mann= 5 , 1 , 0
 3978.50      10       0  4538.5   0.154       0 4975.52   0.054       0
 5024.42   0.154       0  5786.6    0.22       0
Bank Sta=4975.52,5024.42
Exp/Cntr=0.3,0.1

Type RM Length L Ch R = 1 ,100153.4,710.1,710.1,710.1
BEGIN DESCRIPTION:
Cross Section Moccasin Creek 19.0
END DESCRIPTION:
#Sta/Elev= 30
  3840.4   234.8  3920.4   226.5  3960.4   223.6  3980.4     223  4030.4   220.2
  4140.4   217.5  4190.4   217.6  4290.4   216.2    4350   216.9  4620.4   215.1
  4650.4   215.9  4780.4   216.7  4810.4   215.5  4840.4   215.1  4950.4   215.8
 4971.44  215.34 4983.13  211.23 4993.42  212.87 5000.07  210.84 5002.38  211.66
 5018.55  211.71 5028.49  215.28  5050.8   215.8    5500  218.18  5520.8   217.4
  5630.8   217.3  5710.8   219.1  5730.8   221.9  5750.8   227.9  5763.2   233.6
#Mann= 5 , 1 , 0
 3840.40      10       0    4350   0.154       0 4971.44   0.054       0
 5028.49   0.154       0    5500      10       0
Bank Sta=4971.44,5028.49
Exp/Cntr=0.3,0.1

Type RM Length L Ch R = 1 ,99443.3,760.2,760.2,760.2
BEGIN DESCRIPTION:
Cross Section Moccasin Creek 18.0
END DESCRIPTION:
#Sta/Elev= 30
  4013.6   237.3  4033.6   234.1  4063.6   231.2  4103.6   225.1  4143.6   221.9
  4203.6   218.6  4363.6   217.4  4403.6   216.3    4500  216.51  4623.6   216.1
  4663.6   217.3  4753.6   215.5  4923.6   215.8 4971.44   214.6 4983.13  209.49
 4993.42  211.13 5000.07   209.1 5002.38  209.92 5018.55  209.97 5028.49  214.54
  5099.6     215  5129.6   213.9  5269.6   215.3  5319.6   216.8  5389.6   216.6
  5433.9   218.8  5503.9   219.6  5603.9   230.7  5633.9   232.6  5666.3   237.6
#Mann= 4 , 1 , 0
 4013.60      10       0    4500   0.154       0 4971.44   0.054       0
 5028.49   0.154       0
Bank Sta=4971.44,5028.49
Exp/Cntr=0.5,0.3

Type RM Length L Ch R = 1 ,98683.1,43,43,43
BEGIN DESCRIPTION:
Upstream Section of Bridge/Culvert/Weir
END DESCRIPTION:
#Sta/Elev= 30
  4375.8  236.95  4435.8  231.65  4465.8  231.35  4479.9  228.98  4505.8  227.25
  4585.8  226.25  4675.8  216.45  4695.8  217.55  4787.5  215.45  4898.1  215.38
  4926.6  217.06  4959.2  215.21    4960  209.34  4975.9   209.1  4990.6  210.74
  5000.1  208.71  5039.7   209.4  5040.7  215.15  5067.3  215.94    5224   216.6
  5257.7  217.16  5271.1  214.85  5381.1  215.45  5421.1  214.45  5521.1  215.35
  5631.1  218.15  5761.1  217.75  5851.1  220.75  5955.3  234.35  5960.6  235.95
#Mann= 7 , 1 , 0
 4375.80    0.11       0  4479.9   0.154       0  4959.2   0.054       0
  5040.7   0.154       0  5067.3   0.088       0    5224   0.154       0
  5960.6    0.22       0
#XS Ineff= 2 , 0
       0    4948   224.8    5051       0   225.5
Bank Sta=4959.20,5040.70
Exp/Cntr=0.5,0.3