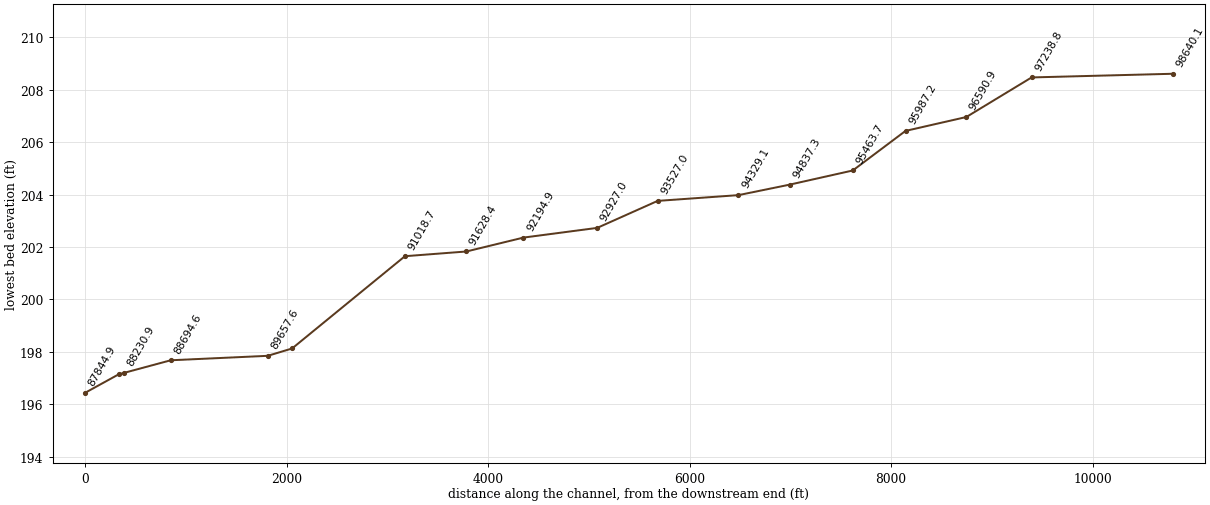
HEC-RAS study Moccasin_Creek_FINAL.prj: Moccasin Creek - Detail Study

--- Moccasin_Creek_FINAL.g01 (geometry) --- (continued)

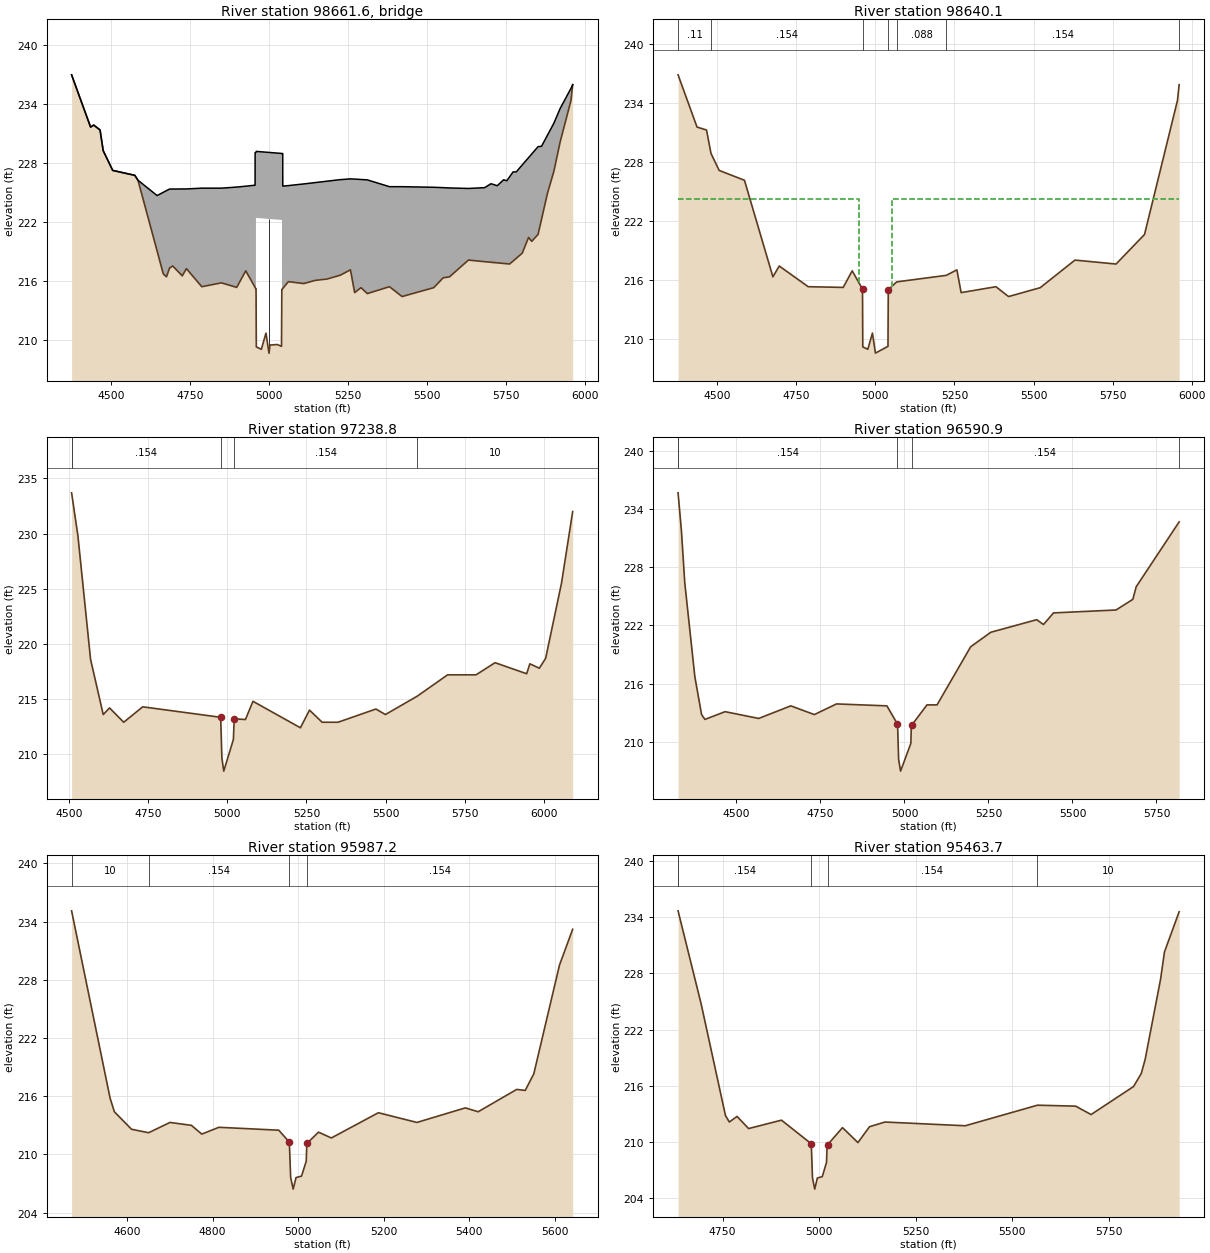
Type RM Length L Ch R = 3 ,98661.6,,,
BEGIN DESCRIPTION:
NC 97
Structure ID: FRMCCR1
END DESCRIPTION:
Bridge Culvert--1,0,-1,-1, 0
Deck Dist Width WeirC Skew NumUp NumDn MinLoCord MaxHiCord MaxSubmerge Is_Ogee
10,23,2.6,, 60, 60,,,0.95,0,1,1,,
  4375.8  4435.8  4445.8  4465.8  4475.8  4505.8  4575.8  4585.8  4646.2  4665.8
  4675.8  4685.8  4695.8  4725.8  4738.9  4787.5  4849.8  4898.1  4926.6 4956.09
  4956.2 4958.71  4958.8  4960.1  5041.1 5041.19  5041.3  5043.6 5043.71  5061.5
  5110.3    5224  5257.7  5271.1  5291.1  5311.1  5381.1  5421.1  5521.1  5551.1
  5571.1  5631.1  5682.1  5702.1  5722.1  5742.1  5752.1  5761.1  5772.1  5782.1
  5801.1  5821.1  5831.1  5851.1  5862.1  5881.1  5901.1  5921.1  5955.3  5960.6
  236.95  231.65  231.85  231.35  229.25  227.25  226.75  226.25   224.7  225.03
   225.2  225.36  225.36  225.37  225.37  225.45  225.45  225.56  225.65  225.75
  229.05  229.07  229.08  229.18  228.97  228.96  228.95  228.96  225.66  225.71
  225.88  226.31  226.39  226.37  226.33  226.29   225.6   225.6  225.54   225.5
  225.47  225.42   225.5   225.9   225.7   226.3   226.2   226.6   227.1   227.1
  227.81  228.55  228.92  229.66   229.7  230.84  232.04  233.54  235.58  235.95
  236.95  231.65  231.85  231.35  229.25  227.25  226.75  226.25  219.08  216.75
  216.45  217.35  217.55  216.55  217.28  215.45  215.84  215.38  217.06  215.39
  215.38  215.24  222.33  222.43  222.22  222.21  215.17  215.26  215.27  215.96
  215.77   216.6  217.16  214.85  215.35  214.75  215.45  214.45  215.35  216.35
  216.45  218.15  217.99  217.93  217.87  217.81  217.78  217.75  218.05  218.33
  218.85  220.45  220.05  220.75  222.29  224.95  227.15  230.15  234.35  235.95
  4375.8  4435.8  4445.8  4465.8  4475.8  4505.8  4575.8  4585.8  4646.2  4665.8
  4675.8  4685.8  4695.8  4725.8  4738.9  4787.5  4849.8  4898.1  4926.6 4956.09
  4956.2 4958.71  4958.8  4960.1  5041.1 5041.19  5041.3  5043.6 5043.71  5061.5
  5110.3    5224  5257.7  5271.1  5291.1  5311.1  5381.1  5421.1  5521.1  5551.1
  5571.1  5631.1  5682.1  5702.1  5722.1  5742.1  5752.1  5761.1  5772.1  5782.1
  5801.1  5821.1  5831.1  5851.1  5862.1  5881.1  5901.1  5921.1  5955.3  5960.6
   236.9  231.61  231.81  231.31  229.21  227.21  226.71  226.21   224.7  225.03
   225.2  225.36  225.36  225.37  225.37  225.45  225.45  225.56  225.65  225.75
  229.05  229.07  229.08  229.18  228.97  228.96  228.95  228.96  225.66  225.71
  225.88  226.31  226.39  226.37  226.33  226.29   225.6   225.6  225.54   225.5
  225.47  225.42   225.5   225.9   225.7   226.3   226.2   226.6   227.1   227.1
  227.81  228.55  228.92  229.66   229.7  230.84  232.04  233.54  235.58   235.9
  236.85  231.55  231.75  231.25  229.15  227.15  226.65  226.15  218.98  216.65
  216.35  217.25  217.45  216.45  217.18  215.35  215.74  215.28  216.96  215.29
  215.28  215.14  222.23  222.33  222.12  222.11  215.07  215.16  215.17  215.86
  215.67   216.5  217.06  214.75  215.25  214.65  215.35  214.35  215.25  216.25
  216.35  218.05  217.89  217.83  217.77  217.71  217.68  217.65  217.95  218.23
  218.75  220.35  219.95  220.65  222.19  224.85  227.05  230.05  234.25  235.85
Pier Skew, UpSta & Num, DnSta & Num=,5000.1, 2 ,5000.1, 2 , 0 , 0 , 0 ,,
     2.5     2.5
  207.98   223.4
     2.5     2.5
  207.88   223.3
BR Coef= 1 , 1 , 0 ,1.25, 0 ,,,0.8,0,2,0,
Wspro=,,,, 1 ,,,, 0 ,,,, 0 ,,,,-1 ,-1 ,-1 , 0 , 0 , 0 , 0 , 0
BC Design=,, 0 ,, 0 ,,,,,,
BR U #Sta/Elev= 106
  4375.8  236.95  4396.2  235.15  4426.2   232.5  4435.8  231.65  4445.8  231.85
  4456.2  231.59  4465.8  231.35  4466.2  231.27  4475.8  229.25  4479.9  228.98
  4505.8  227.25  4516.2  227.18  4536.2  227.03  4566.2  226.82  4575.8  226.75
  4585.8  226.25  4646.2  219.08  4665.8  216.75  4675.8  216.45  4685.6  217.33
  4685.8  217.35  4695.8  217.55  4725.8  216.55  4738.9  217.28  4739.8  217.25
  4787.5  215.45  4792.6  215.48  4849.7  215.84  4849.8  215.84  4898.1  215.38
  4905.7  215.83  4926.6  217.06 4956.09  215.39  4956.2  215.38 4956.31  215.37
  4958.6  215.24 4958.71  215.24  4958.8  215.23  4958.9  215.23  4959.2  215.21
    4960  209.34  4960.1  209.34  4975.9   209.1  4990.6  210.74  5000.1  208.71
  5003.4  209.53  5026.5  209.58  5039.1  209.41  5039.7   209.4  5040.7  215.15
  5041.1  215.17 5041.19  215.17  5041.3  215.17  5041.4  215.18 5043.49  215.26
  5043.6  215.26 5043.71  215.27  5061.5  215.96  5067.3  215.94  5094.6  215.83
  5110.3  215.77  5146.2  216.09    5152  216.11  5183.9  216.23  5205.4  216.43
    5224   216.6  5225.9  216.62  5257.6  217.16  5257.7  217.16  5271.1  214.85
  5291.1  215.35  5310.1  214.78  5311.1  214.75  5362.1  215.26  5372.1  215.36
  5381.1  215.45  5421.1  214.45  5432.1  214.55  5482.1     215  5521.1  215.35
  5551.1  216.35  5571.1  216.45  5622.1   217.9  5631.1  218.15  5682.1  217.99
  5702.1  217.93  5722.1  217.87  5742.1  217.81  5752.1  217.78  5761.1  217.75
  5772.1  218.05  5782.1  218.33  5801.1  218.85  5821.1  220.45  5831.1  220.05
  5851.1  220.75  5852.1  220.89  5862.1  222.29  5881.1  224.95  5882.1  225.06
  5901.1  227.15  5902.1   227.3  5912.1   228.8  5921.1  230.15  5955.3  234.35
  5960.6  235.95
BR U #Mann= 7
 4375.80    0.11  4479.9   0.154  4959.2   0.054  5040.7   0.154  5067.3   0.088
    5224   0.154  5960.6    0.22
BR U Banks=4959.20,5040.70
BR D #Sta/Elev= 106
  4375.8  236.85  4396.2  235.05  4426.2   232.4  4435.8  231.55  4445.8  231.75
  4456.2  231.49  4465.8  231.25  4466.2  231.17  4475.8  229.15  4479.9  228.88
  4505.8  227.15  4516.2  227.08  4536.2  226.93  4566.2  226.72  4575.8  226.65
  4585.8  226.15  4646.2  218.98  4665.8  216.65  4675.8  216.35  4685.6  217.23
  4685.8  217.25  4695.8  217.45  4725.8  216.45  4738.9  217.18  4739.8  217.15
  4787.5  215.35  4792.6  215.38  4849.7  215.74  4849.8  215.74  4898.1  215.28
  4905.7  215.73  4926.6  216.96 4956.09  215.29  4956.2  215.28 4956.31  215.27
  4958.6  215.14 4958.71  215.14  4958.8  215.13  4958.9  215.13  4959.2  215.11
    4960  209.24  4960.1  209.24  4975.9     209  4990.6  210.64  5000.1  208.61
  5003.4  209.43  5026.5  209.48  5039.1  209.31  5039.7   209.3  5040.7  215.05
  5041.1  215.07 5041.19  215.07  5041.3  215.07  5041.4  215.08 5043.49  215.16
  5043.6  215.16 5043.71  215.17  5061.5  215.86  5067.3  215.84  5094.6  215.73
  5110.3  215.67  5146.2  215.99    5152  216.01  5183.9  216.13  5205.4  216.33
    5224   216.5  5225.9  216.52  5257.6  217.06  5257.7  217.06  5271.1  214.75
  5291.1  215.25  5310.1  214.68  5311.1  214.65  5362.1  215.16  5372.1  215.26
  5381.1  215.35  5421.1  214.35  5432.1  214.45  5482.1   214.9  5521.1  215.25
  5551.1  216.25  5571.1  216.35  5622.1   217.8  5631.1  218.05  5682.1  217.89
  5702.1  217.83  5722.1  217.77  5742.1  217.71  5752.1  217.68  5761.1  217.65
  5772.1  217.95  5782.1  218.23  5801.1  218.75  5821.1  220.35  5831.1  219.95
  5851.1  220.65  5852.1  220.79  5862.1  222.19  5881.1  224.85  5882.1  224.96
  5901.1  227.05  5902.1   227.2  5912.1   228.7  5921.1  230.05  5955.3  234.25
  5960.6  235.85
BR D #Mann= 7
 4375.80    0.11  4479.9   0.154  4959.2   0.054  5040.7   0.154  5067.3   0.088
    5224   0.154  5960.6    0.22
BR D Banks=4959.20,5040.70

Type RM Length L Ch R = 1 ,98640.1,1401.3,1401.3,1401.3
BEGIN DESCRIPTION:
Downstream Section of Bridge/Culvert/Weir
END DESCRIPTION:
#Sta/Elev= 30
  4375.8  236.85  4435.8  231.55  4465.8  231.25  4479.9  228.88  4505.8  227.15
  4585.8  226.15  4675.8  216.35  4695.8  217.45  4787.5  215.35  4898.1  215.28
  4926.6  216.96  4959.2  215.11    4960  209.24  4975.9     209  4990.6  210.64
  5000.1  208.61  5039.7   209.3  5040.7  215.05  5067.3  215.84    5224   216.5
  5257.7  217.06  5271.1  214.75  5381.1  215.35  5421.1  214.35  5521.1  215.25
  5631.1  218.05  5761.1  217.65  5851.1  220.65  5955.3  234.25  5960.6  235.85
#Mann= 7 , 1 , 0
 4375.80    0.11       0  4479.9   0.154       0  4959.2   0.054       0
  5040.7   0.154       0  5067.3   0.088       0    5224   0.154       0
  5960.6    0.22       0
#XS Ineff= 2 , 0
       0    4948   224.3    5051       0   224.3
Bank Sta=4959.20,5040.70
Exp/Cntr=0.5,0.3

Type RM Length L Ch R = 1 ,97238.8,647.9,647.9,647.9
BEGIN DESCRIPTION:
Cross Section Moccasin Creek XS158
END DESCRIPTION:
#Sta/Elev= 30
  4507.5   233.7  4527.5   229.8  4567.5   218.6  4607.5   213.6  4627.5   214.2
  4672.3   212.9  4732.3   214.3  4978.8  213.35  4982.6  209.68  4988.5  208.47
    5019  211.34  5021.6  213.21  5057.1  213.15  5080.9   214.8  5230.9   212.4
  5259.6     214  5299.6   212.9  5349.6   212.9  5469.6   214.1  5499.6   213.6
    5600  215.26  5696.2   217.2  5786.2   217.2  5846.2   218.3  5946.2   217.3
  5956.2   218.2  5986.2   217.8  6006.2   218.7  6056.2   225.5  6091.6     232
#Mann= 5 , 1 , 0
 4507.50    0.22       0  4507.5   0.154       0  4978.8   0.054       0
  5021.6   0.154       0    5600      10       0
Bank Sta=4978.80,5021.60
Exp/Cntr=0.3,0.1

Type RM Length L Ch R = 1 ,96590.9,603.7,603.7,603.7
BEGIN DESCRIPTION:
Cross Section Moccasin Creek 13.0
END DESCRIPTION:
#Sta/Elev= 30
  4326.2   235.7  4336.2   231.8  4346.2   226.4  4376.2   216.7  4396.2   212.8
  4406.2   212.3  4466.2   213.1  4566.2   212.4  4661.8   213.7  4731.8   212.8
  4797.8   213.9  4947.8   213.7  4978.8  211.84    4980  211.26  4982.6  208.17
  4988.5  206.96    5019  209.83  5020.1  211.23  5021.6   211.7    5067   213.8
    5097   213.8    5197   219.8    5257   221.3  5393.7   222.6  5413.7   222.1
  5443.7   223.3  5629.7   223.6  5679.7   224.7  5689.7     226  5817.5   232.7
#Mann= 5 , 1 , 0
 4326.20    0.22       0  4326.2   0.154       0  4978.8   0.054       0
  5021.6   0.154       0  5817.5    0.22       0
Bank Sta=4978.80,5021.60
Exp/Cntr=0.3,0.1

Type RM Length L Ch R = 1 ,95987.2,523.5,523.5,523.5
BEGIN DESCRIPTION:
Cross Section Moccasin Creek 12.0
END DESCRIPTION:
#Sta/Elev= 30
  4470.6   235.1  4560.6   215.8  4570.6   214.4  4610.6   212.6  4650.6  212.24
  4700.6   213.3  4750.6     213  4774.9   212.1  4814.9   212.8  4954.9   212.5
  4978.8  211.31    4980  210.73  4982.6  207.64  4988.5  206.43  4995.2  207.62
    5008  207.77    5019   209.3  5020.1   210.7  5021.6  211.17  5047.7   212.3
  5077.7   211.7  5187.7   214.3  5277.7   213.3  5390.9   214.8  5420.9   214.4
  5510.9   216.7  5530.9   216.6  5550.9   218.3  5610.9   229.5  5641.8   233.2
#Mann= 4 , 1 , 0
 4470.60      10       0  4650.6   0.154       0  4978.8   0.054       0
  5021.6   0.154       0
Bank Sta=4978.80,5021.60
Exp/Cntr=0.3,0.1

Type RM Length L Ch R = 1 ,95463.7,626.4,626.4,626.4
BEGIN DESCRIPTION:
Cross Section Moccasin Creek 11.0
END DESCRIPTION:
#Sta/Elev= 30
  4634.6   234.7  4694.6   224.7  4757.3   212.8  4767.3   212.1  4787.3   212.7
  4817.3   211.4  4902.3   212.3  4978.8   209.8    4980  209.22  4982.6  206.13
  4988.5  204.92  4995.2  206.11    5008  206.26    5019  207.79  5020.1  209.19
  5021.6  209.66  5060.3   211.5  5100.3   209.9  5130.3   211.6  5170.3   212.1
  5378.1   211.7    5565   213.9  5663.9   213.8  5703.9   212.9  5813.9   215.9
  5833.9   217.3  5843.9   218.8  5883.9   227.4  5893.9   230.3  5931.9   234.6
#Mann= 5 , 1 , 0
 4634.60    0.22       0  4634.6   0.154       0  4978.8   0.054       0
  5021.6   0.154       0    5565      10       0
Bank Sta=4978.80,5021.60
Exp/Cntr=0.3,0.1

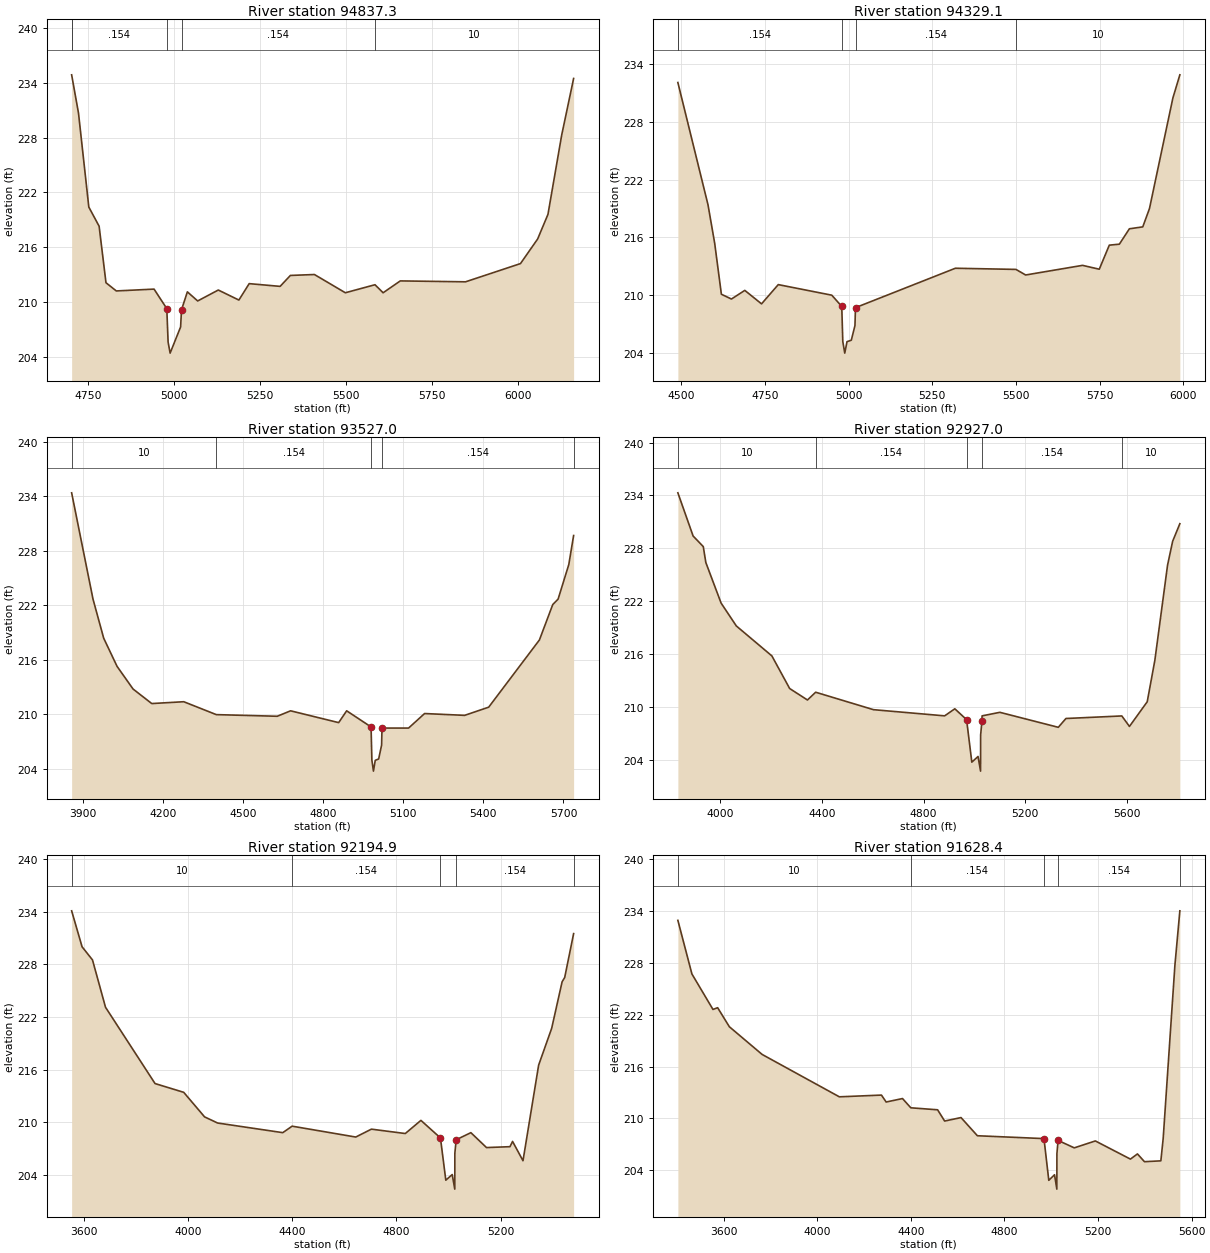
Type RM Length L Ch R = 1 ,94837.3,508.2,508.2,508.2
BEGIN DESCRIPTION:
Cross Section Moccasin Creek 10.0
END DESCRIPTION:
#Sta/Elev= 30
  4701.7   234.9  4721.7   230.7  4751.7   220.4  4781.7   218.3  4801.7   212.1
  4831.7   211.2  4941.7   211.4  4978.8  209.26  4982.6  205.59  4988.5  204.38
    5019  207.25  5021.6  209.12  5038.7   211.1  5068.7   210.1  5128.7   211.3
  5188.7   210.2  5218.7     212  5308.7   211.7  5338.7   212.9  5408.7     213
  5498.7     211    5585  211.88  5608.7     211  5658.7   212.3  5848.7   212.2
  6008.7   214.2  6058.7   216.9  6088.7   219.6  6128.7   228.3  6163.4   234.5
#Mann= 5 , 1 , 0
 4701.70    0.22       0  4701.7   0.154       0  4978.8   0.054       0
  5021.6   0.154       0    5585      10       0
Bank Sta=4978.80,5021.60
Exp/Cntr=0.3,0.1

Type RM Length L Ch R = 1 ,94329.1,802.1,802.1,802.1
BEGIN DESCRIPTION:
Cross Section Moccasin Creek 9.0
END DESCRIPTION:
#Sta/Elev= 30
  4489.8   232.1  4579.8   219.4  4599.8   215.4  4619.8   210.1  4649.8   209.6
  4689.8   210.5  4739.8   209.1  4789.8   211.1  4949.8     210  4978.8  208.86
    4980  208.28  4982.6  205.19  4988.5  203.98  4995.2  205.17    5008  205.32
    5019  206.85  5020.1  208.25  5021.6  208.72    5319   212.8    5500  212.68
    5529   212.1    5699   213.1    5749   212.7    5779   215.2    5809   215.3
    5839   216.9    5879   217.1    5899     219    5969   230.5  5989.8   232.9
#Mann= 5 , 1 , 0
 4489.80    0.22       0  4489.8   0.154       0  4978.8   0.054       0
  5021.6   0.154       0    5500      10       0
Bank Sta=4978.80,5021.60
Exp/Cntr=0.3,0.1

Type RM Length L Ch R = 1 ,93527.0,600,600,600
BEGIN DESCRIPTION:
Cross Section Moccasin Creek 8.0
END DESCRIPTION:
#Sta/Elev= 30
  3858.2   234.4  3938.2   222.7  3978.2   218.4  4028.2   215.3  4088.2   212.8
  4158.2   211.2  4278.2   211.4    4400  209.98  4628.2   209.8  4678.2   210.4
  4858.2   209.1  4888.2   210.4  4978.8  208.64    4980  208.06  4982.6  204.97
  4988.5  203.76  4995.2  204.95    5008   205.1    5019  206.63  5020.1  208.03
  5021.6   208.5    5120   208.5    5180   210.1    5330   209.9    5420   210.8
    5610   218.2    5660   222.1    5680   222.7    5720   226.5  5738.1   229.7
#Mann= 5 , 1 , 0
 3858.20      10       0    4400   0.154       0  4978.8   0.054       0
  5021.6   0.154       0  5738.1    0.22       0
Bank Sta=4978.80,5021.60
Exp/Cntr=0.3,0.1

Type RM Length L Ch R = 1 ,92927.0,732.1,732.1,732.1
BEGIN DESCRIPTION:
Cross Section Moccasin Creek 7.0
END DESCRIPTION:
#Sta/Elev= 30
  3832.7   234.3  3892.7   229.4  3932.7   228.2  3942.7   226.4  4002.7   221.8
  4062.7   219.2  4202.7   215.8  4272.7   212.1  4342.7   210.8    4375  211.68
  4602.7   209.7  4882.7     209  4922.7   209.8    4969  208.57  4989.6  203.75
  5014.1  204.39    5024  202.73  5024.3  206.83  5029.3  208.36    5030     209
    5100   209.4    5330   207.7    5360   208.7    5580  208.99    5610   207.8
    5680   210.6    5710   215.3    5760   226.1    5780   228.8  5808.4   230.8
#Mann= 5 , 1 , 0
 3832.70      10       0    4375   0.154       0    4969   0.054       0
  5029.3   0.154       0    5580      10       0
Bank Sta=4969.00,5029.30
Exp/Cntr=0.3,0.1

Type RM Length L Ch R = 1 ,92194.9,566.5,566.5,566.5
BEGIN DESCRIPTION:
Cross Section Moccasin Creek 6.0
END DESCRIPTION:
#Sta/Elev= 30
  3554.1   234.1  3594.1     230  3634.1   228.5  3684.1   223.1  3874.1   214.4
  3984.1   213.4  4064.1   210.6  4114.1   209.9  4364.1   208.8    4400  209.54
  4644.1   208.3  4704.1   209.2  4834.1   208.7  4894.1   210.2    4969   208.2
  4989.6  203.38  5014.1  204.02    5024  202.36  5024.3  206.46  5029.3  207.99
  5085.7   208.8  5145.7   207.1  5235.7   207.2  5245.7   207.8  5285.7   205.6
  5345.7   216.5  5395.7   220.7  5435.7     226  5445.7   226.5  5479.9   231.5
#Mann= 5 , 1 , 0
 3554.10      10       0    4400   0.154       0    4969   0.054       0
  5029.3   0.154       0  5479.9    0.22       0
Bank Sta=4969.00,5029.30
Exp/Cntr=0.3,0.1

Type RM Length L Ch R = 1 ,91628.4,609.7,609.7,609.7
BEGIN DESCRIPTION:
Cross Section Moccasin Creek 5.0
END DESCRIPTION:
#Sta/Elev= 30
  3404.5   232.9  3464.5   226.7  3554.5   222.6  3574.5   222.8  3624.5   220.6
  3764.5   217.4  4094.5   212.5  4274.5   212.7  4294.5   211.9  4364.5   212.3
    4400  211.23  4514.5     211  4544.5   209.7  4614.5   210.1  4684.5     208
    4969  207.67  4989.6  202.85  5014.1  203.49    5024  201.83  5024.3  205.93
  5029.3  207.46  5098.5   206.6  5188.5   207.4  5338.5   205.3  5368.5   205.9
  5398.5     205  5468.5   205.1  5478.5   207.7  5528.5   227.7  5549.7     234
#Mann= 5 , 1 , 0
 3404.50      10       0    4400   0.154       0    4969   0.054       0
  5029.3   0.154       0  5549.7    0.22       0
Bank Sta=4969.00,5029.30
Exp/Cntr=0.3,0.1

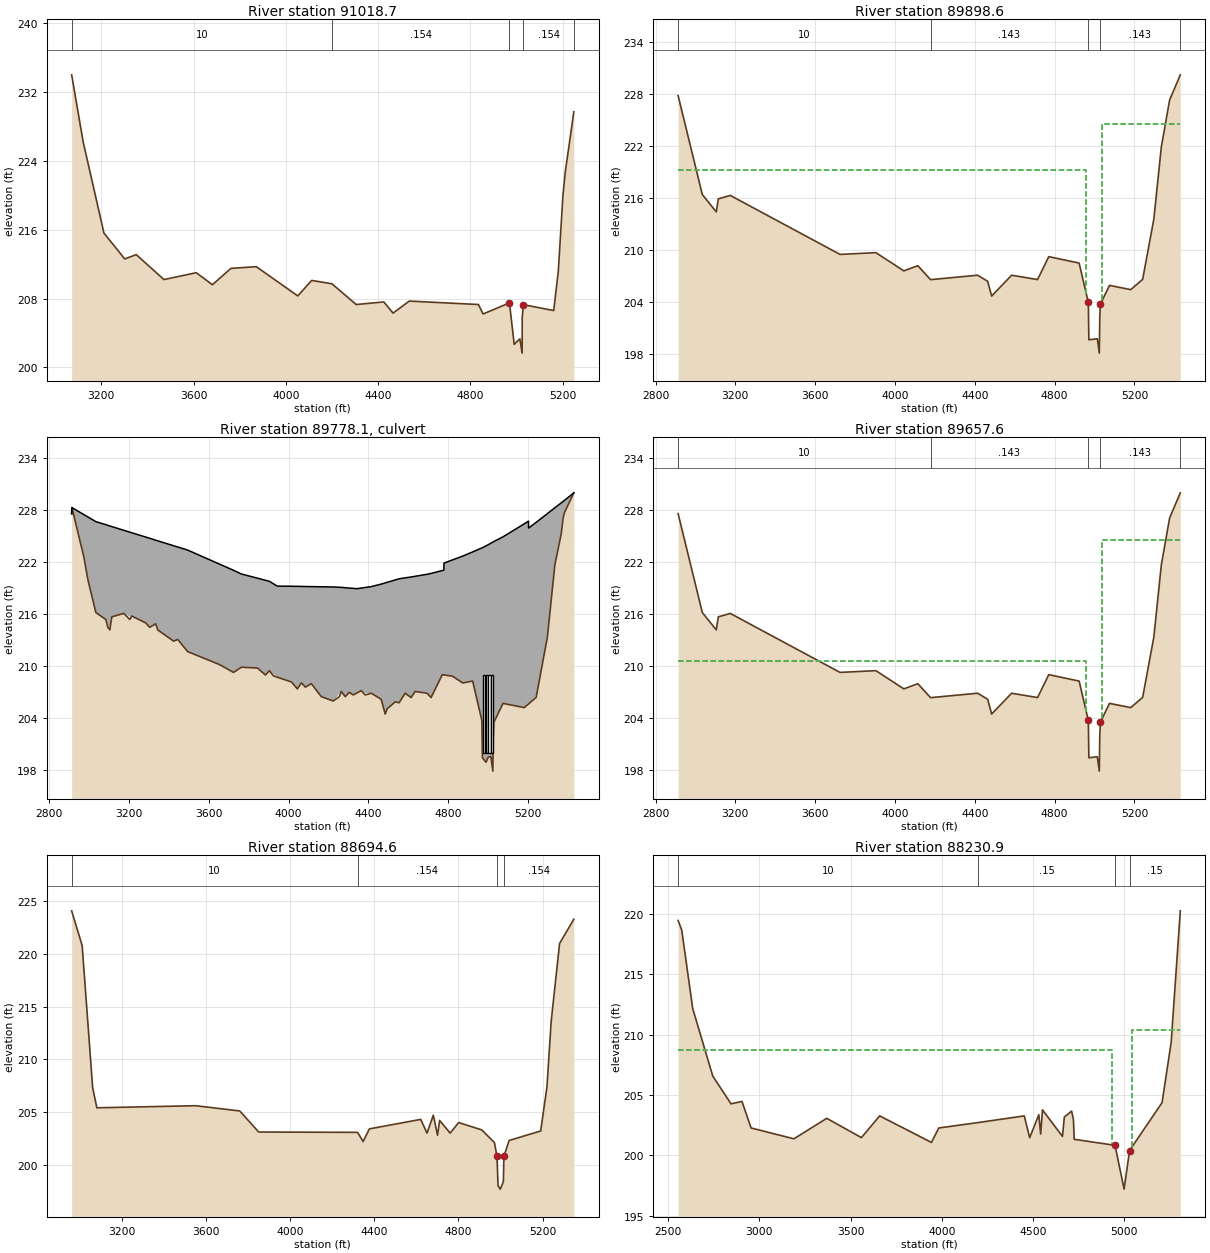
Type RM Length L Ch R = 1 ,91018.7,1120.1,1120.1,1120.1
BEGIN DESCRIPTION:
Cross Section Moccasin Creek 4.0
END DESCRIPTION:
#Sta/Elev= 30
  3071.9     234  3121.9   226.2  3211.9   215.6  3301.9   212.6  3351.9   213.1
  3471.9   210.2  3611.9     211  3681.9   209.6  3761.9   211.5  3871.9   211.7
  4051.9   208.3  4111.9   210.1    4200  209.71  4304.7   207.3  4424.7   207.6
  4464.7   206.3  4534.7   207.7  4834.7   207.3  4854.7   206.2    4969  207.49
  4989.6  202.67  5014.1  203.31    5024  201.65  5024.3  205.75  5029.3  207.28
  5160.8   206.6  5180.8   211.2  5200.8     220  5210.8   222.7    5248   229.7
#Mann= 5 , 1 , 0
 3071.90      10       0    4200   0.154       0    4969   0.054       0
  5029.3   0.154       0    5248    0.22       0
Bank Sta=4969.00,5029.30
Exp/Cntr=0.5,0.3

Type RM Length L Ch R = 1 ,89898.6,241,241,241
BEGIN DESCRIPTION:
Upstream Section of Bridge/Culvert/Weir
END DESCRIPTION:
#Sta/Elev= 30
  2913.2  227.81  3034.5  216.41  3104.5  214.41  3114.5  215.91  3174.5  216.31
  3724.5  209.51  3904.5  209.71  4044.5  207.61  4114.5  208.21  4178.2   206.6
  4414.5  207.11  4464.5  206.41  4484.5  204.71  4584.5  207.11  4714.5  206.61
  4770.8  209.25  4922.9  208.51    4969  203.97  4971.6  199.67  5014.1  199.79
    5024  198.13  5026.3  202.23  5029.3  203.76    5075  205.94  5181.5  205.45
  5241.2  206.63  5297.3  213.58  5334.8   221.9  5376.4  227.31  5429.9  230.21
#Mann= 5 , 1 , 0
 2913.20      10       0  4178.2   0.143       0    4969   0.054       0
  5029.3   0.143       0  5429.9    0.22       0
#XS Ineff= 2 , 0
       0    4959   219.2    5039       0   224.5
Bank Sta=4969.00,5029.30
Exp/Cntr=0.5,0.3

Type RM Length L Ch R = 2 ,89778.1,,,
BEGIN DESCRIPTION:
US Hwy 264
Structure ID: WK_MCCR264
END DESCRIPTION:
Bridge Culvert--1,0,-1,-1, 0
Deck Dist Width WeirC Skew NumUp NumDn MinLoCord MaxHiCord MaxSubmerge Is_Ogee
10,221,3,, 60, 60,,,0.95,0,1,1,,
  2913.2  2914.5  3034.5  3084.5  3104.5  3114.5  3174.5  3304.5  3334.5  3344.5
  3424.5  3444.5  3494.5  3724.5  3764.5  3844.5  3884.5  3904.5  3943.2  4014.5
  4044.5  4064.5  4084.5  4114.5  4164.5  4224.5  4264.5  4284.5  4343.2  4414.5
  4464.5  4484.5  4554.5  4584.5  4614.5  4634.5  4694.5  4714.5  4770.8 4778.69
  4778.8  4873.5  4922.9    4969  4971.6  4989.6  5014.1    5024  5026.3  5029.3
    5075  5181.5  5202.8 5202.91  5241.2  5297.3  5334.8  5366.7  5376.4  5429.9
  227.55  228.25  226.63  226.28  226.13  226.06  225.63  224.71  224.49  224.42
  223.85  223.71  223.35  221.02  220.59  220.11  219.87  219.75   219.2  219.18
  219.17  219.16  219.15  219.14  219.12   219.1  219.05  219.01   218.9  219.14
  219.43  219.57  220.04  220.15  220.25  220.33  220.56  220.66  220.99  221.05
  221.85  222.66  223.14   223.6  223.62  223.83  224.14  224.27   224.3  224.34
  224.88  226.38  226.69  225.89  226.55  227.55  228.23  228.79  228.96  229.95
  227.55  228.25  216.15  215.35  214.15  215.65  216.05  214.45  214.85  214.15
  212.85  213.05  211.65  209.25  209.85  209.75  208.95  209.45   208.7  208.15
  207.35  208.05  207.55  207.95  206.45  205.95  207.05  206.45  206.88  206.85
  206.15  204.45  205.75  206.85  206.35  207.05  206.85  206.35  208.99  208.96
  208.96  208.03  208.25  203.71  199.41  198.89  199.53  197.87  201.97   203.5
  205.68  205.19  205.61  205.61  206.37  213.32  221.64  225.22  227.05  229.95
  2913.2  2914.5  3034.5  3084.5  3104.5  3114.5  3174.5  3304.5  3334.5  3344.5
  3424.5  3444.5  3494.5  3724.5  3764.5  3844.5  3884.5  3904.5  3943.2  4014.5
  4044.5  4064.5  4084.5  4114.5  4164.5  4224.5  4264.5  4284.5  4343.2  4414.5
  4464.5  4484.5  4554.5  4584.5  4614.5  4634.5  4694.5  4714.5  4770.8 4778.69
  4778.8  4873.5  4922.9    4969  4971.6  4989.6  5014.1    5024  5026.3  5029.3
    5075  5181.5  5202.8 5202.91  5241.2  5297.3  5334.8  5366.7  5376.4  5429.9
   227.5  228.21  226.63  226.28  226.13  226.06  225.63  224.71  224.49  224.42
  223.85  223.71  223.35  221.02  220.59  220.11  219.87  219.75   219.2  219.18
  219.17  219.16  219.15  219.14  219.12   219.1  219.05  219.01   218.9  219.14
  219.43  219.57  220.04  220.15  220.25  220.33  220.56  220.66  220.99  221.05
  221.85  222.66  223.14   223.6  223.62  223.83  224.14  224.27   224.3  224.34
  224.88  226.38  226.69  225.89  226.55  227.55  228.23  228.79  228.96   229.9
  227.45  228.15  216.05  215.25  214.05  215.55  215.95  214.35  214.75  214.05
  212.75  212.95  211.55  209.15  209.75  209.65  208.85  209.35   208.6  208.05
  207.25  207.95  207.45  207.85  206.35  205.85  206.95  206.35  206.78  206.75
  206.05  204.35  205.65  206.75  206.25  206.95  206.75  206.25  208.89  208.86
  208.86  207.93  208.15  203.61  199.31  198.79  199.43  197.77  201.87   203.4
  205.58  205.09  205.51  205.51  206.27  213.22  221.54  225.12  226.95  229.85
BR Coef= 1 , 0 , 0 ,1.25, 0 ,,,0.8,-1,2,0,
Wspro=,,,, 1 ,,,, 0 ,,,, 0 ,,,,-1 ,-1 ,-1 , 0 , 0 , 0 , 0 , 0
Culvert=2,9.0,12.0,221.0,0.015,0.4,1.0,8,1,199.94,4979.60,199.89,4979.60,Culvert #1  ,0,10
Culvert=2,9.0,12.0,221.0,0.015,0.4,1.0,8,1,199.94,4994.60,199.89,4994.60,Culvert #2  ,0,10
Culvert=2,9.0,12.0,221.0,0.015,0.4,1.0,8,1,199.94,5006.80,199.89,5006.80,Culvert #3  ,0,10
Culvert=2,9.0,12.0,221.0,0.015,0.4,1.0,8,1,199.94,5019.00,199.89,5019.00,Culvert #4  ,0,10
BC Design=,, 0 ,, 0 ,,,,,,
BR U #Sta/Elev= 101
  2913.2  227.55  2914.5  228.25  2974.5  222.55  2994.5  219.95  3034.5  216.15
  3084.5  215.35  3094.5  214.45  3104.5  214.15  3114.5  215.65  3174.5  216.05
  3204.5  215.35  3214.5  215.75  3284.5  214.95  3304.5  214.45  3334.5  214.85
  3344.5  214.15  3424.5  212.85  3444.5  213.05  3494.5  211.65  3543.2  211.19
  3654.5  210.15  3724.5  209.25  3763.2  209.83  3764.5  209.85  3844.5  209.75
  3884.5  208.95  3904.5  209.45  3913.2  209.19  3924.5  208.85  3943.2   208.7
  4014.5  208.15  4044.5  207.35  4064.5  208.05  4084.5  207.55  4114.5  207.95
  4124.5  207.65  4164.5  206.45  4178.2  206.34  4224.5  205.95  4233.2   206.1
  4254.5  206.45  4264.5  207.05  4284.5  206.45  4293.2  206.67  4304.5  206.95
  4324.5  206.65  4343.2  206.88  4364.5  207.15  4384.5  206.65  4414.5  206.85
  4433.2  206.59  4464.5  206.15  4484.5  204.45  4494.5  205.05  4534.5  205.85
  4543.2  205.81  4554.5  205.75  4584.5  206.85  4614.5  206.35  4634.5  207.05
  4683.2  206.89  4694.5  206.85  4714.5  206.35  4756.3  208.31  4770.8  208.99
 4778.69  208.96  4778.8  208.96 4778.91  208.96  4809.5  208.85  4821.8  208.81
    4868  208.11  4873.5  208.03  4922.9  208.25  4925.3  208.01    4969  203.71
  4971.6  199.41  4980.4  199.16  4989.6  198.89  5001.6   199.5  5014.1  199.53
    5024  197.87  5026.3  201.97  5029.3   203.5  5034.8  203.76    5075  205.68
  5090.1  205.61  5146.9  205.35  5181.5  205.19 5202.69  205.61  5202.8  205.61
 5202.91  205.61  5205.3  205.66  5241.2  206.37  5266.5   209.5  5297.3  213.32
  5321.9  218.78  5334.8  221.64  5366.7  225.22  5376.4  227.05  5382.6  227.65
  5429.9  229.95
BR U #Mann= 5
 2913.20      10  4178.2   0.143    4969   0.054  5029.3   0.143  5429.9    0.22
BR U Banks=4969.00,5029.30
BR D #Sta/Elev= 101
  2913.2  227.45  2914.5  228.15  2974.5  222.45  2994.5  219.85  3034.5  216.05
  3084.5  215.25  3094.5  214.35  3104.5  214.05  3114.5  215.55  3174.5  215.95
  3204.5  215.25  3214.5  215.65  3284.5  214.85  3304.5  214.35  3334.5  214.75
  3344.5  214.05  3424.5  212.75  3444.5  212.95  3494.5  211.55  3543.2  211.09
  3654.5  210.05  3724.5  209.15  3763.2  209.73  3764.5  209.75  3844.5  209.65
  3884.5  208.85  3904.5  209.35  3913.2  209.09  3924.5  208.75  3943.2   208.6
  4014.5  208.05  4044.5  207.25  4064.5  207.95  4084.5  207.45  4114.5  207.85
  4124.5  207.55  4164.5  206.35  4178.2  206.24  4224.5  205.85  4233.2     206
  4254.5  206.35  4264.5  206.95  4284.5  206.35  4293.2  206.57  4304.5  206.85
  4324.5  206.55  4343.2  206.78  4364.5  207.05  4384.5  206.55  4414.5  206.75
  4433.2  206.49  4464.5  206.05  4484.5  204.35  4494.5  204.95  4534.5  205.75
  4543.2  205.71  4554.5  205.65  4584.5  206.75  4614.5  206.25  4634.5  206.95
  4683.2  206.79  4694.5  206.75  4714.5  206.25  4756.3  208.21  4770.8  208.89
 4778.69  208.86  4778.8  208.86 4778.91  208.86  4809.5  208.75  4821.8  208.71
    4868  208.01  4873.5  207.93  4922.9  208.15  4925.3  207.91    4969  203.61
  4971.6  199.31  4980.4  199.06  4989.6  198.79  5001.6   199.4  5014.1  199.43
    5024  197.77  5026.3  201.87  5029.3   203.4  5034.8  203.66    5075  205.58
  5090.1  205.51  5146.9  205.25  5181.5  205.09 5202.69  205.51  5202.8  205.51
 5202.91  205.51  5205.3  205.56  5241.2  206.27  5266.5   209.4  5297.3  213.22
  5321.9  218.68  5334.8  221.54  5366.7  225.12  5376.4  226.95  5382.6  227.55
  5429.9  229.85
BR D #Mann= 5
 2913.20      10  4178.2   0.143    4969   0.054  5029.3   0.143  5429.9    0.22
BR D Banks=4969.00,5029.30

Type RM Length L Ch R = 1 ,89657.6,963,963,963
BEGIN DESCRIPTION:
Downstream Section of Bridge/Culvert/Weir
END DESCRIPTION:
#Sta/Elev= 30
  2913.2  227.53  3034.5  216.13  3104.5  214.13  3114.5  215.63  3174.5  216.03
  3724.5  209.23  3904.5  209.43  4044.5  207.33  4114.5  207.93  4178.2  206.32
  4414.5  206.83  4464.5  206.13  4484.5  204.43  4584.5  206.83  4714.5  206.33
  4770.8  208.97  4922.9  208.23    4969  203.69  4971.6  199.39  5014.1  199.51
    5024  197.85  5026.3  201.95  5029.3  203.48    5075  205.66  5181.5  205.17
  5241.2  206.35  5297.3   213.3  5334.8  221.62  5376.4  227.03  5429.9  229.93
#Mann= 5 , 1 , 0
 2913.20      10       0  4178.2   0.143       0    4969   0.054       0
  5029.3   0.143       0  5429.9    0.22       0
#XS Ineff= 2 , 0
       0    4959   210.6    5039       0   224.5
Bank Sta=4969.00,5029.30
Exp/Cntr=0.5,0.3

Type RM Length L Ch R = 1 ,88694.6,463.7,463.7,463.7
BEGIN DESCRIPTION:
Cross Section Moccasin Creek 2.0
END DESCRIPTION:
#Sta/Elev= 30
  2959.5   224.1  3009.5   220.8  3059.5   207.3  3079.5   205.4  3549.5   205.6
  3759.5   205.1  3849.5   203.1    4320  203.07  4346.2   202.2  4376.2   203.4
  4620.3   204.3  4650.3     203  4680.3   204.7  4700.3   202.8  4710.3   204.2
  4760.3     203    4801     204    4911   203.3    4971   202.1  4983.3  200.78
  4988.3  198.01  4998.9  197.68  5013.5  198.39  5016.1  200.79    5041   202.3
    5191   203.2    5221   207.4    5241   213.6    5281     221  5348.8   223.3
#Mann= 4 , 1 , 0
 2959.50      10       0    4320   0.154       0  4983.3   0.054       0
  5016.1   0.154       0
Bank Sta=4983.30,5016.10
Exp/Cntr=0.5,0.3

Type RM Length L Ch R = 1 ,88230.9,55,55,55
BEGIN DESCRIPTION:
Upstream Section of Bridge/Culvert/Weir
END DESCRIPTION:
#Sta/Elev= 30
  2554.5  219.47  2574.5  218.67  2634.5  212.17  2744.5  206.57  2844.5  204.27
  2904.5  204.47  2954.5  202.27  3189.1  201.37  3369.1  203.07  3559.1  201.47
  3659.1  203.27  3943.1  201.07  3983.1  202.27    4200  202.72  4451.5  203.27
  4481.5  201.47  4531.5  203.37  4541.5  201.77  4551.5  203.77  4661.2  201.57
  4671.2  203.17  4711.2  203.67  4721.2  202.97  4725.4  201.33  4949.1  200.83
  4998.9   197.2  5028.8   200.4  5206.9  204.37  5256.9  209.37  5306.9  220.27
#Mann= 4 , 1 , 0
 2554.50      10       0    4200    0.15       0  4949.1    0.05       0
  5028.8    0.15       0
#XS Ineff= 2 , 0
       0    4935   208.7    5042       0   210.4
Bank Sta=4949.10,5028.80
Exp/Cntr=0.5,0.3

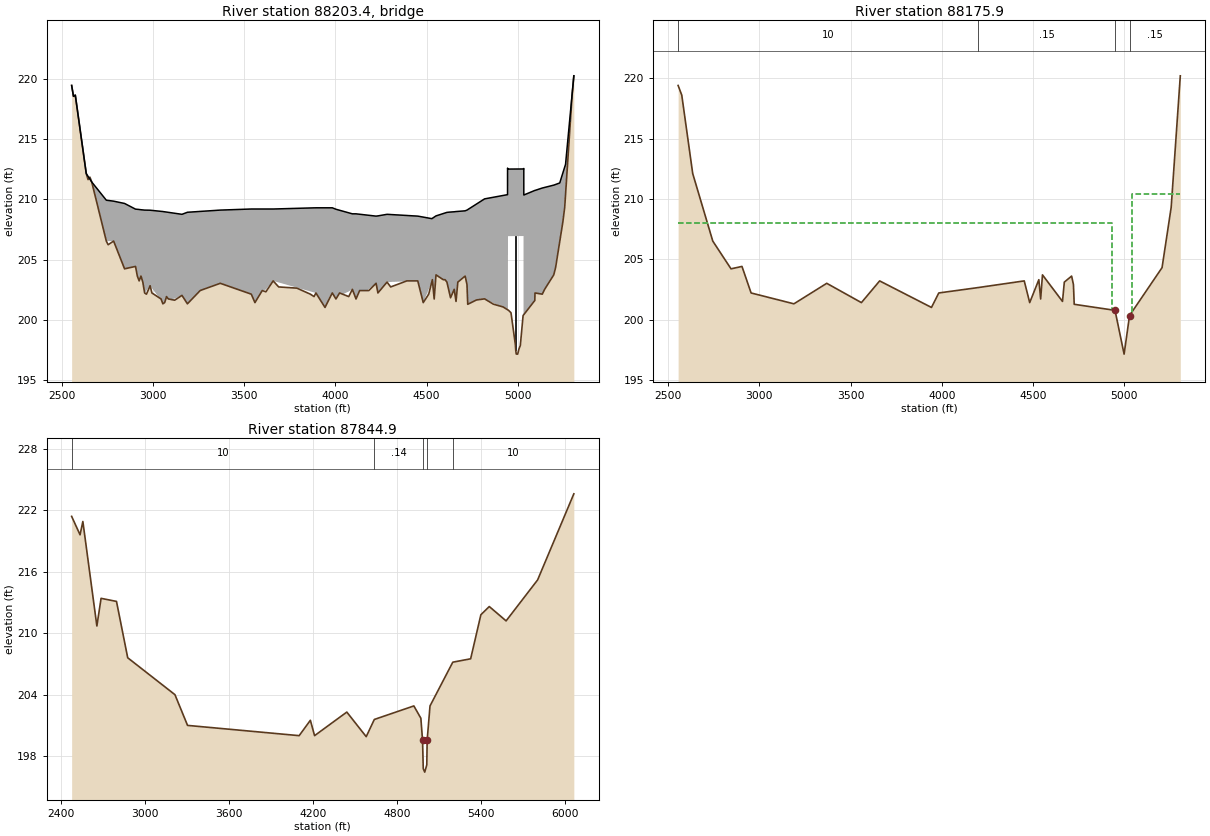
Type RM Length L Ch R = 3 ,88203.4,,,
BEGIN DESCRIPTION:
US Hwy 264A
Structure ID: WK_MCCR264A
END DESCRIPTION:
Bridge Culvert--1,0,-1,-1, 0
Deck Dist Width WeirC Skew NumUp NumDn MinLoCord MaxHiCord MaxSubmerge Is_Ogee
10,35,2.6,, 60, 60,,,0.95,0,1,1,,
  2554.5  2564.5  2574.5  2634.5  2664.5  2744.5  2784.5  2844.5  2904.5  2924.5
  2934.5  2954.5  2984.5  3054.5  3159.1  3189.1  3369.1  3539.1  3559.1  3659.1
  3893.1  3943.1  3983.1  4003.1  4093.1  4113.1  4223.1  4233.1  4283.1  4451.5
  4481.5  4528.6  4531.5  4541.5  4551.5  4611.2  4631.2  4651.2  4661.2  4671.2
  4711.2  4721.2  4725.4  4817.6 4943.49  4943.6 4945.81  4945.9 5031.09  5031.2
  5032.6 5032.71  5093.1    5094    5134  5196.9  5229.6  5246.9  5261.4  5306.9
  219.44  218.54  218.64  212.14  211.44  209.93  209.85  209.66  209.19  209.16
  209.14  209.11   209.1  208.99  208.76  208.93  209.11   209.2   209.2   209.2
   209.3   209.3   209.3  209.18   208.8   208.8  208.61  208.63  208.76  208.61
  208.53   208.4  208.43  208.53  208.63  208.92  208.95  208.97  208.99     209
  209.05  209.11  209.15  210.04  210.39  212.59  212.51  212.51  212.52  212.52
  212.56  210.36  210.74  210.74  210.94  211.18  211.36   212.2   212.9  220.24
  219.44  218.54  218.64  212.14  211.44  206.54  206.54  204.24  204.44  203.24
  203.64  202.24  202.84  201.34  202.04  201.34  203.04  202.14  201.44  203.24
  202.24  201.04  202.24  201.74  202.54  201.74  203.04  202.24  203.14  203.24
  201.44  203.17  203.34  201.74  203.74  203.14  201.84  202.54  201.54  203.14
  203.64  202.94   201.3  201.75  200.85  200.85  200.83  206.95  206.96  200.42
  200.44  200.45  201.62  202.24  202.14  203.74   206.5  208.14  210.38  220.24
  2554.5  2564.5  2574.5  2634.5  2644.5  2664.5  2744.5  2784.5  2844.5  2904.5
  2924.5  2934.5  2954.5  2984.5  3054.5  3159.1  3189.1  3369.1  3539.1  3559.1
  3659.1  3893.1  3943.1  3983.1  4003.1  4093.1  4113.1  4223.1  4233.1  4283.1
  4451.5  4481.5  4528.6  4531.5  4541.5  4551.5  4611.2  4631.2  4651.2  4661.2
  4671.2  4711.2  4721.2  4725.4  4817.6 4943.49  4943.6 4945.81  4945.9 5031.09
  5031.2  5032.6 5032.71  5093.1    5094    5134  5196.9  5246.9  5261.4  5306.9
   219.4   218.5  218.61  212.11  211.61  211.41  209.93  209.85  209.66  209.19
  209.16  209.14  209.11   209.1  208.99  208.76  208.93  209.11   209.2   209.2
   209.2   209.3   209.3   209.3  209.18   208.8   208.8  208.61  208.63  208.76
  208.61  208.53   208.4  208.43  208.53  208.63  208.92  208.95  208.97  208.99
     209  209.05  209.11  209.15  210.04  210.39  212.59  212.51  212.51  212.52
  212.52  212.56  210.36  210.74  210.74  210.94  211.18   212.2   212.9   220.2
  219.35  218.45  218.55  212.05  211.55  211.35  206.45  206.45  204.15  204.35
  203.15  203.55  202.15  202.75  201.25  201.95  201.25  202.95  202.05  201.35
  203.15  202.15  200.95  202.15  201.65  202.45  201.65  202.95  202.15  203.05
  203.15  201.35  203.08  203.25  201.65  203.65  203.05  201.75  202.45  201.45
  203.05  203.55  202.85  201.21  201.66  200.76  200.76  200.74  206.86  206.87
  200.33  200.35  200.36  201.53  202.15  202.05  203.65  208.05  210.29  220.15
Pier Skew, UpSta & Num, DnSta & Num=,4988.3, 2 ,4988.3, 2 , 0 , 0 , 0 ,,
       3       3
  196.34  207.96
       3       3
  196.25  207.86
BR Coef= 1 , 1 , 0 ,1.25, 0 ,,,0.8,0,2,0,
Wspro=,,,, 1 ,,,, 0 ,,,, 0 ,,,,-1 ,-1 ,-1 , 0 , 0 , 0 , 0 , 0
BC Design=,, 0 ,, 0 ,,,,,,
BR U #Sta/Elev= 154
  2554.5  219.44  2564.5  218.54  2567.2  218.57  2574.5  218.64  2577.2  218.35
  2597.2  216.18  2617.2  214.01  2627.2  212.93  2634.5  212.14  2637.2  212.01
  2644.5  211.64  2654.5  211.84  2664.5  211.44  2667.6  211.25  2727.6  207.58
  2744.5  206.54  2747.6  206.45  2754.5  206.24  2784.5  206.54  2827.6  204.89
  2844.5  204.24  2897.6  204.42  2904.5  204.44  2914.5  203.64  2924.5  203.24
  2934.5  203.64  2944.5  203.14  2954.5  202.24  2957.6  202.21  2964.5  202.14
  2984.5  202.84  2994.5  202.24    3036  201.82  3044.5  201.74  3054.5  201.34
  3064.5  201.44  3074.5  201.94  3084.5  201.74    3086  201.74    3096  201.71
  3119.1  201.64    3136  201.81  3159.1  202.04    3176  201.65  3189.1  201.34
    3196  201.45  3259.1  202.44    3266  202.48    3356  202.97  3369.1  203.04
  3470.6   202.5  3539.1  202.14  3559.1  201.44  3599.1  202.44  3619.1  202.34
  3659.1  203.24  3689.1  202.74  3720.6  202.71  3789.1  202.64  3821.2  202.42
  3863.1  202.14  3881.2  201.96  3883.1  201.94  3893.1  202.24  3943.1  201.04
  3983.1  202.24  3991.2  202.04  4003.1  201.74  4023.1  202.24  4041.2  202.13
  4073.1  201.94  4093.1  202.54  4113.1  201.74  4113.7  201.76  4133.1  202.44
  4173.7  202.44  4183.1  202.44    4200  202.69  4223.1  203.04  4233.1  202.24
  4263.7  202.79  4283.1  203.14  4293.7  202.93  4303.1  202.74  4366.2   203.1
  4391.5  203.24  4418.6  203.24  4451.5  203.24  4481.5  201.44  4511.5  202.14
  4528.6  203.17  4531.5  203.34  4541.5  201.74  4551.5  203.74  4558.6  203.67
  4591.2  203.34  4595.7  203.34  4601.2  203.34  4611.2  203.14  4631.2  201.84
  4651.2  202.54  4661.2  201.54  4671.2  203.14  4711.2  203.64  4716.6  203.26
  4721.2  202.94  4725.4   201.3  4772.2  201.66  4773.2  201.66  4817.6  201.75
    4830  201.64  4866.3  201.31  4884.3  201.23  4919.1  201.08  4940.1  200.88
 4943.49  200.85  4943.6  200.85 4943.71  200.85  4945.7  200.83 4945.81  200.83
  4945.9  200.83    4946  200.83  4949.1   200.8  4962.5   200.6  4986.5  197.95
  4988.3   197.5  4991.3  197.18  4998.9  197.17    5006  197.59  5013.5  197.88
  5028.8  200.37    5031  200.41 5031.09  200.41  5031.2  200.42  5031.3  200.42
 5032.49  200.44  5032.6  200.44 5032.71  200.45  5037.2  200.53  5074.6  201.26
  5093.1  201.62    5094  202.24  5126.1  202.16    5134  202.14  5146.9  202.54
  5177.9  203.28  5196.9  203.74  5206.9  204.34  5229.6   206.5  5246.9  208.14
  5256.9  209.34  5261.4  210.38  5296.9  218.54  5306.9  220.24
BR U #Mann= 4
 2554.50      10    4200    0.15  4949.1    0.05  5028.8    0.15
BR U Banks=4949.10,5028.80
BR D #Sta/Elev= 154
  2554.5  219.35  2564.5  218.45  2567.2  218.48  2574.5  218.55  2577.2  218.26
  2597.2  216.09  2617.2  213.92  2627.2  212.84  2634.5  212.05  2637.2  211.92
  2644.5  211.55  2654.5  211.75  2664.5  211.35  2667.6  211.16  2727.6  207.49
  2744.5  206.45  2747.6  206.36  2754.5  206.15  2784.5  206.45  2827.6   204.8
  2844.5  204.15  2897.6  204.33  2904.5  204.35  2914.5  203.55  2924.5  203.15
  2934.5  203.55  2944.5  203.05  2954.5  202.15  2957.6  202.12  2964.5  202.05
  2984.5  202.75  2994.5  202.15    3036  201.73  3044.5  201.65  3054.5  201.25
  3064.5  201.35  3074.5  201.85  3084.5  201.65    3086  201.65    3096  201.62
  3119.1  201.55    3136  201.72  3159.1  201.95    3176  201.56  3189.1  201.25
    3196  201.36  3259.1  202.35    3266  202.39    3356  202.88  3369.1  202.95
  3470.6  202.41  3539.1  202.05  3559.1  201.35  3599.1  202.35  3619.1  202.25
  3659.1  203.15  3689.1  202.65  3720.6  202.62  3789.1  202.55  3821.2  202.33
  3863.1  202.05  3881.2  201.87  3883.1  201.85  3893.1  202.15  3943.1  200.95
  3983.1  202.15  3991.2  201.95  4003.1  201.65  4023.1  202.15  4041.2  202.04
  4073.1  201.85  4093.1  202.45  4113.1  201.65  4113.7  201.67  4133.1  202.35
  4173.7  202.35  4183.1  202.35    4200   202.6  4223.1  202.95  4233.1  202.15
  4263.7   202.7  4283.1  203.05  4293.7  202.84  4303.1  202.65  4366.2  203.01
  4391.5  203.15  4418.6  203.15  4451.5  203.15  4481.5  201.35  4511.5  202.05
  4528.6  203.08  4531.5  203.25  4541.5  201.65  4551.5  203.65  4558.6  203.58
  4591.2  203.25  4595.7  203.25  4601.2  203.25  4611.2  203.05  4631.2  201.75
  4651.2  202.45  4661.2  201.45  4671.2  203.05  4711.2  203.55  4716.6  203.17
  4721.2  202.85  4725.4  201.21  4772.2  201.57  4773.2  201.57  4817.6  201.66
    4830  201.55  4866.3  201.22  4884.3  201.14  4919.1  200.99  4940.1  200.79
 4943.49  200.76  4943.6  200.76 4943.71  200.76  4945.7  200.74 4945.81  200.74
  4945.9  200.74    4946  200.74  4949.1  200.71  4962.5  200.51  4986.5  197.86
  4988.3  197.41  4991.3  197.09  4998.9  197.08    5006   197.5  5013.5  197.79
  5028.8  200.28    5031  200.32 5031.09  200.32  5031.2  200.33  5031.3  200.33
 5032.49  200.35  5032.6  200.35 5032.71  200.36  5037.2  200.44  5074.6  201.17
  5093.1  201.53    5094  202.15  5126.1  202.07    5134  202.05  5146.9  202.45
  5177.9  203.19  5196.9  203.65  5206.9  204.25  5229.6  206.41  5246.9  208.05
  5256.9  209.25  5261.4  210.29  5296.9  218.45  5306.9  220.15
BR D #Mann= 4
 2554.50      10    4200    0.15  4949.1    0.05  5028.8    0.15
BR D Banks=4949.10,5028.80

Type RM Length L Ch R = 1 ,88175.9,331,331,331
BEGIN DESCRIPTION:
Downstream Section of Bridge/Culvert/Weir
END DESCRIPTION:
#Sta/Elev= 30
  2554.5  219.41  2574.5  218.61  2634.5  212.11  2744.5  206.51  2844.5  204.21
  2904.5  204.41  2954.5  202.21  3189.1  201.31  3369.1  203.01  3559.1  201.41
  3659.1  203.21  3943.1  201.01  3983.1  202.21    4200  202.66  4451.5  203.21
  4481.5  201.41  4531.5  203.31  4541.5  201.71  4551.5  203.71  4661.2  201.51
  4671.2  203.11  4711.2  203.61  4721.2  202.91  4725.4  201.27  4949.1  200.77
  4998.9  197.14  5028.8  200.34  5206.9  204.31  5256.9  209.31  5306.9  220.21
#Mann= 4 , 1 , 0
 2554.50      10       0    4200    0.15       0  4949.1    0.05       0
  5028.8    0.15       0
#XS Ineff= 2 , 0
       0    4935     208    5042       0   210.4
Bank Sta=4949.10,5028.80
Exp/Cntr=0.5,0.3

Type RM Length L Ch R = 1 ,87844.9,0,0,0
BEGIN DESCRIPTION:
Cross Section Moccasin Creek 1.0
END DESCRIPTION:
#Sta/Elev= 30
  2479.1   221.4  2539.1   219.6  2559.1   220.9  2659.1   210.7  2689.1   213.4
  2799.1   213.1  2879.2   207.6  3216.2     204  3306.2     201  4102.7     200
  4182.7   201.5  4212.7     200  4442.7   202.3  4581.2   199.9  4639.1  201.58
  4921.2   202.9  4971.2   201.7  4983.3  199.54  4988.3  196.77  4998.9  196.44
  5013.5  197.15  5016.1  199.55  5036.5   202.9  5199.1  207.17  5326.5   207.5
  5399.5   211.8  5459.5   212.6  5579.5   211.2  5804.5   215.2  6062.9   223.6
#Mann= 5 , 1 , 0
 2479.10      10       0  4639.1    0.14       0  4983.3    0.05       0
  5016.1    0.14       0  5199.1      10       0
Bank Sta=4983.30,5016.10
Exp/Cntr=0.3,0.1

Chan Stop Cuts=-1