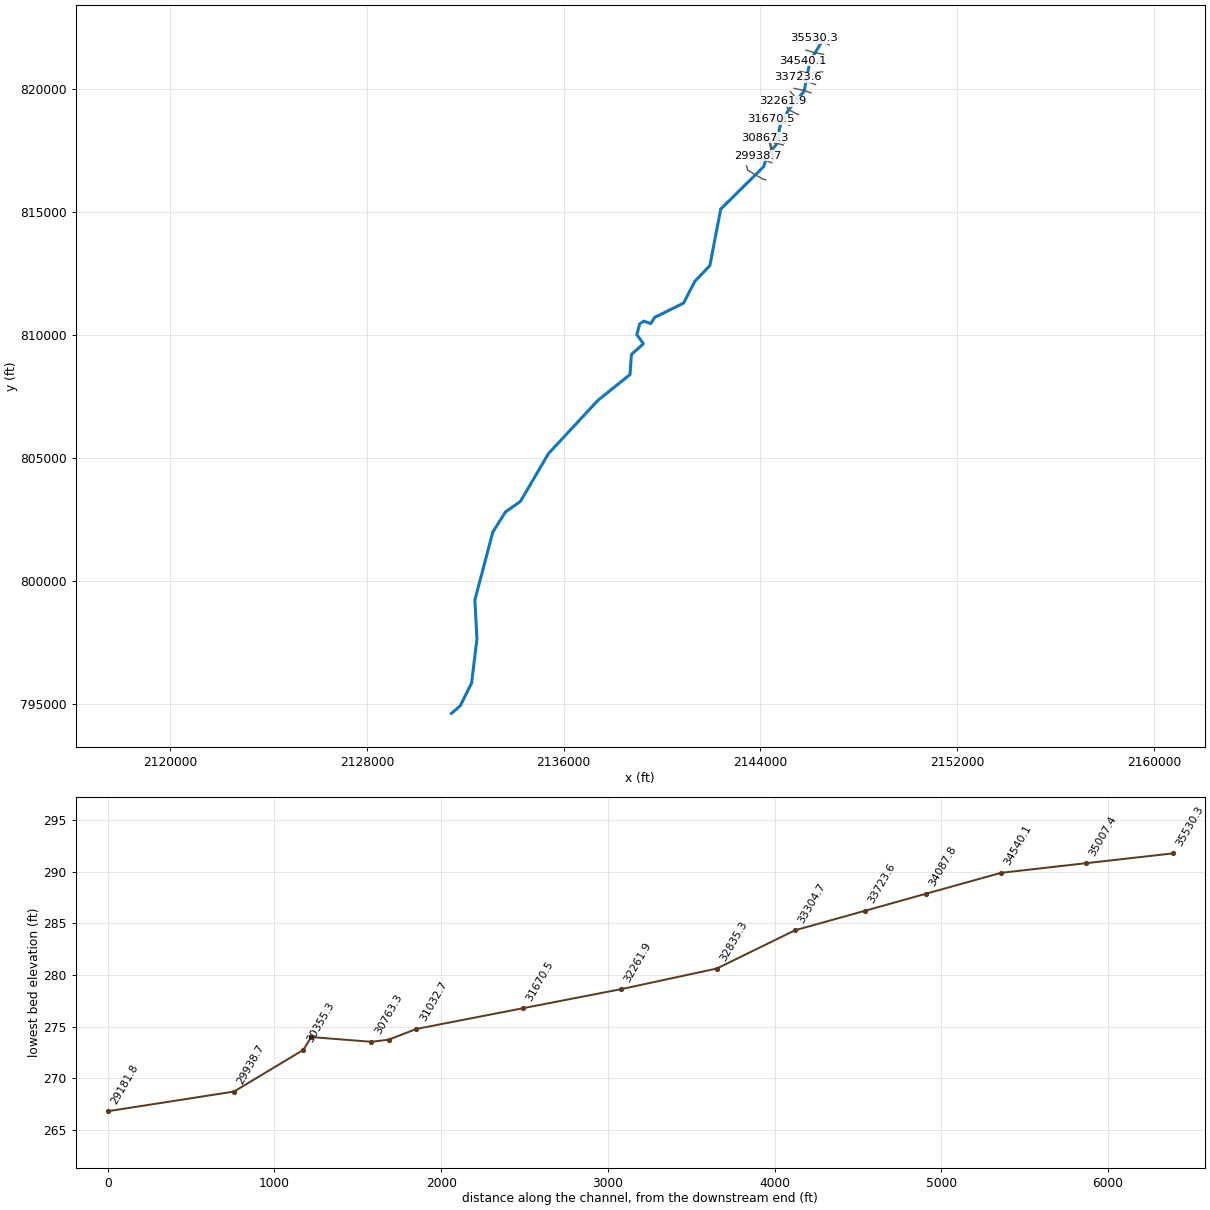
--- NE_Richland_Creek_FINAL.prj (project) ---

Proj Title=Northeast Richland Creek
Current Plan=p01
Default Exp/Contr=.3,.1
English Units
Geom File=g01
Flow File=f02
Flow File=f01
Plan File=p02
Plan File=p01
Y Axis Title=Elevation
X Axis Title(PF)=Main Channel Distance
X Axis Title(XS)=Station
BEGIN DESCRIPTION:
Northeast Richland Creek Detail Study -- Wake County, NC
END DESCRIPTION:
DSS Export Rating Curves= 0
DSS Export Rating Curve Sorted= 0
DSS Export Volume Flow Curves= 0
DXF OffsetX= 0
DXF OffsetY= 0
DXF ScaleX= 1
DXF ScaleY= 10

--- NE_Richland_Creek_FINAL.p01 (plan) ---

Plan Title=Multiple
Version=Version 3.0.1  Mar 2001
Short Identifier=Plan01
Geom File=g01
Flow File=f01
Subcritical Flow
K Sum by GR= 0
Std Step Tol= 0.01
Critical Tol= 0.01
Num of Std Step Trials= 20
Max Error Tol= 0.3
Flow Tol Ratio= 0.001
Split Flow NTrial= 30
Split Flow Tol= 0.02
Split Flow Ratio= 0.02
Log Output Level= 0
Friction Slope Method= 1
Unsteady Friction Slope Method= 2
Parabolic Critical Depth
Global Vel Dist= 0 , 0 , 0
Global Log Level= 0
CheckData=True
Encroach Param=-1 ,0,0, 0
Computation Interval=1HOUR
Output Interval=1HOUR
Run HTab= 0
Run UNet= 0
Run PostProcess= 0
UNET Theta= 1
UNET ZTol= 0.02
UNET ZSATol= 0.1
UNET MxIter= 20
UNET MaxInSteps= 20
UNET DtIC= 0
UNET DtMin= 0
UNET MaxCRTS= 20
UNET WFStab= 2
UNET SFStab= 1
UNET WFX= 1
UNET SFX= 1
UNET Convert EG Bridges=-1
UNET Use Existing IB Tables=-1
Instantaneous Interval=1HOUR
Write IC File= 0
Write Velocity= 0
Write Detailed= 0

--- NE_Richland_Creek_FINAL.p02 (plan) ---

Plan Title=Floodway
Version=Version 3.0.1  Mar 2001
Short Identifier=FLOODWAY
Geom File=g01
Flow File=f02
Subcritical Flow
K Sum by GR= 0
Std Step Tol= 0.01
Critical Tol= 0.01
Num of Std Step Trials= 20
Max Error Tol= 0.3
Flow Tol Ratio= 0.001
Split Flow NTrial= 30
Split Flow Tol= 0.02
Split Flow Ratio= 0.02
Log Output Level= 0
Friction Slope Method= 1
Unsteady Friction Slope Method= 2
Parabolic Critical Depth
Global Vel Dist= 0 , 0 , 0
Global Log Level= 0
CheckData=True
Encroach Param=-1 ,0,0, 2
Encroach River=Richland Creek
Encroach Reach=Reach - 1
Encroach Node=35530.3
       1    4953    5025
Encroach Node=35007.4
       1    4923    5065
Encroach Node=34540.1
       1    4800    5035
Encroach Node=34087.8
       1    4795    5020
Encroach Node=33723.6
       1    4900    5120
Encroach Node=33304.7
       1    4940    5100
Encroach Node=32835.3
       1    4925    5035
Encroach Node=32261.9
       1    4935    5185
Encroach Node=31670.5
       1    4905    5150
Encroach Node=31032.7
       1    4925    5100
Encroach Node=30867.3
       1    4968    5090
Encroach Node=30815.3
       1    4968    5090
Encroach Node=30763.3
       1    4968    5090
Encroach Node=30402.3
       1    4977    5140
Encroach Node=30378.8
       1    4977    5140
Encroach Node=30355.3
       1    4977    5140
Encroach Node=29938.7
       1    4900    5170
Encroach Node=29181.8
       1    4820    5150
Encroach Node=28486.7
       1    4785    5060
Encroach Node=27750.3
       1    4830    5070
Encroach Node=27155.8
       1    4820    5060
Encroach Node=26758.7
       1    4850    5100
Encroach Node=26149.7
       1    4900    5110
Encroach Node=25664.6
       1    4947    5025
Encroach Node=25639.1
       1    4947    5025
Encroach Node=25613.6
       1    4947    5025
Encroach Node=25325.4
       1    4950    5175
Encroach Node=24870.9
       1    4880    5125
Encroach Node=24565.4
       1    4920    5120
Encroach Node=24546.9
       1    4920    5120
Encroach Node=24528.4
       1    4920    5120
Encroach Node=24420.7
       1    4872    5125
Encroach Node=24299.2
       1    4800    5150
Encroach Node=24281.2
       1    4800    5150
Encroach Node=24263.2
       1    4800    5150
Encroach Node=23922.3
       1    4850    5165
Encroach Node=23415.9
       1    4900    5100
Encroach Node=22811.7
       1    4900    5045
Encroach Node=22781.2
       1    4900    5045
Encroach Node=22750.7
       1    4900    5045
Encroach Node=22026.0
       1    4875    5083
Encroach Node=21418.4
       1    4910    5030
Encroach Node=20938.7
       1    4920    5080
Encroach Node=20245.2
       1    4960    5050
Encroach Node=19591.7
       1    4960    5050
Encroach Node=19057.9
       1    4950    5070
Encroach Node=18621.0
       1    4920    5100
Encroach Node=18056.2
       1    4920    5100
Encroach Node=17311.9
       1    4850    5050
Encroach Node=16555.1
       1    4940    5203
Encroach Node=15993.2
       1    4920    5080
Encroach Node=15342.1
       1    4955    5045
Encroach Node=14591.0
       1    4920    5080
Encroach Node=14004.4
       1    4865    5100
Encroach Node=13395.1
       1    4943    5051
Encroach Node=13290.6
       1    4943    5051
Encroach Node=13186.1
       1    4943    5051
Encroach Node=12527.2
       1    4913    5087
Encroach Node=11543.3
       1    4950    5045
Encroach Node=11133.7
       1    4945    5050
Encroach Node=10482.0
       1    4915    5060
Encroach Node=9720.0
       1    4890    5060
Encroach Node=9130.7
       1    4850    5050
Encroach Node=8528.2
       1    4775    5080
Encroach Node=7941.4
       1    4700    5100
Encroach Node=7429.7
       1    4750    5150
Encroach Node=7078.3
       1    4770    5150
Encroach Node=6334.5
       1    4600    5080
Encroach Node=6259.0
       1    4600    5080
Encroach Node=6183.5
       1    4600    5080
Encroach Node=5532.9
       1    4700    5300
Encroach Node=5009.0
       1    4740    5270
Encroach Node=4665.9
       1    4780    5250
Encroach Node=4020.7
       1    4800    5200
Encroach Node=3500.2
       1    4775    5200
Encroach Node=3111.6
       1    4770    5250
Encroach Node=2491.1
       1    4730    5275
Encroach Node=1945.0
       1    4750    5250
Encroach Node=1229.8
       1    4700    5127
Computation Interval=1HOUR
Output Interval=1HOUR
Run HTab= 0
Run UNet= 0
Run PostProcess= 0
UNET Theta= 1
UNET ZTol= 0.02
UNET ZSATol= 0.1
UNET MxIter= 20
UNET MaxInSteps= 20
UNET DtIC= 0
UNET DtMin= 0
UNET MaxCRTS= 20
UNET WFStab= 2
UNET SFStab= 1
UNET WFX= 1
UNET SFX= 1
UNET Convert EG Bridges=-1
UNET Use Existing IB Tables=-1
Instantaneous Interval=1HOUR
Write IC File= 0
Write Velocity= 0
Write Detailed= 0

--- NE_Richland_Creek_FINAL.f01 (steady flow) ---

Flow Title= Multiple
Version=Version 3.0.1  Mar 2001
Number of Profiles= 5
Profile Names=10-year,50-year,100-year,500-year,100yr future
River Rch & RM=Richland Creek,Reach - 1       ,35530.3
    1590    3000    3600    5310    3600
River Rch & RM=Richland Creek,Reach - 1       ,34087.8
    1710    3360    4170    6300    4170
River Rch & RM=Richland Creek,Reach - 1       ,31670.5
    1760    3430    4460    6790    4460
River Rch & RM=Richland Creek,Reach - 1       ,30867.3
    1800    3330    4560    7130    4560
River Rch & RM=Richland Creek,Reach - 1       ,27155.8
    1860    3410    4560    7280    4560
River Rch & RM=Richland Creek,Reach - 1       ,24565.4
    1920    3480    4700    7650    4700
River Rch & RM=Richland Creek,Reach - 1       ,22811.7
    1950    3520    4730    7800    4760
River Rch & RM=Richland Creek,Reach - 1       ,16555.1
    2000    3590    4750    8010    4850
River Rch & RM=Richland Creek,Reach - 1       ,14591
    2060    3630    4760    8190    4950
River Rch & RM=Richland Creek,Reach - 1       ,11543.3
    2310    3880    4850    8510    5970
River Rch & RM=Richland Creek,Reach - 1       ,7429.7
    2400    4100    4900    8640    6350
River Rch & RM=Richland Creek,Reach - 1       ,3500.2
    2460    4230    5040    8740    6570
Boundary for River Rch & Prof#=Richland Creek,Reach - 1       , 1
Up Type= 0
Dn Type= 3
Dn Slope=.0029
Boundary for River Rch & Prof#=Richland Creek,Reach - 1       , 2
Up Type= 0
Dn Type= 3
Dn Slope=.0029
Boundary for River Rch & Prof#=Richland Creek,Reach - 1       , 3
Up Type= 0
Dn Type= 3
Dn Slope=.0029
Boundary for River Rch & Prof#=Richland Creek,Reach - 1       , 4
Up Type= 0
Dn Type= 3
Dn Slope=.0029
Boundary for River Rch & Prof#=Richland Creek,Reach - 1       , 5
Up Type= 0
Dn Type= 3
Dn Slope=.0029
DSS Import GetInterval= 0
DSS Import GetPeak= 0
DSS Import FillOption= 0

--- NE_Richland_Creek_FINAL.f02 (steady flow) ---

Flow Title= Floodway
Version=Version 3.0.1  Mar 2001
Number of Profiles= 2
Profile Names=100-year,Floodway
River Rch & RM=Richland Creek,Reach - 1       ,35530.3
    3600    3600
River Rch & RM=Richland Creek,Reach - 1       ,34087.8
    4170    4170
River Rch & RM=Richland Creek,Reach - 1       ,31670.5
    4460    4460
River Rch & RM=Richland Creek,Reach - 1       ,30867.3
    4560    4560
River Rch & RM=Richland Creek,Reach - 1       ,27155.8
    4560    4560
River Rch & RM=Richland Creek,Reach - 1       ,24565.4
    4700    4700
River Rch & RM=Richland Creek,Reach - 1       ,22811.7
    4730    4730
River Rch & RM=Richland Creek,Reach - 1       ,16555.1
    4750    4750
River Rch & RM=Richland Creek,Reach - 1       ,14591
    4760    4760
River Rch & RM=Richland Creek,Reach - 1       ,11543.3
    4850    4850
River Rch & RM=Richland Creek,Reach - 1       ,7429.7
    4900    4900
River Rch & RM=Richland Creek,Reach - 1       ,3500.2
    5040    5040
Boundary for River Rch & Prof#=Richland Creek,Reach - 1       , 1
Up Type= 0
Dn Type= 3
Dn Slope=.0029
Boundary for River Rch & Prof#=Richland Creek,Reach - 1       , 2
Up Type= 0
Dn Type= 1
Dn Known WS=197.67
DSS Import GetInterval= 0
DSS Import GetPeak= 0
DSS Import FillOption= 0

--- NE_Richland_Creek_FINAL.g01 (geometry) ---

Geom Title=Geom 01 by CodeH2 for Windows
Version=Version 3.0.1  Mar 2001

River Reach=Richland Creek  ,Reach - 1
Reach XY= 30
      2131437.36        794621.1      2131796.08       794927.46
      2132258.02       795851.35      2132475.67       797645.82
      2132391.28       799227.09      2133124.17       801994.32
      2133639.41       802807.16      2134243.49       803229.13
      2135381.38       805170.64       2137397.3       807340.48
      2138698.22        808383.2       2138757.8       809202.48
       2139244.4       809634.47      2138976.28       810006.86
      2139095.44       810448.78      2139264.26       810553.05
      2139542.32       810453.74      2139701.21       810706.98
        2140878.       811287.92      2141334.81       812171.75
      2141945.54       812812.27      2142387.45       815106.26
      2144134.78        816830.4      2144285.16       817309.99
      2144642.57       817722.52      2144788.88        818441.9
      2145146.55       819140.97      2145780.58       819896.94
      2146012.25       821104.04      2146538.35         821973.

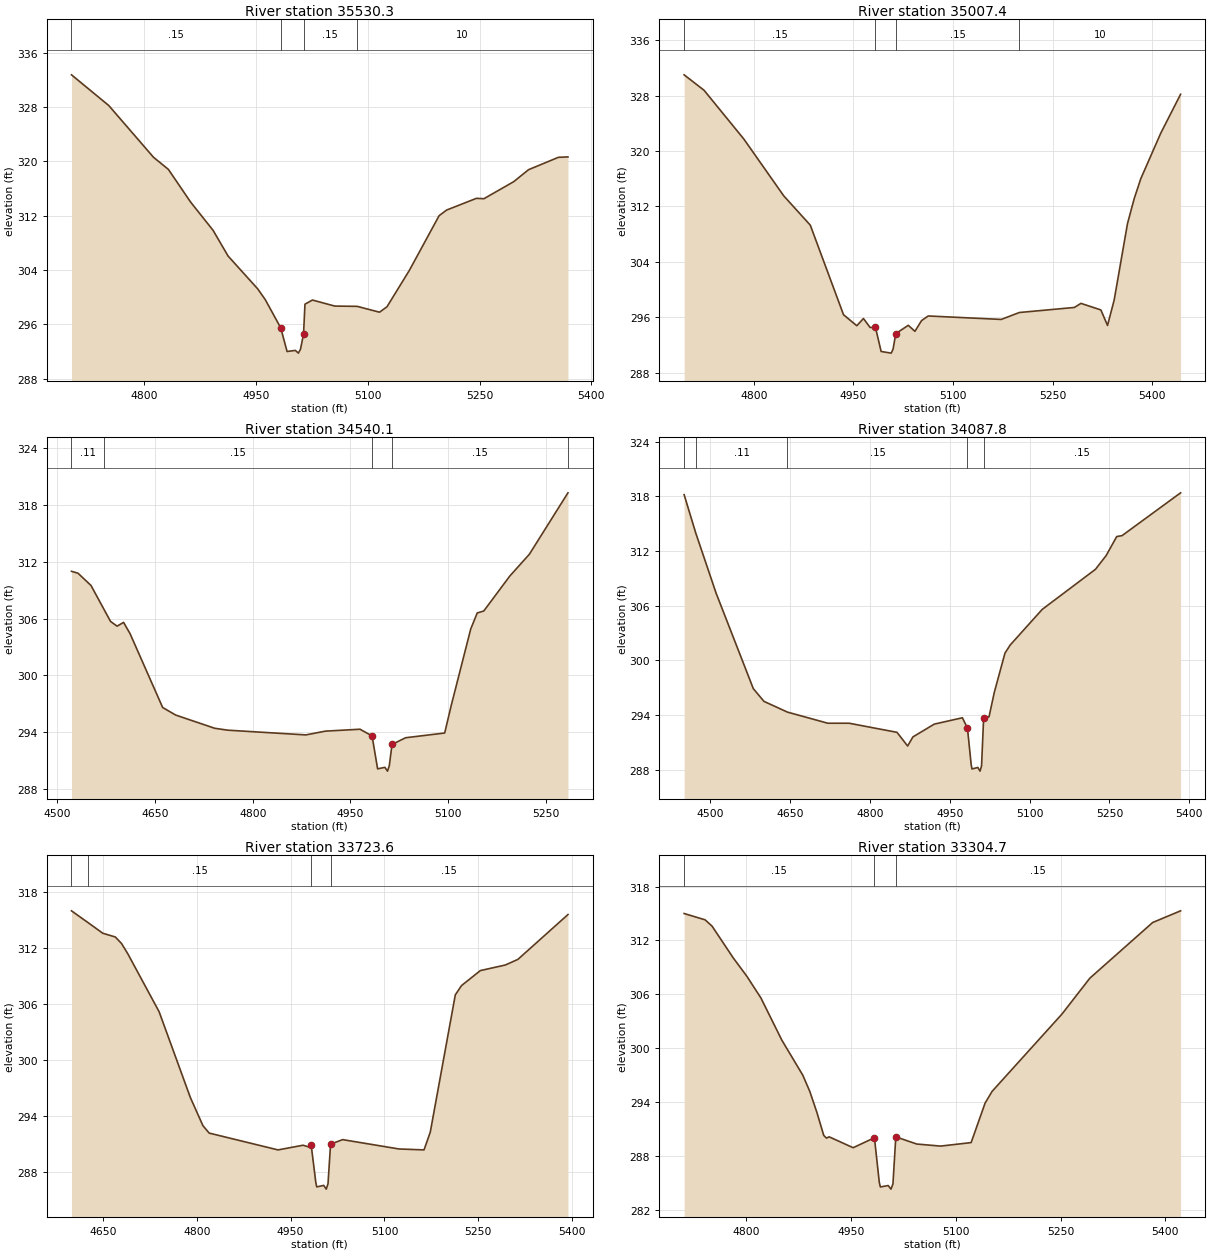
Type RM Length L Ch R = 1 ,35530.3 ,523,523,523
BEGIN DESCRIPTION:
Cross Section Richland Creek 53.0
END DESCRIPTION:
XS GIS Cut Line= 3
      2146793.58       821784.02      2146512.59       821897.94
      2146179.86        822042.6
#Sta/Elev= 30
  4702.6  332.74  4752.6  328.22  4812.6   320.6  4832.6  318.81  4862.6  313.97
  4892.6  309.83  4912.6  306.06  4952.6  301.19  4962.6  299.62  4983.3  295.47
  4991.8  291.99  5002.9  292.15    5007  291.75  5009.8  292.33  5013.9  294.57
  5015.8  298.96  5025.8  299.57  5055.8  298.68  5085.8  298.64  5115.8  297.78
  5125.8  298.57  5155.8  303.93  5195.8     312  5205.8  312.82  5245.8  314.55
  5255.8  314.49  5295.8     317  5315.8  318.77  5355.8  320.59  5368.6  320.65
#Mann= 4 ,-1 , 0
  4702.6     .15       0  4983.3     .04       0  5013.9     .15       0
  5085.8      10       0
Bank Sta=4983.3,5013.9
XS Rating Curve= 0
Exp/Cntr=.3,.1

Type RM Length L Ch R = 1 ,35007.4 ,507.8,507.8,507.8
BEGIN DESCRIPTION:
Cross Section Richland Creek 52.0
END DESCRIPTION:
XS GIS Cut Line= 3
      2146572.72       821394.16      2146259.43       821445.87
      2145846.29         821565.
#Sta/Elev= 30
  4695.2  331.02  4725.2  328.79  4785.2  321.73  4845.2  313.53  4885.2  309.29
  4935.2  296.35  4955.2  294.76  4965.2   295.8  4975.2  294.51  4983.3  294.52
  4991.8  291.04    5007   290.8  5009.8  291.38  5013.9  293.62  5032.7  294.82
  5042.7  293.95  5052.7   295.5  5062.7  296.17  5172.7  295.67    5200  296.67
  5282.7   297.4  5292.7  297.99  5322.7  297.04  5332.7   294.8  5342.7  298.47
  5362.7  309.49  5372.7  313.08  5382.7  315.99  5412.7  322.56  5442.7  328.21
#Mann= 4 , 1 , 0
  4695.2     .15       0  4983.3     .04       0  5013.9     .15       0
    5200      10       0
Bank Sta=4983.3,5013.9
XS Rating Curve= 0
Exp/Cntr=.3,.1

Type RM Length L Ch R = 1 ,34540.1 ,452.3,452.3,452.3
BEGIN DESCRIPTION:
Cross Section Richland Creek 51.0
END DESCRIPTION:
XS GIS Cut Line= 3
      2146486.35       821100.26      2146044.07        821073.1
      2145731.09       821136.55
#Sta/Elev= 30
  4521.7     311  4531.7   310.8  4551.7   309.5  4571.1  307.04  4581.7   305.7
  4591.7   305.2  4601.7   305.6  4611.7   304.4  4661.7   296.6  4681.7   295.8
  4741.7   294.4  4761.7   294.2  4881.7   293.7  4911.7   294.1  4964.8   294.3
  4983.3  293.59  4991.8  290.11  5002.9  290.27    5007  289.87  5009.8  290.45
  5013.9  292.69  5034.8   293.4  5094.8   293.9  5104.8   296.8  5134.8   304.9
  5144.8   306.6  5154.8   306.8  5194.8   310.5  5224.8   312.8  5284.1   319.3
#Mann= 5 , 1 , 0
  4521.7     .11       0  4571.1     .15       0  4983.3     .04       0
  5013.9     .15       0  5284.1      .2       0
Bank Sta=4983.3,5013.9
XS Rating Curve= 0
Exp/Cntr=.3,.1

Type RM Length L Ch R = 1 ,34087.8 ,364.2,364.2,364.2
BEGIN DESCRIPTION:
Cross Section Richland Creek 50.0
END DESCRIPTION:
XS GIS Cut Line= 3
      2146530.03        820679.6      2145989.09       820633.23
      2145604.37       820697.03
#Sta/Elev= 30
  4450.9   318.2  4472.8  313.98  4510.9   307.4  4580.9   296.9  4600.9   295.5
  4645.1  294.32  4720.9   293.1  4760.9   293.1  4850.9   292.1  4870.9   290.6
  4880.9   291.6  4920.9     293  4973.8   293.7  4983.3  292.56  4990.3  288.56
  4991.8  288.08  5002.9  288.24    5007  287.84  5009.8  288.42  5013.7  293.66
  5023.8   293.8  5033.8   296.5  5053.8   300.8  5063.8   301.7  5123.8   305.6
  5223.8     310  5243.8   311.5  5263.8   313.6  5273.8   313.7  5383.8   318.4
#Mann= 5 , 1 , 0
  4450.9     .15       0  4472.8     .11       0  4645.1     .15       0
  4983.3     .04       0  5013.7     .15       0
Bank Sta=4983.3,5013.7
XS Rating Curve= 0
Exp/Cntr=.3,.1

Type RM Length L Ch R = 1 ,33723.6 ,418.9,418.9,418.9
BEGIN DESCRIPTION:
Cross Section Richland Creek 49.0
END DESCRIPTION:
XS GIS Cut Line= 3
      2146240.21       820163.05      2145871.45       820299.94
       2145504.1       820458.11
#Sta/Elev= 30
  4599.9     316  4625.7  314.77  4649.9   313.6  4669.9   313.2  4679.9   312.5
  4689.9   311.4  4739.9   305.2  4789.9     296  4809.9     293  4819.9   292.2
  4929.9   290.4  4969.9   290.9  4979.9   290.7  4982.9  290.92  4990.3  286.92
  4991.8  286.44  5002.9   286.6    5007   286.2  5009.8  286.78  5013.9  291.02
  5033.2   291.5  5123.2   290.5  5163.2   290.4  5173.2   292.3  5213.2     307
  5223.2     308  5253.2   309.6  5293.2   310.2  5313.2   310.8  5393.2   315.6
#Mann= 4 , 1 , 0
  4599.9     .11       0  4625.7     .15       0  4982.9     .04       0
  5013.9     .15       0
Bank Sta=4982.9,5013.9
XS Rating Curve= 0
Exp/Cntr=.3,.1

Type RM Length L Ch R = 1 ,33304.7 ,469.4,469.4,469.4
BEGIN DESCRIPTION:
Cross Section Richland Creek 48.0-CCX226
END DESCRIPTION:
XS GIS Cut Line= 4
      2146058.75       819826.82      2145866.25       819893.69
      2145782.91       819919.73      2145373.39       820012.96
#Sta/Elev= 30
  4710.7     315  4740.7   314.3  4750.7   313.6  4780.7   310.1  4800.7     308
  4820.7   305.6  4850.7   300.9  4880.7     297  4890.7   295.2  4900.7   292.9
  4910.7   290.3  4914.5     290  4918.5  290.14  4952.8  288.93  4983.3  290.04
  4990.3  285.04  4991.8  284.56  5002.9  284.72    5007  284.32  5009.8   284.9
  5013.9  290.14  5043.9  289.34  5078.1  289.11  5121.8   289.5  5141.8   293.9
  5151.8   295.2  5251.8   303.8  5291.8   307.8  5381.8     314  5421.8   315.3
#Mann= 3 , 1 , 0
  4710.7     .15       0  4983.3     .04       0  5013.9     .15       0
Bank Sta=4983.3,5013.9
XS Rating Curve= 0
Exp/Cntr=.3,.1

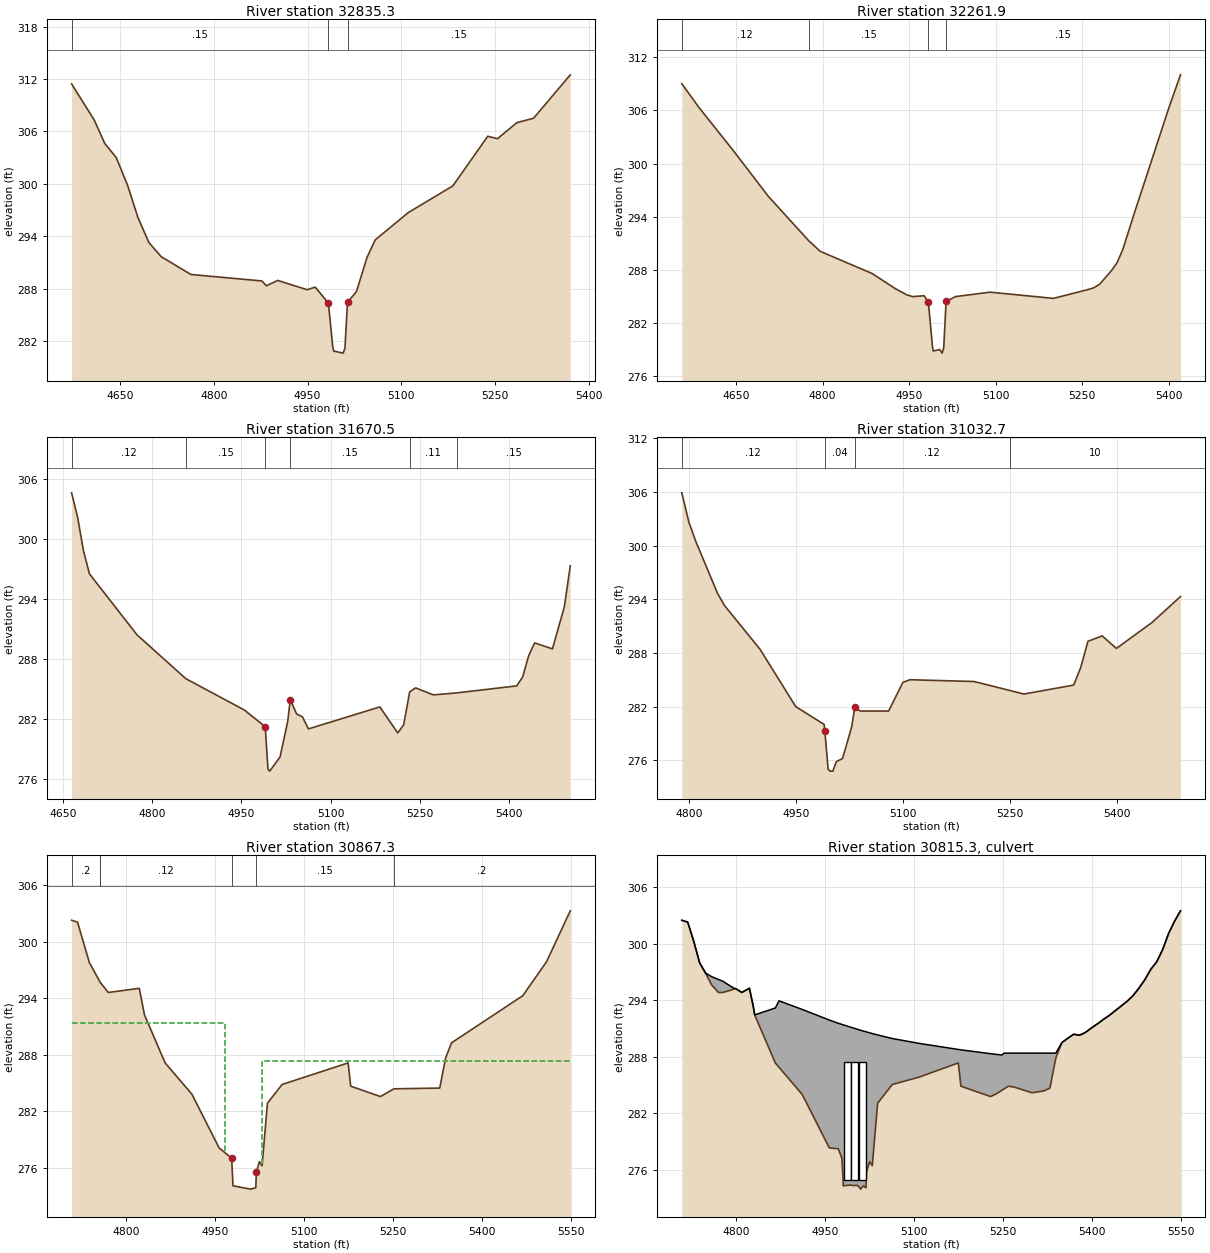
Type RM Length L Ch R = 1 ,32835.3 ,573.4,573.4,573.4
BEGIN DESCRIPTION:
Cross Section Richland Creek 47.0
END DESCRIPTION:
XS GIS Cut Line= 3
       2145867.1       819462.91      2145465.25       819607.25
      2145215.91       819881.45
#Sta/Elev= 30
  4572.6  311.43  4608.8   307.3  4625.6  304.62  4644.1  302.99  4662.4  299.78
  4678.6  296.16  4696.2  293.28  4715.7  291.67  4763.4  289.62  4876.9  288.88
  4884.1  288.33  4902.3  288.94  4949.1  287.88  4962.3  288.17  4983.3  286.34
  4990.3  281.34  4991.8  280.86    5007  280.62  5009.8   281.2  5013.9  286.44
  5028.2  287.66  5045.2  291.59  5058.2  293.58  5111.2  296.71  5182.4  299.76
  5238.2  305.44  5253.8  305.16  5284.8     307  5311.5   307.5  5370.2  312.47
#Mann= 3 , 1 , 0
  4572.6     .15       0  4983.3     .04       0  5013.9     .15       0
Bank Sta=4983.3,5013.9
XS Rating Curve= 0
Exp/Cntr=.3,.1

Type RM Length L Ch R = 1 ,32261.9 ,591.4,591.4,591.4
BEGIN DESCRIPTION:
Cross Section Richland Creek 46.0
END DESCRIPTION:
XS GIS Cut Line= 3
      2145543.65       818944.31       2145152.7       819133.27
      2144917.49       819493.22
#Sta/Elev= 30
  4555.9     309  4585.9   306.3  4645.9   301.4  4705.9   296.3    4776  291.29
  4795.9   290.1  4885.9   287.6  4925.9   285.9  4945.9   285.2  4955.9     285
  4975.9   285.1  4983.3  284.35  4990.3  279.35  4991.8  278.87  5002.9  279.03
    5007  278.63  5009.8  279.21  5013.9  284.45  5030.1     285  5090.1   285.5
  5200.1   284.8  5260.1   285.8  5270.1     286  5280.1   286.4  5300.1   287.9
  5310.1   288.8  5320.1   290.3  5340.1   294.4  5400.1   306.3  5420.1     310
#Mann= 4 , 1 , 0
  4555.9     .12       0    4776     .15       0  4983.3     .04       0
  5013.9     .15       0
Bank Sta=4983.3,5013.9
XS Rating Curve= 0
Exp/Cntr=.3,.1

Type RM Length L Ch R = 1 ,31670.5 ,637.8,637.8,637.8
BEGIN DESCRIPTION:
Cross Section Richland Creek 45.0
END DESCRIPTION:
XS GIS Cut Line= 3
      2145204.71       818512.64      2144892.29       818612.44
      2144404.36       818760.94
#Sta/Elev= 30
  4664.8   304.6  4674.8   302.2  4684.8   298.8  4694.8   296.5  4774.8   290.4
  4856.8  286.02  4954.8   282.9  4990.2  281.22  4994.8  276.98  4997.7  276.78
  5015.1   278.2  5027.9  281.73  5032.3  283.93  5042.8   282.5  5052.8   282.2
  5062.8     281  5182.8   283.2  5212.8   280.6  5222.8   281.4  5232.9   284.7
  5242.8   285.1  5272.8   284.4  5311.7   284.6  5412.8   285.3  5422.8   286.2
  5432.8   288.3  5442.8   289.6  5472.8     289  5492.8   293.2  5502.8   297.3
#Mann= 6 , 1 , 0
  4664.8     .12       0  4856.8     .15       0  4990.2     .04       0
  5032.3     .15       0  5232.9     .11       0  5311.7     .15       0
Bank Sta=4990.2,5032.3
XS Rating Curve= 0
Exp/Cntr=.3,.1

Type RM Length L Ch R = 1 ,31032.7 ,165.4,165.4,165.4
BEGIN DESCRIPTION:
Cross Section Richland Creek 44.0
END DESCRIPTION:
XS GIS Cut Line= 3
      2144929.52       818041.24      2144721.11       818010.85
      2144268.35       818198.19
#Sta/Elev= 30
  4789.2   305.9  4799.2   302.6  4809.2   300.4  4839.2   294.7  4849.2   293.3
  4899.2   288.4  4949.2     282  4989.2     280  4990.2  279.22  4994.8  274.98
  4997.7  274.78  5001.5  274.78  5006.2  275.83  5015.1   276.2  5027.9  279.73
  5032.3  281.93  5039.8   281.5  5079.8   281.5  5099.8   284.7  5109.8     285
  5199.8   284.8    5250   283.8  5269.8   283.4  5339.8   284.4  5349.8   286.4
  5359.8   289.3  5379.8   289.9  5399.8   288.5  5449.8   291.4  5489.8   294.3
#Mann= 4 , 1 , 0
  4789.2     .12       0  4990.2     .04       0  5032.3     .12       0
    5250      10       0
Bank Sta=4990.2,5032.3
XS Rating Curve= 0
Exp/Cntr=.5,.3

Type RM Length L Ch R = 1 ,30867.3 ,104,104,104
BEGIN DESCRIPTION:
Upstream Section of Bridge/Culvert/Weir
END DESCRIPTION:
XS GIS Cut Line= 3
      2144978.29       817804.89      2144696.74       817871.44
      2144160.59       817998.48
#Sta/Elev= 30
  4708.8  302.27  4718.8  302.07  4738.8  297.77  4756.1  295.79  4756.6  295.72
  4770.7  294.61  4822.8  295.05  4831.7  292.22  4866.4  287.14  4911.6  283.81
  4957.4  278.12  4978.5  277.04  4980.8   274.1  5010.3  273.75  5019.2  273.89
  5020.1  275.55  5025.2  276.66  5029.8  276.23  5038.8  282.86  5063.5  284.85
  5174.8  287.14  5179.1  284.67  5229.1  283.57    5252  284.39  5329.1  284.47
  5339.1  287.67  5349.1  289.27  5469.1  294.27  5509.1  297.87  5549.1  303.27
#Mann= 6 , 1 , 0
  4708.8      .2       0  4756.1    .125       0  4756.6     .12       0
  4978.5     .04       0  5020.1     .15       0    5252      .2       0
#XS Ineff= 2 , 0
       0    4968   291.4    5030       0   287.3
Permanent Ineff=
       F       F
Bank Sta=4978.5,5020.1
XS Rating Curve= 0
Exp/Cntr=.5,.3

Type RM Length L Ch R = 2 ,30815.3 ,,,
BEGIN DESCRIPTION:
HARRIS ROAD
Structure ID: WK_RLCR4A
END DESCRIPTION:
Bridge Culvert--1,0,-1,-1, 0
Deck Dist Width WeirC Skew NumUp NumDn MinLoCord MaxHiCord MaxSubmerge Is_Ogee
10,84,3,0, 60, 60, , , .95, 0, 1,1,,
  4708.8  4718.8  4728.8  4738.8  4748.8  4759.2  4770.7  4777.7  4796.1  4799.6
    4810  4822.8  4829.1  4831.7  4866.4  4872.6  4911.6  4957.4  4972.4  4978.5
  4980.6  4980.8  4993.6  5005.2  5010.3  5014.7  5019.2  5019.5  5020.1  5025.2
  5029.8  5038.8  5063.5    5109  5174.8  5179.1  5229.1  5248.1    5252  5259.1
  5269.1  5299.1  5319.1  5329.1  5339.1  5349.1  5369.1  5379.1  5389.1  5429.1
  5459.1  5469.1  5479.1  5489.1  5499.1  5509.1  5519.1  5529.1  5539.1  5549.1
   302.5   302.3   300.3     298   296.9  296.51  296.21  296.04   295.3  295.25
  294.85  295.29  293.41  292.46  293.19  293.95  293.04  291.91  291.57  291.45
  291.41   291.4  291.15  290.92  290.82  290.74  290.67  290.66  290.65  290.56
  290.48  290.33  289.95  289.43  288.79  288.75  288.34   288.2   288.4   288.4
   288.4   288.4   288.4   288.4   288.4  289.51  290.41  290.31  290.61  292.41
   293.9   294.5   295.3   296.2   297.3   298.1   299.4   301.1   302.4   303.5
  302.49  302.29  300.29  297.99  296.89  295.63  294.83  294.83  295.17  295.23
  294.83  295.27  293.39  292.44  287.36   286.9  284.03  278.34  278.26  277.26
  275.07  274.32  274.41  274.36  273.97  274.32  274.11  274.99  275.77  276.88
  276.45  283.08  285.07  285.86  287.36  284.89  283.79  284.45  284.61  284.89
  284.79  284.19  284.39  284.69  287.89  289.49  290.39  290.29  290.59  292.39
  293.89  294.49  295.29  296.19  297.29  298.09  299.39  301.09  302.39  303.49
  4708.8  4718.8  4728.8  4738.8  4748.8  4759.2  4770.7  4777.7  4796.1  4799.6
    4810  4822.8  4829.1  4831.7  4866.4  4872.6  4911.6  4957.4  4972.4  4978.5
  4980.6  4980.8  4993.6  5005.2  5010.3  5014.7  5019.2  5019.5  5020.1  5025.2
  5029.8  5038.8  5063.5    5109  5174.8  5179.1  5229.1  5248.1    5252  5259.1
  5269.1  5299.1  5319.1  5329.1  5339.1  5349.1  5369.1  5379.1  5389.1  5429.1
  5459.1  5469.1  5479.1  5489.1  5499.1  5509.1  5519.1  5529.1  5539.1  5549.1
   302.5   302.3   300.3     298   296.9  296.51  296.21  296.04   295.3  295.25
  294.85  295.29  293.41  292.46  293.19  293.95  293.04  291.91  291.57  291.45
  291.41   291.4  291.15  290.92  290.82  290.74  290.67  290.66  290.65  290.56
  290.48  290.33  289.95  289.43  288.79  288.75  288.34   288.2   288.4   288.4
   288.4   288.4   288.4   288.4   288.4  289.51  290.41  290.31  290.61  292.41
   293.9   294.5   295.3   296.2   297.3   298.1   299.4   301.1   302.4   303.5
  302.47  302.27  300.27  297.97  296.87  295.61  294.81  294.81  295.15  295.21
  294.81  295.25  293.37  292.42  287.34  286.88  284.01  278.32  278.24  277.24
  275.05   274.3  274.39  274.34  273.95   274.3  274.09  274.97  275.75  276.86
  276.43  283.06  285.05  285.84  287.34  284.87  283.77  284.43  284.59  284.87
  284.77  284.17  284.37  284.67  287.87  289.47  290.37  290.27  290.57  292.37
  293.87  294.47  295.27  296.17  297.27  298.07  299.37  301.07  302.37  303.47
BR Coef= 1 , 0 , 0 ,1.25, 0 ,,,.8,-1,2,0,
WSPro=,,,, 1 ,,,, 0 ,,,, 0 ,,,,-1 ,-1 ,-1 , 0 , 0 , 0 , 0 , 0
Culvert=2,12.5,12,84,.015,.4,1,8,1,274.93,4987.6,274.6,4987.6,Culvert #1  , 0 ,10
Culvert Bottom n=.015
Culvert=2,12.5,12,84,.015,.4,1,8,1,274.92,5000.3,274.64,5000.3,Culvert #2  , 0 ,10
Culvert Bottom n=.015
Culvert=2,12.5,12,84,.015,.4,1,8,1,274.91,5013,274.65,5013,Culvert #3  , 0 ,10
Culvert Bottom n=.015
BR U #Sta/Elev= 85
  4708.8  302.49  4718.8  302.29  4728.8  300.29  4738.8  297.99  4748.8  296.89
  4756.1  296.01  4756.6  295.94  4759.2  295.63  4766.1  295.15  4770.7  294.83
  4776.1  294.83  4777.7  294.83  4786.1  294.98  4796.1  295.17  4799.6  295.23
    4810  294.83  4822.8  295.27  4823.5  295.06  4829.1  293.39  4831.7  292.44
  4866.4  287.36  4872.6   286.9  4911.6  284.03    4920  282.99  4957.4  278.34
  4966.3  278.29  4972.4  278.26  4978.5  277.26  4980.6  275.07  4980.8  274.32
  4993.6  274.41  4997.5  274.35  5005.2  274.36  5010.3  273.97  5011.5  274.07
  5014.7  274.32  5019.2  274.11  5019.5  274.99  5020.1  275.77  5025.2  276.88
  5029.8  276.45  5038.8  283.08  5055.5  284.43  5063.5  285.07  5104.4  285.78
    5109  285.86  5148.8  286.77  5155.1  286.91  5174.8  287.36  5179.1  284.89
    5204  284.34  5229.1  283.79  5239.1  284.09  5248.1  284.45  5249.1  284.49
    5252  284.61  5259.1  284.89  5269.1  284.79  5299.1  284.19  5309.1  284.29
  5319.1  284.39  5329.1  284.69  5339.1  287.89  5349.1  289.49  5359.1  289.99
  5369.1  290.39  5379.1  290.29  5389.1  290.59  5399.1  291.09  5409.1  291.49
  5419.1  291.99  5429.1  292.39  5439.1  292.89  5449.1  293.39  5456.1  293.74
  5459.1  293.89  5469.1  294.49  5479.1  295.29  5489.1  296.19  5499.1  297.29
  5509.1  298.09  5519.1  299.39  5529.1  301.09  5539.1  302.39  5549.1  303.49
BR U #Mann= 6
  4708.8      .2  4756.1    .125  4756.6     .12  4978.5     .04  5020.1     .15
    5252      .2
BR U Banks=4978.5,5020.1
BR D #Sta/Elev= 85
  4708.8  302.47  4718.8  302.27  4728.8  300.27  4738.8  297.97  4748.8  296.87
  4756.1  295.99  4756.6  295.92  4759.2  295.61  4766.1  295.13  4770.7  294.81
  4776.1  294.81  4777.7  294.81  4786.1  294.96  4796.1  295.15  4799.6  295.21
    4810  294.81  4822.8  295.25  4823.5  295.04  4829.1  293.37  4831.7  292.42
  4866.4  287.34  4872.6  286.88  4911.6  284.01    4920  282.97  4957.4  278.32
  4966.3  278.27  4972.4  278.24  4978.5  277.24  4980.6  275.05  4980.8   274.3
  4993.6  274.39  4997.5  274.33  5005.2  274.34  5010.3  273.95  5011.5  274.05
  5014.7   274.3  5019.2  274.09  5019.5  274.97  5020.1  275.75  5025.2  276.86
  5029.8  276.43  5038.8  283.06  5055.5  284.41  5063.5  285.05  5104.4  285.76
    5109  285.84  5148.8  286.75  5155.1  286.89  5174.8  287.34  5179.1  284.87
    5204  284.32  5229.1  283.77  5239.1  284.07  5248.1  284.43  5249.1  284.47
    5252  284.59  5259.1  284.87  5269.1  284.77  5299.1  284.17  5309.1  284.27
  5319.1  284.37  5329.1  284.67  5339.1  287.87  5349.1  289.47  5359.1  289.97
  5369.1  290.37  5379.1  290.27  5389.1  290.57  5399.1  291.07  5409.1  291.47
  5419.1  291.97  5429.1  292.37  5439.1  292.87  5449.1  293.37  5456.1  293.72
  5459.1  293.87  5469.1  294.47  5479.1  295.27  5489.1  296.17  5499.1  297.27
  5509.1  298.07  5519.1  299.37  5529.1  301.07  5539.1  302.37  5549.1  303.47
BR D #Mann= 6
  4708.8      .2  4756.1    .125  4756.6     .12  4978.5     .04  5020.1     .15
    5252      .2
BR D Banks=4978.5,5020.1
BC Design=,, 0 ,, 0 ,,,,,,

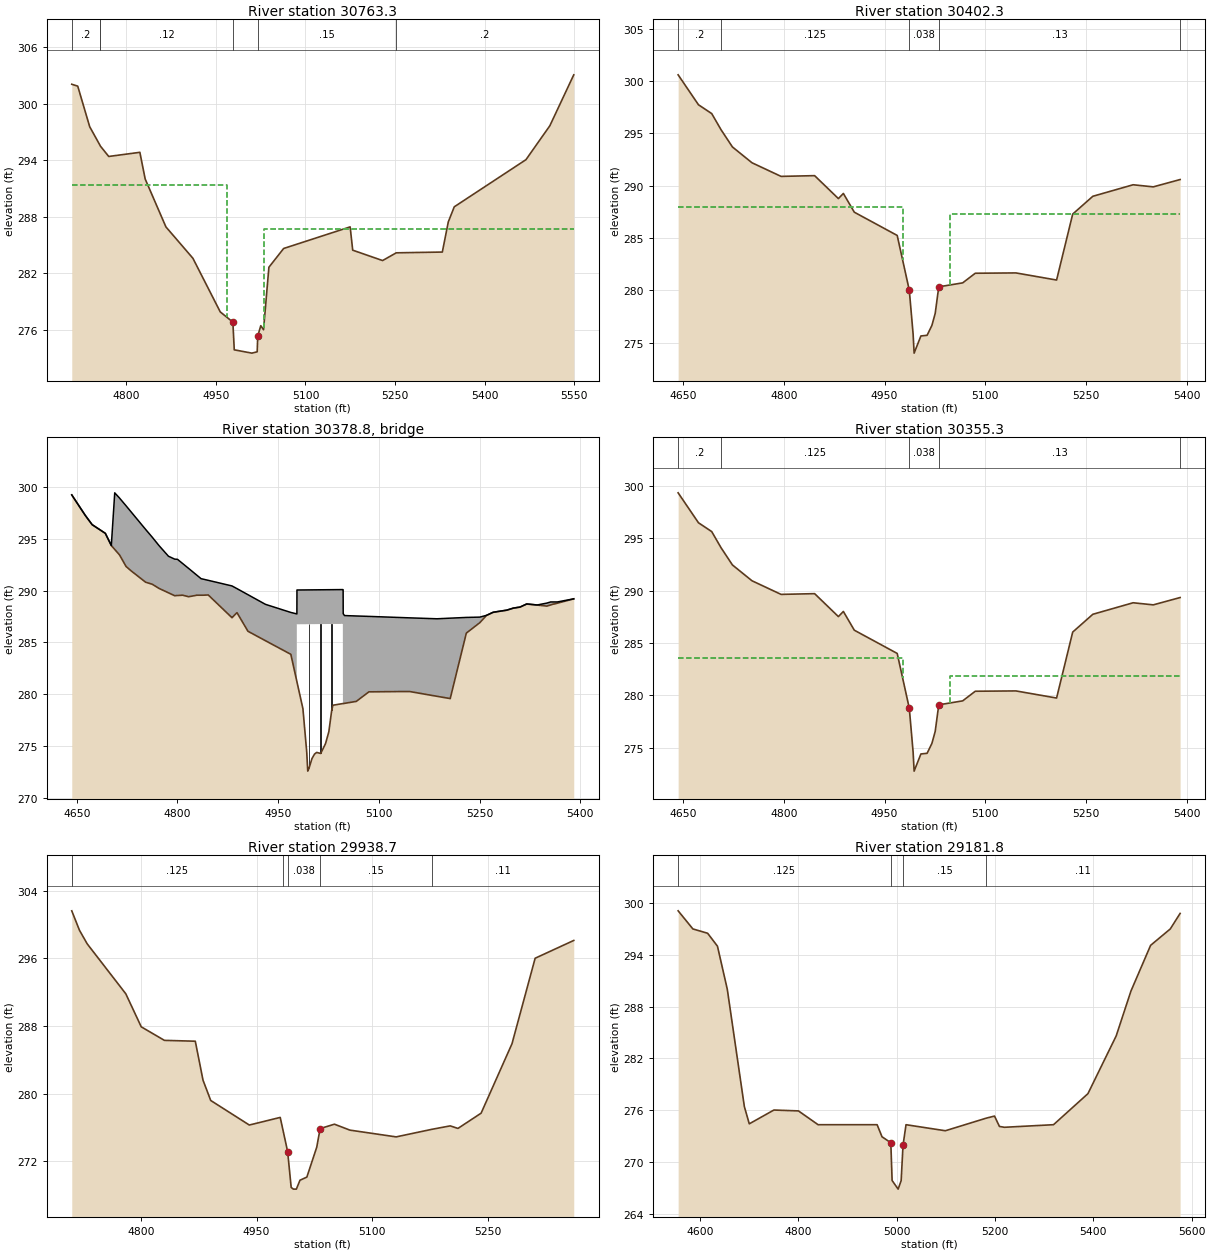
Type RM Length L Ch R = 1 ,30763.3 ,361,361,361
BEGIN DESCRIPTION:
Downstream Section of Bridge/Culvert/Weir
END DESCRIPTION:
XS GIS Cut Line= 3
      2144931.78       817711.87      2144650.24       817778.42
      2144114.08       817905.45
#Sta/Elev= 30
  4708.8  302.06  4718.8  301.86  4738.8  297.56  4756.1  295.58  4756.6  295.51
  4770.7   294.4  4822.8  294.84  4831.7  292.01  4866.4  286.93  4911.6   283.6
  4957.4  277.91  4978.5  276.83  4980.8  273.89  5010.3  273.54  5019.2  273.68
  5020.1  275.34  5025.2  276.45  5029.8  276.02  5038.8  282.65  5063.5  284.64
  5174.8  286.93  5179.1  284.46  5229.1  283.36    5252  284.18  5329.1  284.26
  5339.1  287.46  5349.1  289.06  5469.1  294.06  5509.1  297.66  5549.1  303.06
#Mann= 6 , 1 , 0
  4708.8      .2       0  4756.1    .125       0  4756.6     .12       0
  4978.5     .04       0  5020.1     .15       0    5252      .2       0
#XS Ineff= 2 , 0
       0    4968   291.4    5030       0   286.7
Permanent Ineff=
       F       F
Bank Sta=4978.5,5020.1
XS Rating Curve= 0
Exp/Cntr=.5,.3

Type RM Length L Ch R = 1 ,30402.3 ,47,47,47
BEGIN DESCRIPTION:
Upstream Section of Bridge/Culvert/Weir
END DESCRIPTION:
XS GIS Cut Line= 5
      2144542.36         817119.       2144512.8       817319.66
      2144471.13       817507.16      2144436.41       817692.32
        2144393.       817850.91
#Sta/Elev= 30
  4642.6  300.58  4672.9  297.72  4692.6  296.88  4706.6  295.33  4723.5  293.69
  4752.6  292.18  4795.9  290.88  4845.9  290.95  4881.3  288.76  4888.7  289.25
    4905  287.46  4968.9  285.24  4986.9  280.01  4992.6  275.82  4994.1     274
  5004.2  275.64  5013.4   275.7  5020.6  276.65  5025.5  277.79  5029.8  279.86
  5031.5  280.34  5066.4  280.71  5085.2  281.63  5145.8  281.66  5206.3  280.98
  5230.3  287.28  5260.3  288.98  5320.3  290.08  5350.3  289.88  5390.3  290.58
#Mann= 5 , 1 , 0
  4642.6      .2       0  4706.6    .125       0  4986.9    .038       0
  5031.5     .13       0  5390.3      .2       0
#XS Ineff= 2 , 0
       0    4977     288    5048       0   287.3
Permanent Ineff=
       F       F
Bank Sta=4986.9,5031.5
XS Rating Curve= 0
Exp/Cntr=.5,.3

Type RM Length L Ch R = 3 ,30378.8 ,,,
BEGIN DESCRIPTION:
OAK AVE
Structure ID: WK_RLCR4
END DESCRIPTION:
Bridge Culvert--1,0,-1,-1, 0
Deck Dist Width WeirC Skew NumUp NumDn MinLoCord MaxHiCord MaxSubmerge Is_Ogee
10,27,2.6,0, 50, 49, , , .95, 0, 1,1,,
  4642.6  4662.6  4672.9  4692.6  4701.5  4706.6  4713.7  4723.5  4752.6  4762.6
  4772.6  4786.6  4795.9  4800.1  4807.7  4816.8  4835.2  4845.9  4881.3  4888.7
    4905  4931.1  4968.9  4977.7  4977.8 4977.89    4978 5046.39  5046.5  5046.8
 5046.91  5048.8  5066.4  5085.2  5145.8  5186.6  5206.3  5230.3  5250.3  5260.3
  5270.3  5290.3  5300.3  5310.3  5320.3  5335.9  5350.3  5355.9  5365.9  5390.3
   299.2  297.24  296.34   295.5  294.33   299.4   298.9  298.15  295.88  295.12
  294.32   293.3  293.02     293   292.6  292.12  291.14  290.98  290.44  290.18
   289.6  288.67  287.89  287.75  287.75  287.75  290.05  290.09  290.09  290.07
  287.77  287.59  287.55  287.51  287.37  287.28  287.34  287.41  287.44  287.61
  287.91  288.11  288.31  288.41  288.71  288.61  288.79   288.9   288.9   289.2
   299.2  297.24  296.34   295.5  294.33  293.95  293.43  292.31   290.8   290.6
   290.2  289.78   289.5  289.52  289.55   289.4  289.55  289.57  287.38  287.87
  286.08  285.17  283.86   281.3  286.75  286.75  286.75  286.79  279.12  279.12
  279.12  279.14  279.33  280.25  280.28  279.82   279.6   285.9   286.9   287.6
   287.9   288.1   288.3   288.4   288.7   288.6   288.5  288.61  288.78   289.2
  4642.6  4662.6  4672.9  4692.6  4701.5  4706.6  4713.7  4723.5  4752.6  4762.6
  4772.6  4786.6  4795.9  4800.1  4807.7  4816.8  4835.2  4845.9  4881.3  4888.7
    4905  4931.1  4968.9  4977.7  4977.8 4977.89    4978 5046.39  5046.5  5046.8
 5046.91  5048.8  5066.4  5085.2  5145.8  5186.6  5206.3  5230.3  5235.9  5245.9
  5250.3  5260.3  5270.3  5290.3  5300.3  5310.3  5320.3  5350.3  5390.3
  300.19  298.23  297.33  296.49  295.32   299.4   298.9  298.15  295.88  295.12
  294.32   293.3  293.02     293   292.6  292.12  291.14  290.98  290.44  290.18
   289.6  288.67  287.89  287.75  287.75  287.75  290.05  290.09  290.09  290.07
  287.77  287.59  287.55  287.51  287.37  287.28  287.34  287.41   287.4  287.67
  287.89  288.59  288.89  289.09  289.29  289.39  289.69  289.49  290.19
  300.19  298.23  297.33  296.49  295.32  294.94  294.42   293.3  291.79  291.59
  291.19  290.77  290.49  290.51  290.54  290.39  290.54  290.56  288.37  288.86
  287.07  286.16  284.85  282.29  287.74  287.74  287.74  287.78  280.11  280.11
  280.11  280.13  280.32  281.24  281.27  280.81  280.59  286.89  287.17  287.67
  287.89  288.59  288.89  289.09  289.29  289.39  289.69  289.49  290.19
Pier Skew, UpSta & Num, DnSta & Num=  ,4996, 2 ,4996, 2 , 0 , 0 , 0 ,,
       1       1
  271.83  287.76
       1       1
  272.82  288.75
Pier Skew, UpSta & Num, DnSta & Num=  ,5013.4, 2 ,5013.4, 2 , 0 , 0 , 0 ,,
       1       1
  273.33  287.77
       1       1
  274.32  288.76
Pier Skew, UpSta & Num, DnSta & Num=  ,5029.8, 2 ,5029.8, 2 , 0 , 0 , 0 ,,
       1       1
  277.24  287.78
       1       1
  278.23  288.77
BR Coef= 1 , 1 , 0 ,1.25, 0 ,,,.8,0,2,0,
WSPro=,,,, 1 ,,,, 0 ,,,, 0 ,,,,-1 ,-1 ,-1 , 0 , 0 , 0 , 0 , 0
BR U #Sta/Elev= 100
  4642.6   299.2  4662.6  297.24  4672.9  296.34  4692.6   295.5  4701.5  294.33
  4706.6  293.95  4713.7  293.43  4716.6   293.1  4723.5  292.31  4726.6  292.14
  4731.4  291.87  4736.6  291.61  4746.6   291.1  4752.6   290.8  4756.6  290.72
  4762.6   290.6  4766.6  290.44  4772.6   290.2  4776.6  290.08  4786.6  289.78
  4792.6   289.6  4795.9   289.5  4796.6   289.5  4800.1  289.52  4807.7  289.55
  4816.8   289.4  4829.1  289.55  4835.2  289.55  4838.6  289.55  4845.9  289.57
  4881.3  287.38  4881.4  287.39  4888.7  287.87    4905  286.08  4931.1  285.17
  4968.9  283.86  4976.4  281.68  4977.5  281.36 4977.61  281.33  4977.7   281.3
  4977.8  281.27 4977.89  281.25    4978  281.22 4978.11  281.18  4986.9  278.63
  4992.6  274.44  4994.1  272.62    4996   272.9  5000.4  273.83  5004.2  274.26
  5007.4  274.42  5013.4  274.32  5020.6  275.27  5025.5  276.41  5029.8  278.48
  5031.5  278.96  5046.3  279.12 5046.39  279.12  5046.5  279.12 5046.59  279.12
  5046.7  279.12  5046.8  279.12 5046.91  279.12  5048.8  279.14  5066.4  279.33
  5085.2  280.25  5090.1  280.25  5138.7  280.28  5145.8  280.28  5186.6  279.82
  5206.3   279.6  5230.3   285.9  5234.9  286.13  5235.9  286.18  5245.9  286.68
  5250.3   286.9  5255.9  287.29  5260.3   287.6  5265.9  287.77  5270.3   287.9
  5275.9  287.96  5285.9  288.06  5290.3   288.1  5295.9  288.21  5300.3   288.3
  5305.9  288.36  5310.3   288.4  5315.9  288.57  5320.3   288.7  5325.9  288.66
  5335.9   288.6  5345.9  288.53  5350.3   288.5  5355.9  288.61  5360.3   288.7
  5361.4   288.7  5365.9  288.78  5375.9  288.95  5385.9  289.12  5390.3   289.2
BR U #Mann= 5
  4642.6      .2  4706.6    .125  4986.9    .038  5031.5     .13  5390.3      .2
BR U Banks=4986.9,5031.5
BR D #Sta/Elev= 100
  4642.6  300.19  4662.6  298.23  4672.9  297.33  4692.6  296.49  4701.5  295.32
  4706.6  294.94  4713.7  294.42  4716.6  294.09  4723.5   293.3  4726.6  293.13
  4731.4  292.86  4736.6   292.6  4746.6  292.09  4752.6  291.79  4756.6  291.71
  4762.6  291.59  4766.6  291.43  4772.6  291.19  4776.6  291.07  4786.6  290.77
  4792.6  290.59  4795.9  290.49  4796.6  290.49  4800.1  290.51  4807.7  290.54
  4816.8  290.39  4829.1  290.54  4835.2  290.54  4838.6  290.54  4845.9  290.56
  4881.3  288.37  4881.4  288.38  4888.7  288.86    4905  287.07  4931.1  286.16
  4968.9  284.85  4976.4  282.67  4977.5  282.35 4977.61  282.32  4977.7  282.29
  4977.8  282.26 4977.89  282.24    4978  282.21 4978.11  282.17  4986.9  279.62
  4992.6  275.43  4994.1  273.61    4996  273.89  5000.4  274.82  5004.2  275.25
  5007.4  275.41  5013.4  275.31  5020.6  276.26  5025.5   277.4  5029.8  279.47
  5031.5  279.95  5046.3  280.11 5046.39  280.11  5046.5  280.11 5046.59  280.11
  5046.7  280.11  5046.8  280.11 5046.91  280.11  5048.8  280.13  5066.4  280.32
  5085.2  281.24  5090.1  281.24  5138.7  281.27  5145.8  281.27  5186.6  280.81
  5206.3  280.59  5230.3  286.89  5234.9  287.12  5235.9  287.17  5245.9  287.67
  5250.3  287.89  5255.9  288.28  5260.3  288.59  5265.9  288.76  5270.3  288.89
  5275.9  288.95  5285.9  289.05  5290.3  289.09  5295.9   289.2  5300.3  289.29
  5305.9  289.35  5310.3  289.39  5315.9  289.56  5320.3  289.69  5325.9  289.65
  5335.9  289.59  5345.9  289.52  5350.3  289.49  5355.9   289.6  5360.3  289.69
  5361.4  289.69  5365.9  289.77  5375.9  289.94  5385.9  290.11  5390.3  290.19
BR D #Mann= 5
  4642.6      .2  4706.6    .125  4986.9    .038  5031.5     .13  5390.3      .2
BR D Banks=4986.9,5031.5
BC Design=,, 0 ,, 0 ,,,,,,

Type RM Length L Ch R = 1 ,30355.3 ,416.6,416.6,416.6
BEGIN DESCRIPTION:
Downstream Section of Bridge/Culvert/Weir
END DESCRIPTION:
XS GIS Cut Line= 5
      2144505.11       817090.34      2144475.54         817291.
      2144433.87        817478.5      2144399.15       817663.66
      2144355.74       817822.25
#Sta/Elev= 30
  4642.6  299.34  4672.9  296.48  4692.6  295.64  4706.6  294.09  4723.5  292.45
  4752.6  290.94  4795.9  289.64  4845.9  289.71  4881.3  287.52  4888.7  288.01
    4905  286.22  4968.9     284  4986.9  278.77  4992.6  274.58  4994.1  272.76
  5004.2   274.4  5013.4  274.46  5020.6  275.41  5025.5  276.55  5029.8  278.62
  5031.5   279.1  5066.4  279.47  5085.2  280.39  5145.8  280.42  5206.3  279.74
  5230.3  286.04  5260.3  287.74  5320.3  288.84  5350.3  288.64  5390.3  289.34
#Mann= 5 , 1 , 0
  4642.6      .2       0  4706.6    .125       0  4986.9    .038       0
  5031.5     .13       0  5390.3      .2       0
#XS Ineff= 2 , 0
       0    4977   283.6    5048       0   281.8
Permanent Ineff=
       F       F
Bank Sta=4986.9,5031.5
XS Rating Curve= 0
Exp/Cntr=.5,.3

Type RM Length L Ch R = 1 ,29938.7 ,756.9,756.9,756.9
BEGIN DESCRIPTION:
Cross Section Richland Creek 43.0
END DESCRIPTION:
XS GIS Cut Line= 3
      2144468.59       816981.21       2144202.5         817097.
       2143884.7       817266.15
#Sta/Elev= 30
  4710.6   301.6  4720.6   299.3  4730.6   297.7  4780.6   291.8  4800.6   287.9
  4830.6   286.3  4870.6   286.2  4880.6   281.6  4890.6   279.2  4940.6   276.3
  4980.6   277.2  4983.7   275.9  4990.2  273.17  4994.8  268.93  4997.7  268.73
  5001.5  268.73  5006.2  269.78  5015.1  270.15  5027.9  273.68  5032.3  275.88
  5050.8   276.4  5070.8   275.7  5130.8   274.9  5176.8  275.79  5200.8   276.2
  5210.8   275.9  5240.8   277.7  5280.8   285.9  5310.8     296  5360.8   298.1
#Mann= 5 , 1 , 0
  4710.6    .125       0  4983.7     .15       0  4990.2    .038       0
  5032.3     .15       0  5176.8     .11       0
Bank Sta=4990.2,5032.3
XS Rating Curve= 0
Exp/Cntr=.3,.1

Type RM Length L Ch R = 1 ,29181.8 ,695.1,695.1,695.1
BEGIN DESCRIPTION:
Cross Section Richland Creek 42.0
END DESCRIPTION:
XS GIS Cut Line= 5
      2144221.38       816299.22      2144108.75       816320.96
      2143822.29       816482.42      2143483.75       816690.75
      2143432.63       816863.29
#Sta/Elev= 30
  4555.6   299.1  4585.6     297  4615.6   296.5  4635.6     295  4655.6     290
  4690.3   276.4  4700.3   274.4  4750.3     276  4800.3   275.9  4840.3   274.3
  4960.3   274.3  4970.3   272.9  4988.2  272.21  4990.8  267.83  5003.1  266.83
  5009.2  267.82    5013  271.91  5019.1   274.3  5099.1   273.6  5182.3  275.06
  5199.1   275.3  5209.1   274.1  5219.1     274  5319.1   274.3  5389.1   277.9
  5446.6   284.6  5476.6   289.8  5516.6   295.1  5556.6     297  5576.6   298.8
#Mann= 4 , 1 , 0
  4555.6    .125       0  4988.2    .038       0    5013     .15       0
  5182.3     .11       0
Bank Sta=4988.2,5013
XS Rating Curve= 0
Exp/Cntr=.3,.1