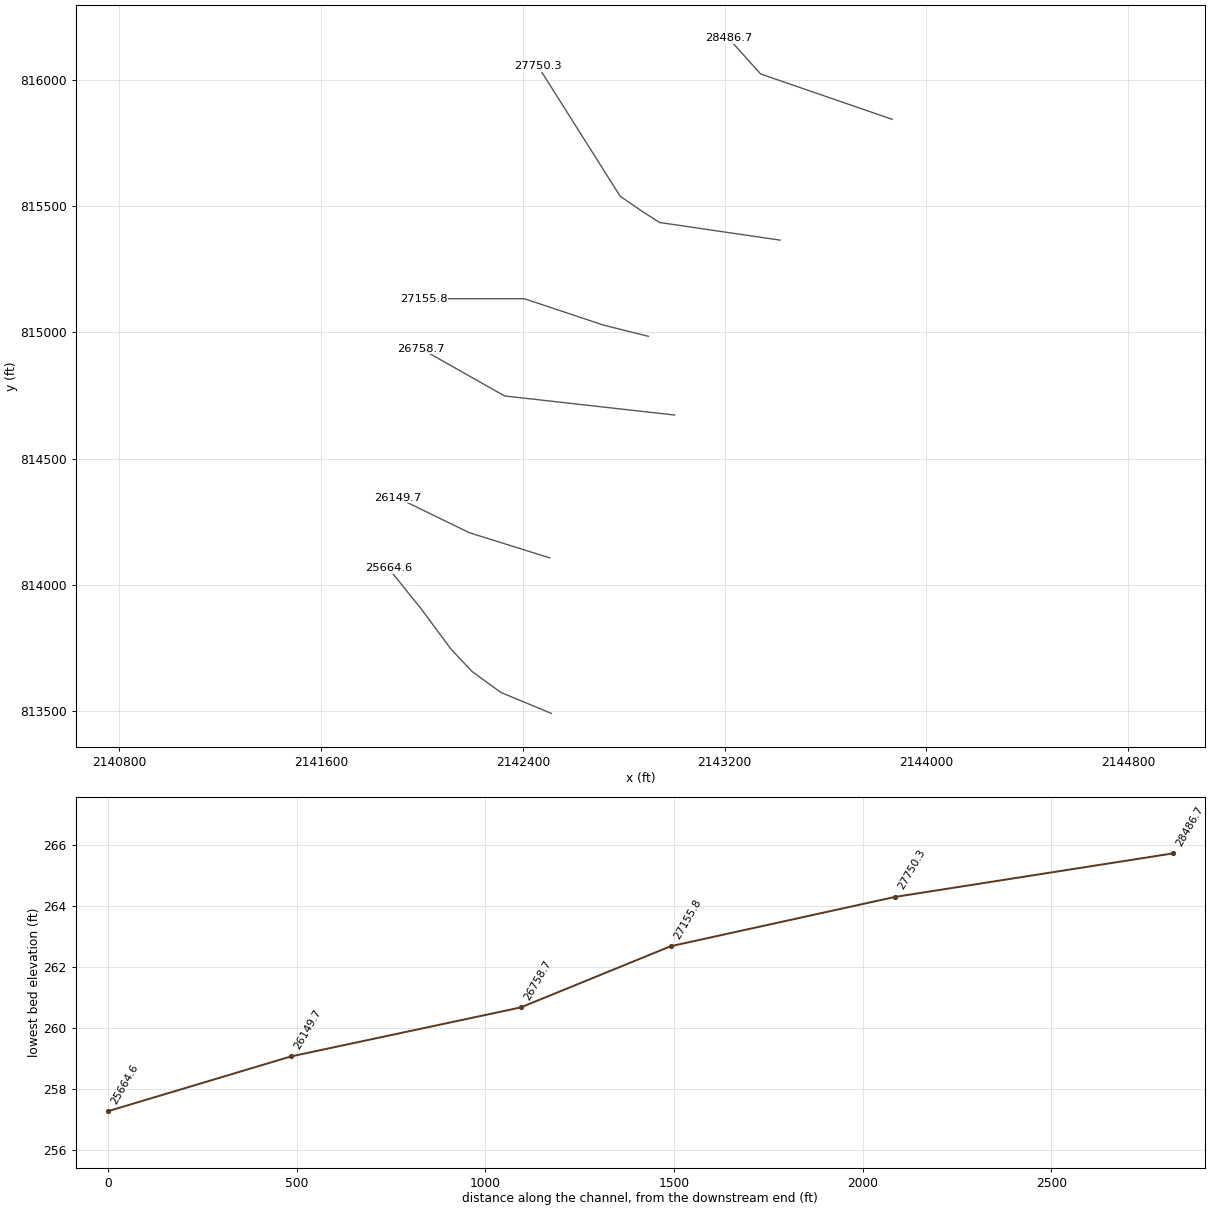
HEC-RAS study NE_Richland_Creek_FINAL.prj: Northeast Richland Creek

--- NE_Richland_Creek_FINAL.g01 (geometry) --- (continued)

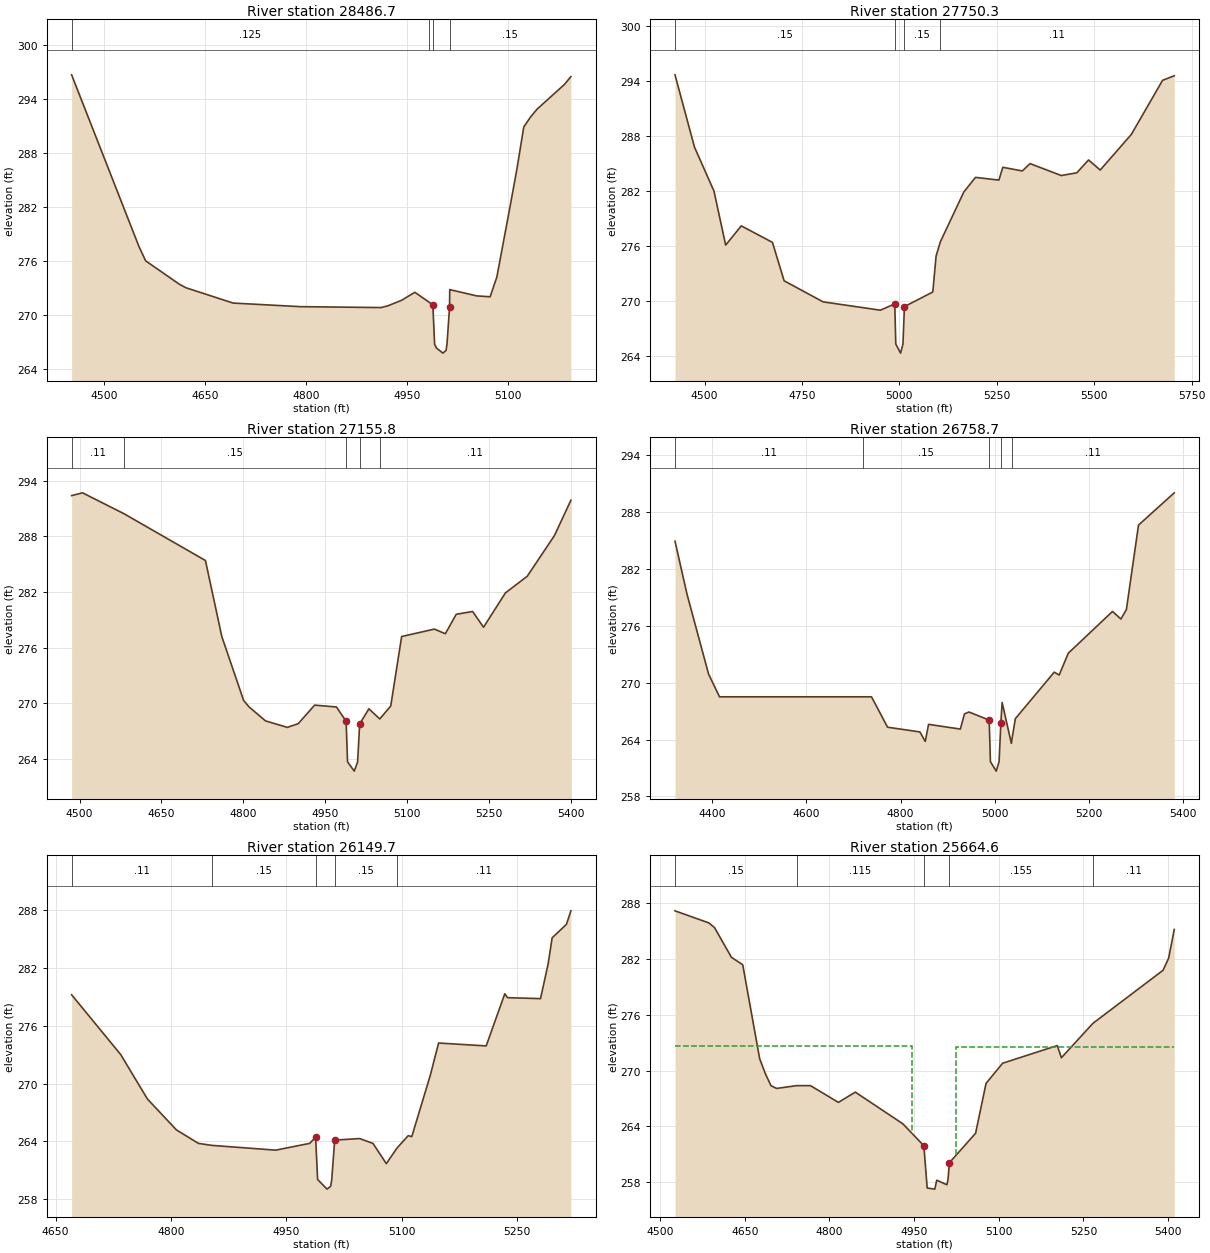
Type RM Length L Ch R = 1 ,28486.7 ,736.4,736.4,736.4
BEGIN DESCRIPTION:
Cross Section Richland Creek 41.0
END DESCRIPTION:
XS GIS Cut Line= 3
      2143864.82       815844.42      2143343.12       816024.08
        2143216.       816165.33
#Sta/Elev= 30
  4451.5   296.7  4551.5   277.6  4561.5     276  4611.5   273.4  4621.5     273
  4691.5   271.3  4791.5   270.9  4911.5   270.8  4921.5     271  4941.5   271.6
  4961.5   272.5  4982.4  271.41  4988.2  271.11  4990.8  266.73  4993.4  266.31
  5003.1  265.73  5007.8  266.03  5009.2  266.72    5013  270.81  5013.3   272.8
  5053.3   272.1  5073.3     272  5083.3   274.2  5103.3   282.2  5113.3   286.3
  5123.3   290.9  5133.3     292  5143.3   292.9  5183.3   295.6  5193.3   296.5
#Mann= 4 , 1 , 0
  4451.5    .125       0  4982.4     .15       0  4988.2    .038       0
    5013     .15       0
Bank Sta=4988.2,5013
XS Rating Curve= 0
Exp/Cntr=.3,.1

Type RM Length L Ch R = 1 ,27750.3 ,594.5,594.5,594.5
BEGIN DESCRIPTION:
Cross Section Richland Creek 40.0-CCX225
END DESCRIPTION:
XS GIS Cut Line= 5
      2143420.28       815365.56      2142942.08       815435.54
      2142869.17       815482.42      2142785.83       815539.71
      2142459.94       816055.36
#Sta/Elev= 30
  4424.3   294.7  4474.3   286.8  4524.3     282  4554.3   276.1  4594.3   278.2
  4674.3   276.4  4704.3   272.2  4804.3   269.9  4951.3  268.99  4988.2  269.68
  4990.8   265.3  5003.1   264.3  5009.2  265.29    5013  269.38  5085.8  270.98
  5094.2   274.9    5105  276.44  5165.4   281.9  5195.4   283.5  5255.4   283.2
  5265.4   284.6  5315.4   284.2  5335.4     285  5415.4   283.7  5455.4     284
  5485.4   285.4  5515.4   284.3  5595.4   288.2  5675.4   294.1  5705.4   294.6
#Mann= 4 , 1 , 0
  4424.3     .15       0  4988.2    .038       0    5013     .15       0
    5105     .11       0
Bank Sta=4988.2,5013
XS Rating Curve= 0
Exp/Cntr=.3,.1

Type RM Length L Ch R = 1 ,27155.8 ,397.12,397.12,397.12
BEGIN DESCRIPTION:
Cross Section Richland Creek 39.0
END DESCRIPTION:
XS GIS Cut Line= 4
      2142897.68        814984.4      2142718.12       815029.29
      2142405.62       815133.46      2142005.61       815133.46
#Sta/Elev= 30
  4485.4   292.4  4505.4   292.7  4581.2  290.45  4730.5   285.4  4760.5   277.2
  4800.5   270.3  4810.5   269.6  4840.5   268.1  4880.5   267.4  4900.5   267.8
  4930.5   269.8  4970.5   269.6  4988.2  268.06  4990.8  263.68  5003.1  262.68
  5009.2  263.67    5013  267.76  5029.9   269.4  5049.8  268.31  5069.9   269.7
  5089.9   277.2  5149.9     278  5169.9   277.5  5189.9   279.6  5219.9   279.9
  5239.9   278.2  5279.9   281.9  5319.9   283.7  5369.9   288.1  5399.9   291.9
#Mann= 5 , 1 , 0
  4485.4     .11       0  4581.2     .15       0  4988.2    .038       0
    5013     .15       0  5049.8     .11       0
Bank Sta=4988.2,5013
XS Rating Curve= 0
Exp/Cntr=.3,.1

Type RM Length L Ch R = 1 ,26758.7 ,609,609,609
BEGIN DESCRIPTION:
Cross Section Richland Creek 38.0
END DESCRIPTION:
XS GIS Cut Line= 3
      2143001.97       814672.37       2142327.5       814748.04
      2141994.95         814936.
#Sta/Elev= 30
  4320.7   284.9  4346.3   279.3    4392   270.9  4415.3   268.5  4719.7   268.5
  4738.2   268.5  4772.3   265.3    4841   264.8  4852.4   263.8  4859.4   265.6
  4926.9   265.1  4935.7   266.7  4945.1   266.9  4988.2  266.05  4990.8  261.67
  5003.1  260.67  5009.2  261.66    5013  265.75  5015.7   267.9  5035.3   263.6
    5037  264.17  5043.8   266.2  5126.4   271.1  5136.9   270.8  5156.3   273.1
  5250.2   277.5    5268   276.7  5279.7   277.7  5305.4   286.6  5381.4     290
#Mann= 5 , 1 , 0
  4320.7     .11       0  4719.7     .15       0  4988.2    .038       0
    5013     .15       0    5037     .11       0
Bank Sta=4988.2,5013
XS Rating Curve= 0
Exp/Cntr=.3,.1

Type RM Length L Ch R = 1 ,26149.7 ,485.1,485.1,485.1
BEGIN DESCRIPTION:
Cross Section Richland Creek 37.0
END DESCRIPTION:
XS GIS Cut Line= 3
      2142506.64       814106.28      2142186.87       814206.38
      2141904.16         814344.
#Sta/Elev= 30
  4670.8   279.2  4734.7     273  4769.4   268.4  4807.1   265.2  4835.8   263.8
  4853.6  263.59  4936.2   263.1  4980.5   263.8  4988.2  264.44  4990.8  260.06
  5003.1  259.06  5007.8  259.36  5009.2  260.05    5013  264.14  5045.5   264.3
  5062.8   263.8  5080.2   261.7  5094.1  263.32  5108.7   264.6  5113.3   264.5
  5137.2   270.8  5148.2   274.2  5210.1   273.9  5234.3   279.3  5237.9   278.9
  5280.8   278.8  5290.7   282.4  5295.9   285.1  5314.5   286.5  5320.3   287.9
#Mann= 5 , 1 , 0
  4670.8     .11       0  4853.6     .15       0  4988.2    .038       0
    5013     .15       0  5094.1     .11       0
Bank Sta=4988.2,5013
XS Rating Curve= 0
Exp/Cntr=.3,.1

Type RM Length L Ch R = 1 ,25664.6 ,51,51,51
BEGIN DESCRIPTION:
Upstream Section of Bridge/Culvert/Weir
END DESCRIPTION:
XS GIS Cut Line= 6
       2142512.9       813490.06      2142312.87       813572.94
      2142198.28       813656.27      2142114.95       813744.81
      2141995.16       813906.27      2141867.19       814064.83
#Sta/Elev= 30
  4526.3  287.19  4586.3  285.89  4596.3  285.39  4626.3  282.19  4646.3  281.39
  4676.3  271.29  4686.3  269.69  4696.3  268.39  4706.3  268.09  4741.8  268.39
  4766.3  268.39  4815.8  266.59  4845.8  267.69  4929.9  264.29  4967.2  261.93
  4973.1  257.38  4986.6  257.26  4990.1  258.22    5008  257.73    5010  258.27
  5012.5   260.1  5058.9  263.27  5077.4  268.63  5106.8   270.8  5203.6   272.7
  5210.9  271.39  5266.8  275.09  5390.9  280.79  5400.9  282.09  5410.9  285.19
#Mann= 5 , 1 , 0
  4526.3     .15       0  4741.8    .115       0  4967.2    .038       0
  5012.5    .155       0  5266.8     .11       0
#XS Ineff= 2 , 0
       0    4947   272.7    5025       0   272.5
Permanent Ineff=
       F       F
Bank Sta=4967.2,5012.5
XS Rating Curve= 0
Exp/Cntr=.5,.3