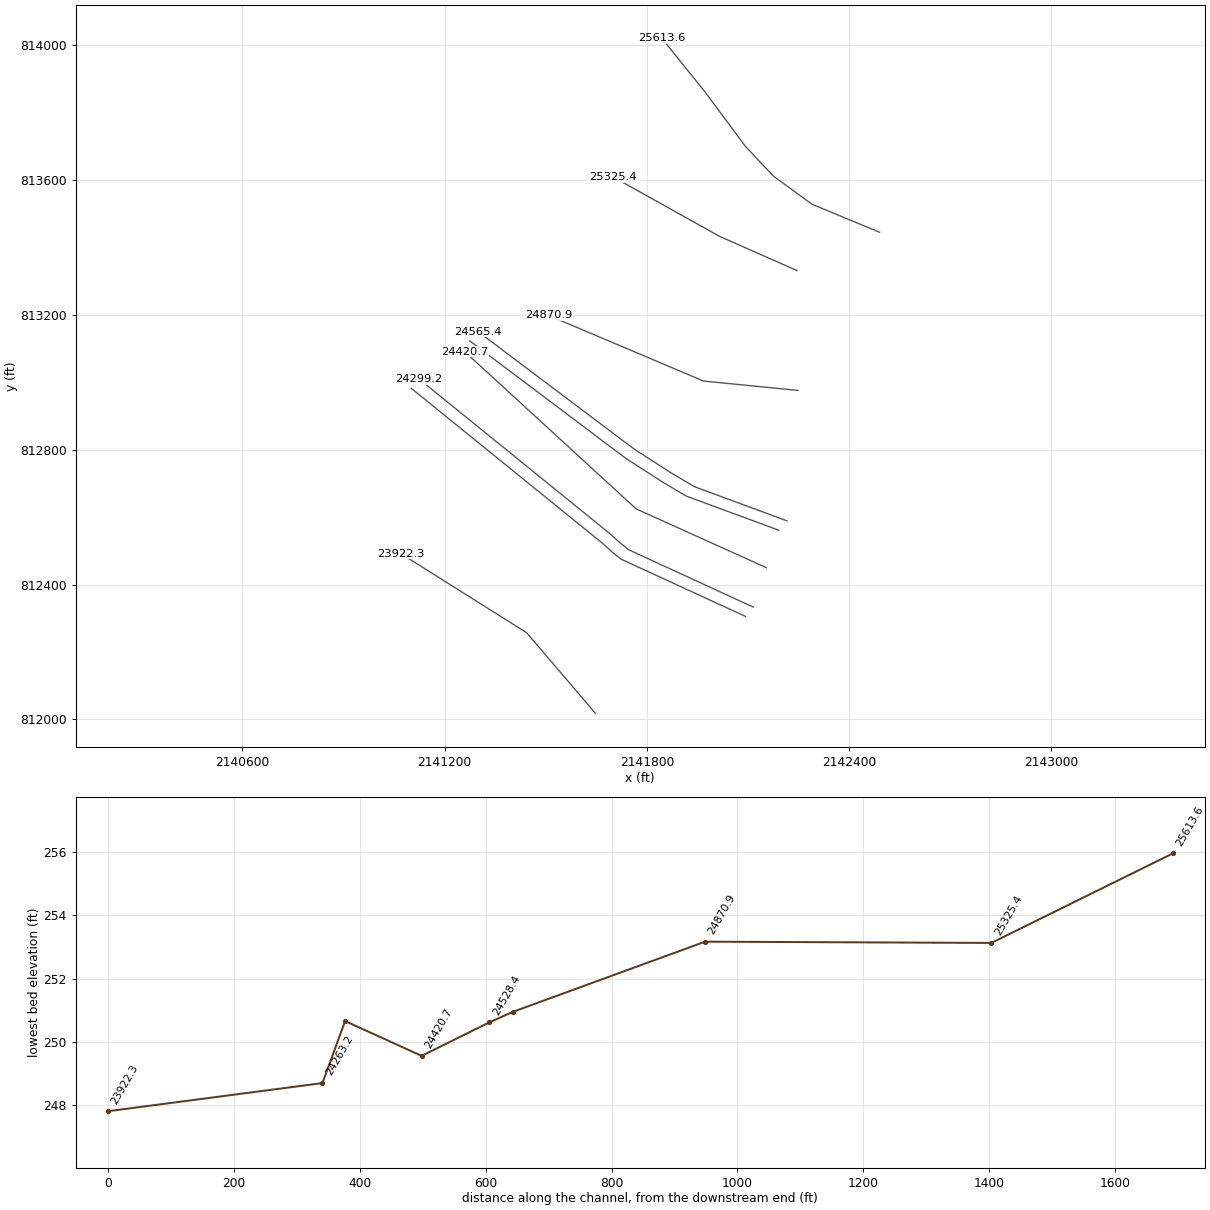
HEC-RAS study NE_Richland_Creek_FINAL.prj: Northeast Richland Creek

--- NE_Richland_Creek_FINAL.g01 (geometry) --- (continued)

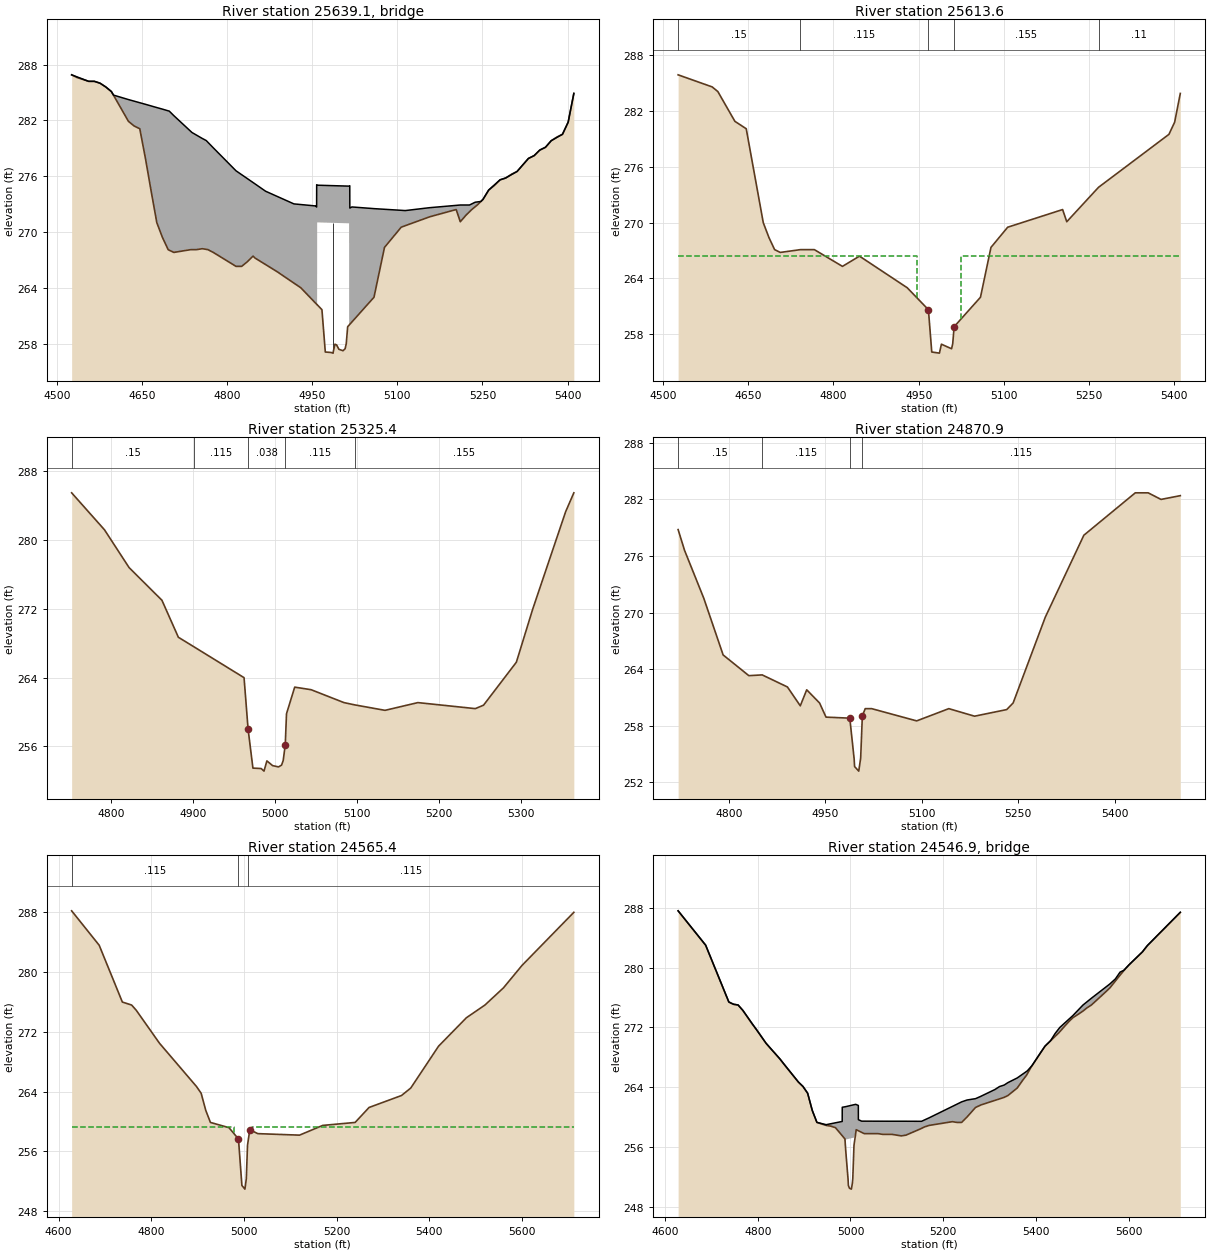
Type RM Length L Ch R = 3 ,25639.1 ,,,
BEGIN DESCRIPTION:
STADIUM DRIVE
Structure ID: WK_RLCR3
END DESCRIPTION:
Bridge Culvert--1,0,-1,-1, 0
Deck Dist Width WeirC Skew NumUp NumDn MinLoCord MaxHiCord MaxSubmerge Is_Ogee
10,31,2.6,0, 60, 60, , , .95, 0, 1,1,,
  4526.3  4556.3  4566.3  4576.3  4586.3  4596.3    4600  4626.3  4636.3  4646.3
  4656.3  4676.3  4686.3  4696.3  4698.2  4706.3  4738.2  4756.3  4763.4  4775.8
  4815.8  4825.8  4845.8    4868  4917.8  4929.9  4955.9 4957.79  4957.9 4958.71
  4958.8 5014.99  5015.1  5015.2  5016.2 5016.31    5020  5058.9  5077.4  5106.8
  5113.8  5156.6  5203.6  5210.9  5227.1  5237.1  5247.1  5250.9  5260.9  5280.9
  5290.9  5310.9  5330.9  5340.9  5350.9  5360.9  5370.9  5390.9  5400.9  5410.9
   286.9   286.2   286.2     286   285.6   285.1  284.72  284.24  284.07   283.9
  283.73  283.38  283.21  283.03     283  282.51   280.7  280.06  279.83  279.05
  276.58  276.16  275.32  274.38  273.02  272.95   272.8  272.68  275.08  275.03
  275.03  274.93  274.93  274.93  274.97  272.57  272.69  272.51  272.44  272.33
   272.3  272.61  272.86   272.9   272.9   273.2  273.28  273.51  274.51  275.61
  275.81  276.51  277.91  278.21  278.81  279.11  279.81  280.51  281.81   284.9
   286.9   286.2   286.2     286   285.6   285.1  284.71   281.9   281.4   281.1
   277.9     271   269.4   268.1  268.04   267.8   268.1   268.2  268.13   267.8
   266.3   266.3   267.4  266.49   264.5     264  262.35  262.24  262.23  262.18
  271.03  270.93  259.99  259.99  260.06  260.07  260.32  262.98  268.34  270.51
  270.67  271.62  272.41   271.1  272.17  272.71  273.27   273.5   274.5   275.6
   275.8   276.5   277.9   278.2   278.8   279.1   279.8   280.5   281.8   284.9
  4526.3  4556.3  4566.3  4576.3  4586.3  4596.3    4600  4626.3  4636.3  4646.3
  4656.3  4676.3  4686.3  4696.3  4698.2  4706.3  4738.2  4756.3  4763.4  4775.8
  4815.8  4825.8  4845.8    4868  4917.8  4929.9  4955.9 4957.79  4957.9 4958.71
  4958.8 5014.99  5015.1  5015.2  5016.2 5016.31    5020  5058.9  5077.4  5106.8
  5113.8  5156.6  5203.6  5210.9  5227.1  5237.1  5247.1  5250.9  5260.9  5280.9
  5290.9  5310.9  5330.9  5340.9  5350.9  5360.9  5370.9  5390.9  5400.9  5410.9
   286.9   286.2   286.2     286   285.6   285.1  284.72  284.24  284.07   283.9
  283.73  283.38  283.21  283.03     283  282.51   280.7  280.06  279.83  279.05
  276.58  276.16  275.32  274.38  273.02  272.95   272.8  272.68  275.08  275.03
  275.03  274.93  274.93  274.93  274.97  272.57  272.69  272.51  272.44  272.33
   272.3  272.61  272.86   272.9   272.9   273.2  273.28  273.51  274.51  275.61
  275.81  276.51  277.91  278.21  278.81  279.11  279.81  280.51  281.81   284.9
  286.01  285.31  285.31  285.11  284.71  284.21  283.82  281.01  280.51  280.21
  277.01  270.11  268.51  267.21  267.15  266.91  267.21  267.31  267.24  266.91
  265.41  265.41  266.51   265.6  263.61  263.11  261.46  261.35  261.34  261.29
  270.14  270.04   259.1   259.1  259.17  259.18  259.43  262.09  267.45  269.62
  269.78  270.73  271.52  270.21  271.28  271.82  272.38  272.61  273.61  274.71
  274.91  275.61  277.01  277.31  277.91  278.21  278.91  279.61  280.91  284.01
Pier Skew, UpSta & Num, DnSta & Num=  ,4986.6, 2 ,4986.6, 2 , 0 , 0 , 0 ,,
       1       1
  255.98  271.98
       1       1
  255.09  271.09
BR Coef= 1 , 1 , 0 ,1.25, 0 ,,,.8,0,2,0,
WSPro=,,,, 1 ,,,, 0 ,,,, 0 ,,,,-1 ,-1 ,-1 , 0 , 0 , 0 , 0 , 0
BR U #Sta/Elev= 119
  4526.3   286.9  4536.3   286.6  4546.3   286.4  4556.3   286.2  4566.3   286.2
  4576.3     286  4586.3   285.6  4596.3   285.1    4600  284.71  4626.3   281.9
  4636.3   281.4  4646.3   281.1  4656.3   277.9  4666.3   274.4  4676.3     271
  4686.3   269.4  4696.3   268.1  4698.2  268.04  4706.3   267.8  4708.2  267.82
  4718.2  267.92  4728.2  268.02  4736.3   268.1  4738.2   268.1  4741.8   268.1
  4742.8   268.1  4746.3   268.1  4756.3   268.2  4763.4  268.13  4766.3   268.1
  4775.8   267.8  4813.7  266.38  4815.8   266.3  4825.8   266.3  4835.8   266.8
  4845.8   267.4  4849.7  267.18    4868  266.49  4888.7  265.71  4917.8   264.5
  4929.9     264  4955.9  262.35 4957.79  262.24  4957.9  262.23 4958.01  262.22
  4958.6  262.18 4958.71  262.18  4958.8  262.17  4958.9  262.17  4967.2  261.64
  4973.1  257.09  4983.2  257.04  4986.6  256.97  4990.1  257.93    4993  257.85
  4997.1  257.38  5004.3  257.23    5008  257.44    5010  257.98  5012.5  259.81
  5014.9  259.97 5014.99  259.98  5015.1  259.99  5015.2  259.99 5016.09  260.06
  5016.2  260.06 5016.31  260.07    5020  260.32  5058.9  262.98  5066.2   265.1
  5077.4  268.34  5106.8  270.51  5113.8  270.67  5156.6  271.62  5162.3  271.72
  5203.6  272.41  5210.9   271.1  5211.3  271.13  5217.1  271.53  5220.9   271.8
  5227.1  272.17  5230.9   272.4  5237.1  272.71  5240.9   272.9  5247.1  273.27
  5250.9   273.5  5257.1  274.12  5260.9   274.5  5266.8   274.8  5267.1  274.81
  5270.9     275  5277.1  275.37  5280.9   275.6  5287.1  275.72  5290.9   275.8
  5297.1  276.05  5300.9   276.2  5307.1  276.39  5310.9   276.5  5317.1  276.93
  5320.9   277.2  5327.1  277.63  5330.9   277.9  5337.1  278.09  5340.9   278.2
  5347.1  278.57  5350.9   278.8  5357.1  278.99  5360.9   279.1  5367.1  279.53
  5370.9   279.8  5377.1  280.05  5380.9   280.2  5387.1  280.39  5390.9   280.5
  5397.1  281.31  5400.9   281.8  5407.1  283.72  5410.9   284.9
BR U #Mann= 5
  4526.3     .15  4741.8    .115  4967.2    .038  5012.5    .155  5266.8     .11
BR U Banks=4967.2,5012.5
BR D #Sta/Elev= 119
  4526.3  286.01  4536.3  285.71  4546.3  285.51  4556.3  285.31  4566.3  285.31
  4576.3  285.11  4586.3  284.71  4596.3  284.21    4600  283.82  4626.3  281.01
  4636.3  280.51  4646.3  280.21  4656.3  277.01  4666.3  273.51  4676.3  270.11
  4686.3  268.51  4696.3  267.21  4698.2  267.15  4706.3  266.91  4708.2  266.93
  4718.2  267.03  4728.2  267.13  4736.3  267.21  4738.2  267.21  4741.8  267.21
  4742.8  267.21  4746.3  267.21  4756.3  267.31  4763.4  267.24  4766.3  267.21
  4775.8  266.91  4813.7  265.49  4815.8  265.41  4825.8  265.41  4835.8  265.91
  4845.8  266.51  4849.7  266.29    4868   265.6  4888.7  264.82  4917.8  263.61
  4929.9  263.11  4955.9  261.46 4957.79  261.35  4957.9  261.34 4958.01  261.33
  4958.6  261.29 4958.71  261.29  4958.8  261.28  4958.9  261.28  4967.2  260.75
  4973.1   256.2  4983.2  256.15  4986.6  256.08  4990.1  257.04    4993  256.96
  4997.1  256.49  5004.3  256.34    5008  256.55    5010  257.09  5012.5  258.92
  5014.9  259.08 5014.99  259.09  5015.1   259.1  5015.2   259.1 5016.09  259.17
  5016.2  259.17 5016.31  259.18    5020  259.43  5058.9  262.09  5066.2  264.21
  5077.4  267.45  5106.8  269.62  5113.8  269.78  5156.6  270.73  5162.3  270.83
  5203.6  271.52  5210.9  270.21  5211.3  270.24  5217.1  270.64  5220.9  270.91
  5227.1  271.28  5230.9  271.51  5237.1  271.82  5240.9  272.01  5247.1  272.38
  5250.9  272.61  5257.1  273.23  5260.9  273.61  5266.8  273.91  5267.1  273.92
  5270.9  274.11  5277.1  274.48  5280.9  274.71  5287.1  274.83  5290.9  274.91
  5297.1  275.16  5300.9  275.31  5307.1   275.5  5310.9  275.61  5317.1  276.04
  5320.9  276.31  5327.1  276.74  5330.9  277.01  5337.1   277.2  5340.9  277.31
  5347.1  277.68  5350.9  277.91  5357.1   278.1  5360.9  278.21  5367.1  278.64
  5370.9  278.91  5377.1  279.16  5380.9  279.31  5387.1   279.5  5390.9  279.61
  5397.1  280.42  5400.9  280.91  5407.1  282.83  5410.9  284.01
BR D #Mann= 5
  4526.3     .15  4741.8    .115  4967.2    .038  5012.5    .155  5266.8     .11
BR D Banks=4967.2,5012.5
BC Design=,, 0 ,, 0 ,,,,,,

Type RM Length L Ch R = 1 ,25613.6 ,288.2,288.2,288.2
BEGIN DESCRIPTION:
Downstream Section of Bridge/Culvert/Weir
END DESCRIPTION:
XS GIS Cut Line= 6
      2142490.09       813444.45      2142290.05       813527.32
      2142175.46       813610.65      2142092.13       813699.19
      2141972.34       813860.65      2141844.38       814019.22
#Sta/Elev= 30
  4526.3  285.89  4586.3  284.59  4596.3  284.09  4626.3  280.89  4646.3  280.09
  4676.3  269.99  4686.3  268.39  4696.3  267.09  4706.3  266.79  4741.8  267.09
  4766.3  267.09  4815.8  265.29  4845.8  266.39  4929.9  262.99  4967.2  260.63
  4973.1  256.08  4986.6  255.96  4990.1  256.92    5008  256.43    5010  256.97
  5012.5   258.8  5058.9  261.97  5077.4  267.33  5106.8   269.5  5203.6   271.4
  5210.9  270.09  5266.8  273.79  5390.9  279.49  5400.9  280.79  5410.9  283.89
#Mann= 5 , 1 , 0
  4526.3     .15       0  4741.8    .115       0  4967.2    .038       0
  5012.5    .155       0  5266.8     .11       0
#XS Ineff= 2 , 0
       0    4947   266.4    5025       0   266.4
Permanent Ineff=
       F       F
Bank Sta=4967.2,5012.5
XS Rating Curve= 0
Exp/Cntr=.5,.3

Type RM Length L Ch R = 1 ,25325.4 ,454.5,454.5,454.5
BEGIN DESCRIPTION:
Cross Section Richland Creek 36.5
END DESCRIPTION:
XS GIS Cut Line= 3
       2142245.1       813330.89      2142014.81       813432.61
      2141700.45       813607.93
#Sta/Elev= 30
  4752.3   285.5  4792.3   281.2  4822.3   276.8  4862.3     273  4882.3   268.7
  4901.1   267.6  4962.3     264  4967.2  258.03  4973.1  253.48  4983.2  253.43
  4986.6  253.13  4990.1  254.32  4997.1  253.77  5004.3  253.62    5008  253.83
    5010  254.37  5012.5   256.2    5014   259.8    5024   262.9    5044   262.6
    5084   261.1  5097.4  260.83    5134   260.2    5174   261.1    5244   260.4
    5254   260.8    5294   265.8    5314     272    5354   283.3    5364   285.5
#Mann= 5 , 1 , 0
  4752.3     .15       0  4901.1    .115       0  4967.2    .038       0
  5012.5    .115       0  5097.4    .155       0
Bank Sta=4967.2,5012.5
XS Rating Curve= 0
Exp/Cntr=.3,.1

Type RM Length L Ch R = 1 ,24870.9 ,305.5,305.5,305.5
BEGIN DESCRIPTION:
Cross Section Richland Creek 36.0
END DESCRIPTION:
XS GIS Cut Line= 3
      2142247.73       812975.54      2141968.12       813003.25
      2141507.62       813198.08
#Sta/Elev= 30
  4721.1   278.8  4731.1   276.6  4761.1   271.5  4791.1   265.5  4831.1   263.3
  4851.9  263.38  4891.1   262.1  4911.1   260.1  4921.1   261.8  4941.1   260.4
  4951.1   258.9  4988.1  258.79  4994.9  254.44  4995.5  253.66    5002  253.17
    5005  254.55  5007.6  259.03  5012.1   259.8  5022.1   259.8  5092.1   258.5
  5142.1   259.8  5182.1     259  5232.1   259.7  5242.1   260.4  5292.1   269.5
  5352.1   278.2  5432.1   282.7  5452.1   282.7  5472.1     282  5502.1   282.4
#Mann= 4 , 1 , 0
  4721.1     .15       0  4851.9    .115       0  4988.1    .038       0
  5007.6    .115       0
Bank Sta=4988.1,5007.6
XS Rating Curve= 0
Exp/Cntr=.5,.3

Type RM Length L Ch R = 1 ,24565.4 ,37,37,37
BEGIN DESCRIPTION:
Upstream Section of Bridge/Culvert/Weir
END DESCRIPTION:
XS GIS Cut Line= 5
      2142215.76       812588.78       2141941.3       812689.96
      2141871.26       812731.47      2141762.31       812801.51
      2141298.83       813150.12
#Sta/Elev= 30
  4628.2  288.17  4687.6  283.57  4737.6  275.97  4757.6  275.57  4767.6  274.87
  4817.6  270.47  4897.6  264.67  4907.6  263.77  4917.6  261.47  4927.6  259.87
  4967.6  259.17  4988.1  257.66  4995.5  251.44    5002  250.95    5005  252.33
  5007.6  256.81  5012.5   258.9  5029.8  258.37  5119.8  258.17  5169.8  259.47
  5239.8  259.87  5269.8  261.87  5339.8  263.47  5359.8  264.47  5419.8  270.07
  5479.8  273.87  5519.8  275.57  5559.8  277.87  5599.8  280.87  5711.6  287.97
#Mann= 3 , 1 , 0
  4628.2    .115       0  4988.1    .038       0  5007.6    .115       0
#XS Ineff= 2 , 0
       0    4978   259.3    5017       0   259.3
Permanent Ineff=
       F       F
Bank Sta=4988.1,5012.5
XS Rating Curve= 0
Exp/Cntr=.5,.3

Type RM Length L Ch R = 3 ,24546.9 ,,,
BEGIN DESCRIPTION:
PASCHAL GOLF COURSE
Structure ID: WK_RLCR2B
END DESCRIPTION:
Bridge Culvert--1,0,-1,-1, 0
Deck Dist Width WeirC Skew NumUp NumDn MinLoCord MaxHiCord MaxSubmerge Is_Ogee
10,17,2.6,0, 60, 60, , , .95, 0, 1,1,,
  4628.2  4687.6  4737.6  4747.6  4757.6  4767.6  4817.6  4847.6  4887.6  4897.6
  4907.6  4917.6  4927.6  4947.6  4967.6 4982.19  4982.3  4988.1  4989.1 4989.61
  4989.7  5007.6  5011.3  5012.5    5017 5017.11  5024.1  5029.8  5089.8  5109.8
  5119.8  5153.3  5169.8  5219.8  5239.8  5251.6  5269.8  5279.8  5311.6  5321.6
  5331.6  5339.8  5359.8  5381.6  5391.6  5419.8  5431.6  5441.6  5451.6  5479.8
  5501.6  5519.8  5559.8  5571.6  5581.6  5589.8  5599.8  5629.8  5639.8  5711.6
   287.6  283.01  275.41  275.11  275.01  274.31  269.91  267.81  264.71  264.11
  263.21  260.91  259.31     259  259.25  259.43  261.33  261.39  261.41  261.41
  261.41  261.67  261.72  261.69  261.57  259.67  259.47  259.47  259.46  259.46
  259.46  259.45  259.92  261.44  262.05   262.3  262.48  262.75   263.7   264.1
   264.3  264.63  265.25   266.2   266.9  269.51  270.22   271.2     272  273.59
     275  275.91  277.83   278.5   279.4  279.65  280.31  282.11  282.91   287.4
   287.6     283   275.4   275.1     275   274.3   269.9   267.8   264.7   264.1
   263.2   260.9   259.3   258.9   258.6  257.53  257.52  257.09  256.09   255.7
  257.01  257.27  257.82  258.33  258.19  258.18  257.97   257.8   257.7   257.5
   257.6  258.51   258.9   259.4   259.3  260.03   261.3   261.6  262.24  262.44
  262.65   262.9   263.9   265.8  266.87   269.5  270.21  270.81  271.43   273.3
  274.19     275   277.3  278.24  278.99   279.6   280.3   282.1   282.9   287.4
  4628.2  4687.6  4737.6  4747.6  4757.6  4767.6  4817.6  4847.6  4887.6  4897.6
  4907.6  4917.6  4927.6  4947.6  4967.6 4982.19  4982.3  4988.1  4989.1 4989.61
  4989.7  5007.6  5011.3  5012.5    5017 5017.11  5024.1  5029.8  5089.8  5109.8
  5119.8  5153.3  5169.8  5219.8  5239.8  5251.6  5269.8  5279.8  5311.6  5321.6
  5331.6  5339.8  5359.8  5371.6  5379.8  5389.8  5419.8  5441.6  5449.8  5469.8
  5479.8  5489.8  5501.6  5519.8  5551.6  5559.8  5599.8  5629.8  5639.8  5711.6
  288.07  283.47  275.87  275.57  275.47  274.77  270.37  268.27  265.17  264.57
  263.67  261.37  259.77  259.37  259.25  259.43  261.33  261.39  261.41  261.41
  261.41  261.67  261.72  261.69  261.57  259.67  259.47  259.47  259.46  259.46
  259.46  259.45  259.92  261.44  262.05   262.3  262.48  262.75   263.7   264.1
   264.3  264.63  265.25   265.7  266.11  267.17  269.97  271.28  271.86  273.17
  273.77  274.27     275  275.91   277.5  277.83  280.77  282.57  283.37  287.87
  288.07  283.47  275.87  275.57  275.47  274.77  270.37  268.27  265.17  264.57
  263.67  261.37  259.77  259.37  259.07     258  257.99  257.56  256.56  256.17
  257.48  257.74  258.29   258.8  258.66  258.65  258.44  258.27  258.17  257.97
  258.07  258.98  259.37  259.87  259.77   260.5  261.77  262.07  262.71  262.91
  263.12  263.37  264.37  265.41  266.07  267.17  269.97  271.28  271.77  273.17
  273.77  274.17  274.66  275.47  277.28  277.77  280.77  282.57  283.37  287.87
BR Coef= 1 , 1 , 0 ,1.25, 0 ,,,.8,0,2,0,
WSPro=,,,, 1 ,,,, 0 ,,,, 0 ,,,,-1 ,-1 ,-1 , 0 , 0 , 0 , 0 , 0
BR U #Sta/Elev= 171
  4628.2   287.6  4638.2  286.83  4648.2  286.05  4658.2  285.28  4668.2   284.5
  4678.2  283.73  4687.6     283  4688.2  282.91  4698.2  281.39  4708.2  279.87
  4718.2  278.35  4728.2  276.83  4737.6   275.4  4738.2  275.38  4747.6   275.1
  4748.2  275.09  4757.6     275  4758.2  274.96  4767.6   274.3  4768.2  274.25
  4777.6   273.4  4778.2  273.35  4787.6   272.5  4788.2  272.45  4797.6   271.7
  4798.2  271.65  4808.2  270.75  4817.6   269.9  4818.2  269.86  4827.6   269.2
  4828.2  269.16  4838.2  268.46  4839.4  268.37  4847.6   267.8  4857.6     267
  4886.3   264.8  4887.6   264.7  4897.6   264.1  4907.6   263.2  4917.6   260.9
  4927.6   259.3  4934.3  259.17  4947.6   258.9  4957.6   258.8  4967.6   258.6
  4981.3  257.59 4982.19  257.53  4982.3  257.52 4982.41  257.51  4988.1  257.09
  4989.1  256.09  4989.5  255.78 4989.61   255.7  4989.7  255.63  4989.8  255.55
  4994.9  251.65  4995.5  250.87  4997.8   250.5    5002  250.38  5004.1  251.17
    5005  251.76  5007.6  256.24  5011.3  257.82 5011.39  257.86  5011.5   257.9
  5011.6  257.95  5012.5  258.33 5016.89  258.19    5017  258.19 5017.11  258.18
  5019.8   258.1  5024.1  257.97  5029.8   257.8  5039.8   257.8  5049.8   257.8
  5059.8   257.8  5069.8   257.7  5079.8   257.7  5089.8   257.7  5099.8   257.6
  5109.8   257.5  5119.8   257.6  5149.8   258.4  5153.3  258.51  5159.8   258.7
  5166.5  258.83  5169.8   258.9  5179.8     259  5189.8   259.1  5219.8   259.4
  5229.8   259.3  5239.8   259.3  5241.6  259.41  5249.8   259.9  5251.6  260.03
  5259.8   260.6  5261.6  260.73  5269.8   261.3  5271.6  261.35  5279.8   261.6
  5281.6  261.64  5291.6  261.84  5301.6  262.04  5311.6  262.24  5321.6  262.44
  5329.8   262.6  5331.6  262.65  5339.8   262.9  5341.6  262.99  5349.8   263.4
  5351.6  263.49  5359.8   263.9  5361.6  264.06  5369.8   264.8  5371.6  264.94
  5379.8   265.6  5381.6   265.8  5389.8   266.7  5391.6  266.87  5401.6  267.82
  5409.8   268.6  5411.6  268.76  5419.8   269.5  5421.6  269.61  5431.6  270.21
  5439.8   270.7  5441.6  270.81  5449.8   271.3  5451.6  271.43  5459.8     272
  5461.6  272.13  5469.8   272.7  5471.6  272.81  5479.8   273.3  5481.6  273.37
  5489.8   273.7  5491.6  273.77  5499.8   274.1  5501.6  274.19  5509.8   274.6
  5511.6  274.67  5519.8     275  5521.6   275.1  5531.6  275.67  5541.6  276.24
  5549.8   276.7  5551.6  276.81  5559.8   277.3  5561.6  277.44  5569.8   278.1
  5571.6  278.24  5581.6  278.99  5589.8   279.6  5591.6  279.73  5599.8   280.3
  5601.6  280.41  5609.8   280.9  5611.6  281.01  5619.8   281.5  5621.6  281.61
  5629.8   282.1  5631.6  282.24  5639.8   282.9  5641.6  283.01  5651.6  283.64
  5661.6  284.27  5671.6  284.89  5681.6  285.52  5691.6  286.15  5701.6  286.77
  5711.6   287.4
BR U #Mann= 3
  4628.2    .115  4988.1    .038  5007.6    .115
BR U Banks=4988.1,5012.5
BR D #Sta/Elev= 171
  4628.2  288.07  4638.2   287.3  4648.2  286.52  4658.2  285.75  4668.2  284.97
  4678.2   284.2  4687.6  283.47  4688.2  283.38  4698.2  281.86  4708.2  280.34
  4718.2  278.82  4728.2   277.3  4737.6  275.87  4738.2  275.85  4747.6  275.57
  4748.2  275.56  4757.6  275.47  4758.2  275.43  4767.6  274.77  4768.2  274.72
  4777.6  273.87  4778.2  273.82  4787.6  272.97  4788.2  272.92  4797.6  272.17
  4798.2  272.12  4808.2  271.22  4817.6  270.37  4818.2  270.33  4827.6  269.67
  4828.2  269.63  4838.2  268.93  4839.4  268.84  4847.6  268.27  4857.6  267.47
  4886.3  265.27  4887.6  265.17  4897.6  264.57  4907.6  263.67  4917.6  261.37
  4927.6  259.77  4934.3  259.64  4947.6  259.37  4957.6  259.27  4967.6  259.07
  4981.3  258.06 4982.19     258  4982.3  257.99 4982.41  257.98  4988.1  257.56
  4989.1  256.56  4989.5  256.25 4989.61  256.17  4989.7   256.1  4989.8  256.02
  4994.9  252.12  4995.5  251.34  4997.8  250.97    5002  250.85  5004.1  251.64
    5005  252.23  5007.6  256.71  5011.3  258.29 5011.39  258.33  5011.5  258.37
  5011.6  258.42  5012.5   258.8 5016.89  258.66    5017  258.66 5017.11  258.65
  5019.8  258.57  5024.1  258.44  5029.8  258.27  5039.8  258.27  5049.8  258.27
  5059.8  258.27  5069.8  258.17  5079.8  258.17  5089.8  258.17  5099.8  258.07
  5109.8  257.97  5119.8  258.07  5149.8  258.87  5153.3  258.98  5159.8  259.17
  5166.5   259.3  5169.8  259.37  5179.8  259.47  5189.8  259.57  5219.8  259.87
  5229.8  259.77  5239.8  259.77  5241.6  259.88  5249.8  260.37  5251.6   260.5
  5259.8  261.07  5261.6   261.2  5269.8  261.77  5271.6  261.82  5279.8  262.07
  5281.6  262.11  5291.6  262.31  5301.6  262.51  5311.6  262.71  5321.6  262.91
  5329.8  263.07  5331.6  263.12  5339.8  263.37  5341.6  263.46  5349.8  263.87
  5351.6  263.96  5359.8  264.37  5361.6  264.53  5369.8  265.27  5371.6  265.41
  5379.8  266.07  5381.6  266.27  5389.8  267.17  5391.6  267.34  5401.6  268.29
  5409.8  269.07  5411.6  269.23  5419.8  269.97  5421.6  270.08  5431.6  270.68
  5439.8  271.17  5441.6  271.28  5449.8  271.77  5451.6   271.9  5459.8  272.47
  5461.6   272.6  5469.8  273.17  5471.6  273.28  5479.8  273.77  5481.6  273.84
  5489.8  274.17  5491.6  274.24  5499.8  274.57  5501.6  274.66  5509.8  275.07
  5511.6  275.14  5519.8  275.47  5521.6  275.57  5531.6  276.14  5541.6  276.71
  5549.8  277.17  5551.6  277.28  5559.8  277.77  5561.6  277.91  5569.8  278.57
  5571.6  278.71  5581.6  279.46  5589.8  280.07  5591.6   280.2  5599.8  280.77
  5601.6  280.88  5609.8  281.37  5611.6  281.48  5619.8  281.97  5621.6  282.08
  5629.8  282.57  5631.6  282.71  5639.8  283.37  5641.6  283.48  5651.6  284.11
  5661.6  284.74  5671.6  285.36  5681.6  285.99  5691.6  286.62  5701.6  287.24
  5711.6  287.87
BR D #Mann= 3
  4628.2    .115  4988.1    .038  5007.6    .115
BR D Banks=4988.1,5012.5
BC Design=,, 0 ,, 0 ,,,,,,

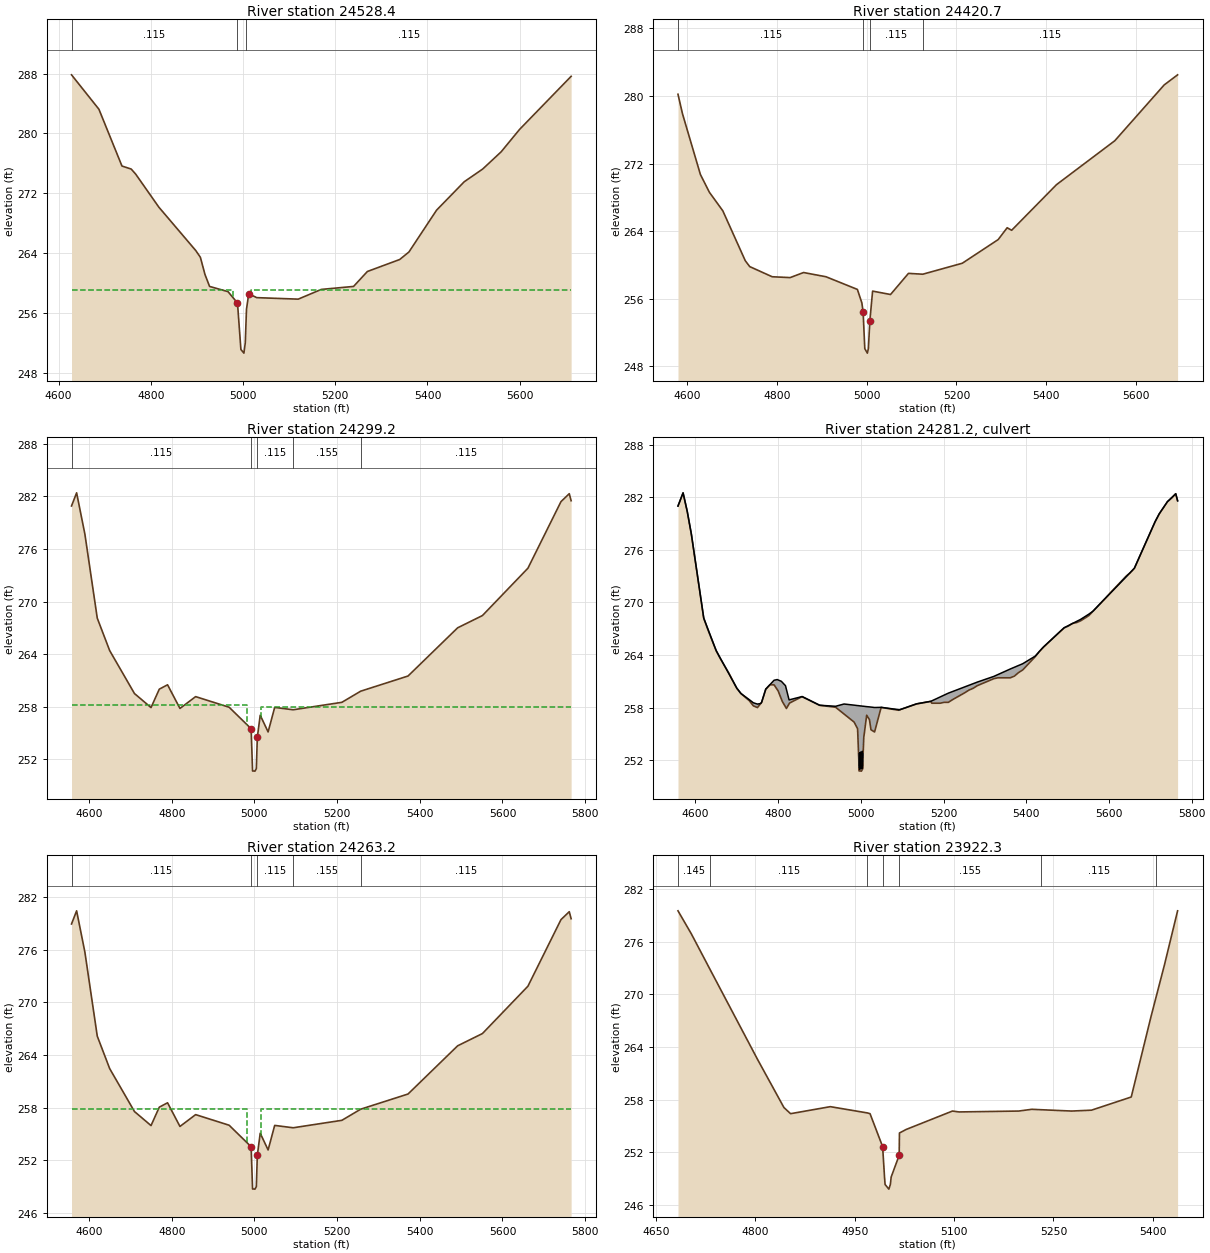
Type RM Length L Ch R = 1 ,24528.4 ,107.7,107.7,107.7
BEGIN DESCRIPTION:
Downstream Section of Bridge/Culvert/Weir
END DESCRIPTION:
XS GIS Cut Line= 5
      2142191.24       812561.06      2141916.78       812662.24
      2141846.74       812703.75      2141737.79       812773.79
      2141274.32        813122.4
#Sta/Elev= 30
  4628.2  287.84  4687.6  283.24  4737.6  275.64  4757.6  275.24  4767.6  274.54
  4817.6  270.14  4897.6  264.34  4907.6  263.44  4917.6  261.14  4927.6  259.54
  4967.6  258.84  4988.1  257.33  4995.5  251.11    5002  250.62    5005     252
  5007.6  256.48  5012.5  258.57  5029.8  258.04  5119.8  257.84  5169.8  259.14
  5239.8  259.54  5269.8  261.54  5339.8  263.14  5359.8  264.14  5419.8  269.74
  5479.8  273.54  5519.8  275.24  5559.8  277.54  5599.8  280.54  5711.6  287.64
#Mann= 3 , 1 , 0
  4628.2    .115       0  4988.1    .038       0  5007.6    .115       0
#XS Ineff= 2 , 0
       0    4978     259    5017       0     259
Permanent Ineff=
       F       F
Bank Sta=4988.1,5012.5
XS Rating Curve= 0
Exp/Cntr=.5,.3

Type RM Length L Ch R = 1 ,24420.7 ,121.5,121.5,121.5
BEGIN DESCRIPTION:
Cross Section Richland Creek 35.0
END DESCRIPTION:
XS GIS Cut Line= 3
      2142154.58       812449.95      2141768.21       812624.22
      2141259.54        813090.5
#Sta/Elev= 30
  4579.3   280.2  4589.3   277.9  4629.3   270.7  4649.3   268.6  4679.3   266.4
  4729.3   260.5  4739.3   259.8  4789.3   258.6  4829.3   258.5  4859.3   259.1
  4909.3   258.6  4979.3   257.1  4989.3   255.5  4992.1   254.4  4995.8  250.09
  5001.5  249.56  5003.8   250.1  5007.1  253.41  5013.2   256.9  5053.2   256.5
  5093.2     259    5125   258.9  5213.2   260.2  5293.2     263  5313.2   264.4
  5323.2   264.1  5423.2   269.5  5553.2   274.7  5663.2   281.3  5693.2   282.5
#Mann= 4 , 1 , 0
  4579.3    .115       0  4992.1    .038       0  5007.1    .115       0
    5125    .115       0
Bank Sta=4992.1,5007.1
XS Rating Curve= 0
Exp/Cntr=.5,.3

Type RM Length L Ch R = 1 ,24299.2 ,36,36,36
BEGIN DESCRIPTION:
Upstream Section of Bridge/Culvert/Weir
END DESCRIPTION:
XS GIS Cut Line= 5
      2142115.38       812333.24        2141746.       812503.15
      2141720.06       812523.91      2141691.53       812549.85
      2141124.16       813009.24
#Sta/Elev= 30
  4557.7  280.91    4570  282.41    4590  277.71    4620  268.11    4650  264.41
    4710  259.51    4750  257.91    4770  260.01    4790  260.51    4820  257.81
  4857.9  259.16  4938.9  257.95  4992.1   255.5  4995.6  250.68  5001.5  250.66
  5004.7  250.95  5007.1  254.51  5014.1  257.04  5033.2  255.13  5049.1  257.93
  5093.9  257.66  5211.6  258.51  5257.1  259.78  5371.6  261.51  5491.6  267.01
  5551.6  268.41  5661.6  273.81  5741.6  281.41  5761.6  282.31  5766.1  281.51
#Mann= 5 , 1 , 0
  4557.7    .115       0  4992.1    .038       0  5007.1    .115       0
  5093.9    .155       0  5257.1    .115       0
#XS Ineff= 2 , 0
       0    4982   258.2    5017       0     258
Permanent Ineff=
       F       F
Bank Sta=4992.1,5007.1
XS Rating Curve= 0
Exp/Cntr=.5,.3

Type RM Length L Ch R = 2 ,24281.2 ,,,
BEGIN DESCRIPTION:
PASCHAL GOLF COURSE
Structure ID: WK_RLCR2A
END DESCRIPTION:
Bridge Culvert--1,0,-1,-1, 0
Deck Dist Width WeirC Skew NumUp NumDn MinLoCord MaxHiCord MaxSubmerge Is_Ogee
10,16,3,0, 60, 60, , , .95, 0, 1,1,,
  4557.7    4570    4580    4590    4620    4650    4700    4710    4730    4740
    4750  4757.7    4760    4770    4780    4790  4797.7  4807.7  4817.7    4820
  4826.4  4857.9  4900.3  4938.9  4959.3  4983.6  4992.1    4995  4995.6  5001.5
  5004.7    5005  5007.1  5014.1  5020.8  5024.5  5033.2  5049.1  5093.9  5134.8
    5169  5171.6  5211.6  5281.6  5321.6  5361.6  5391.6  5421.6  5441.6  5491.6
  5531.6  5551.6  5561.6  5651.6  5661.6  5711.6  5721.6  5741.6  5761.6  5766.1
     281  282.51  280.41  277.81  268.21  264.51  260.21  259.61  258.91  258.55
   258.4  258.47  258.61  260.11  260.61  261.12   261.2     261   260.5  260.07
  258.88  259.26  258.27  258.15  258.41  258.28  258.23  258.22  258.21  258.18
  258.16  258.16  258.15  258.11  258.08  258.06  258.01  258.03  257.75  258.43
  258.72  258.77  259.65  260.91  261.56  262.41  263.01  263.87  264.91  267.11
  268.07  268.67  269.01  273.41  273.91  279.21  280.11  281.51  282.41   281.6
     281   282.5   280.4   277.8   268.2   264.5   260.2   259.6   258.8   258.2
     258  258.46   258.6   260.1   260.6   260.6  260.06  258.98  258.08   257.9
  258.42  259.25  258.26  258.04  257.27  256.35  255.59  252.08  250.77  250.75
  251.04  252.13   254.6  257.13  256.62  255.47  255.22  258.02  257.75  258.42
   258.7   258.5   258.6   260.5   261.3   261.4   262.3   263.8   264.9   267.1
   267.9   268.5     269   273.4   273.9   279.2   280.1   281.5   282.4   281.6
  4557.7    4570    4580    4590    4620    4650    4700    4710    4730    4740
    4750  4757.7    4760    4770    4780    4790  4797.7  4807.7  4817.7    4820
  4826.4  4857.9  4900.3  4938.9  4959.3  4983.6  4992.1    4995  4995.6  5001.5
  5004.7    5005  5007.1  5014.1  5020.8  5024.5  5033.2  5049.1  5093.9  5134.8
    5169  5171.6  5211.6  5281.6  5321.6  5361.6  5391.6  5421.6  5441.6  5491.6
  5531.6  5551.6  5561.6  5651.6  5661.6  5711.6  5721.6  5741.6  5761.6  5766.1
     281  282.51  280.41  277.81  268.21  264.51  260.21  259.61  258.91  258.55
   258.4  258.47  258.61  260.11  260.61  261.12   261.2     261   260.5  260.07
  258.88  259.26  258.27  258.15  258.41  258.28  258.23  258.22  258.21  258.18
  258.16  258.16  258.15  258.11  258.08  258.06  258.01  258.03  257.75  258.43
  258.72  258.77  259.65  260.91  261.56  262.41  263.01  263.87  264.91  267.11
  268.07  268.67  269.01  273.41  273.91  279.21  280.11  281.51  282.41   281.6
  279.97  281.47  279.37  276.77  267.17  263.47  259.17  258.57  257.77  257.17
  256.97  257.43  257.57  259.07  259.57  259.57  259.03  257.95  257.05  256.87
  257.39  258.22  257.23  257.01  256.24  255.32  254.56  251.05  249.74  249.72
  250.01   251.1  253.57   256.1  255.59  254.44  254.19  256.99  256.72  257.39
  257.67  257.47  257.57  259.47  260.27  260.37  261.27  262.77  263.87  266.07
  266.87  267.47  267.97  272.37  272.87  278.17  279.07  280.47  281.37  280.57
BR Coef= 1 , 0 , 0 ,1.25, 0 ,,,.8,-1,2,0,
WSPro=,,,, 1 ,,,, 0 ,,,, 0 ,,,,-1 ,-1 ,-1 , 0 , 0 , 0 , 0 , 0
Culvert=1,2,,16,.024,.5,1,2,1,250.9,4996.9,250.27,4996.9,Culvert #1  , 0 ,10
Culvert Bottom n=.024
Culvert=1,2,,16,.024,.5,1,2,1,250.97,5000.1,249.85,5000.1,Culvert #2  , 0 ,10
Culvert Bottom n=.024
Culvert=1,2,,16,.024,.5,1,2,1,251.05,5003.5,250.16,5003.5,Culvert #3  , 0 ,10
Culvert Bottom n=.024
BR U #Sta/Elev= 175
  4557.7     281  4567.7  282.22    4570   282.5  4577.7  280.88    4580   280.4
  4587.7   278.4    4590   277.8    4600   274.6    4620   268.2  4627.7   267.2
    4630   266.9  4637.7  265.98    4640   265.7  4647.7  264.78    4650   264.5
  4657.7  263.81    4660   263.6    4680     262  4687.7  261.31    4690   261.1
  4697.7  260.41    4700   260.2  4707.7  259.74    4710   259.6  4717.7  259.29
    4720   259.2  4727.7  258.89    4730   258.8  4737.7  258.34    4740   258.2
  4747.7  258.05    4750     258  4757.7  258.46    4760   258.6  4767.7  259.76
    4770   260.1  4777.7  260.49    4780   260.6  4787.7   260.6    4790   260.6
  4797.7  260.06    4800   259.9  4807.7  258.98    4810   258.7  4817.7  258.08
    4820   257.9  4826.4  258.42  4827.6  258.52  4857.9  259.25  4871.6  258.93
  4900.3  258.26  4915.8  258.17  4938.9  258.04  4959.3  257.27  4983.6  256.35
  4992.1  255.59    4995  252.08  4995.6  250.77    4999  250.77  5001.5  250.75
  5004.7  251.04    5005  252.13  5007.1   254.6  5014.1  257.13  5020.8  256.62
  5024.5  255.47  5033.2  255.22  5047.8  257.79  5049.1  258.02    5091   257.7
  5093.9  257.75  5096.3  257.79  5134.8  258.42  5143.5  258.49    5169   258.7
  5171.6   258.5  5181.6   258.5  5191.6   258.5  5201.6   258.6  5211.6   258.6
  5221.6   258.9  5246.1  259.55  5251.6   259.7  5256.1  259.84  5257.1  259.87
  5261.6     260  5266.1  260.09  5271.6   260.2  5276.1  260.34  5281.6   260.5
  5286.1  260.59  5291.6   260.7  5296.1  260.79  5306.1  260.99  5316.1  261.19
  5321.6   261.3  5326.1  261.35  5331.6   261.4  5336.1   261.4  5341.6   261.4
  5346.1   261.4  5356.1   261.4  5361.6   261.4  5366.1  261.49  5371.6   261.6
  5376.1  261.78  5381.6     262  5386.1  262.14  5391.6   262.3  5396.1  262.53
  5401.6   262.8  5406.1  263.03  5411.6   263.3  5416.1  263.53  5421.6   263.8
  5426.1  264.07  5431.6   264.4  5436.1  264.63  5441.6   264.9  5446.1   265.1
  5456.1  265.54  5466.1  265.98  5476.1  266.42  5486.1  266.86  5491.6   267.1
  5496.1  267.19  5501.6   267.3  5506.1  267.44  5511.6   267.6  5516.1  267.65
  5521.6   267.7  5526.1  267.79  5531.6   267.9  5536.1  268.03  5541.6   268.2
  5546.1  268.34  5551.6   268.5  5556.1  268.73  5561.6     269  5566.1  269.23
  5571.6   269.5  5576.1  269.73  5581.6     270  5586.1  270.23  5591.6   270.5
  5596.1  270.73  5601.6     271  5606.1  271.23  5611.6   271.5  5616.1  271.73
  5621.6     272  5626.1  272.23  5631.6   272.5  5636.1  272.73  5641.6     273
  5646.1  273.18  5651.6   273.4  5656.1  273.63  5661.6   273.9  5666.1  274.38
  5676.1  275.44  5686.1   276.5  5696.1  277.56  5706.1  278.62  5711.6   279.2
  5716.1  279.61  5721.6   280.1  5726.1  280.42  5731.6   280.8  5736.1  281.12
  5741.6   281.5  5751.6   281.9  5756.1  282.13  5761.6   282.4  5766.1   281.6
BR U #Mann= 5
  4557.7    .115  4992.1    .038  5007.1    .115  5093.9    .155  5257.1    .115
BR U Banks=4992.1,5007.1
BR D #Sta/Elev= 175
  4557.7  279.97  4567.7  281.19    4570  281.47  4577.7  279.85    4580  279.37
  4587.7  277.37    4590  276.77    4600  273.57    4620  267.17  4627.7  266.17
    4630  265.87  4637.7  264.95    4640  264.67  4647.7  263.75    4650  263.47
  4657.7  262.78    4660  262.57    4680  260.97  4687.7  260.28    4690  260.07
  4697.7  259.38    4700  259.17  4707.7  258.71    4710  258.57  4717.7  258.26
    4720  258.17  4727.7  257.86    4730  257.77  4737.7  257.31    4740  257.17
  4747.7  257.02    4750  256.97  4757.7  257.43    4760  257.57  4767.7  258.73
    4770  259.07  4777.7  259.46    4780  259.57  4787.7  259.57    4790  259.57
  4797.7  259.03    4800  258.87  4807.7  257.95    4810  257.67  4817.7  257.05
    4820  256.87  4826.4  257.39  4827.6  257.49  4857.9  258.22  4871.6   257.9
  4900.3  257.23  4915.8  257.14  4938.9  257.01  4959.3  256.24  4983.6  255.32
  4992.1  254.56    4995  251.05  4995.6  249.74    4999  249.74  5001.5  249.72
  5004.7  250.01    5005   251.1  5007.1  253.57  5014.1   256.1  5020.8  255.59
  5024.5  254.44  5033.2  254.19  5047.8  256.76  5049.1  256.99    5091  256.67
  5093.9  256.72  5096.3  256.76  5134.8  257.39  5143.5  257.46    5169  257.67
  5171.6  257.47  5181.6  257.47  5191.6  257.47  5201.6  257.57  5211.6  257.57
  5221.6  257.87  5246.1  258.52  5251.6  258.67  5256.1  258.81  5257.1  258.84
  5261.6  258.97  5266.1  259.06  5271.6  259.17  5276.1  259.31  5281.6  259.47
  5286.1  259.56  5291.6  259.67  5296.1  259.76  5306.1  259.96  5316.1  260.16
  5321.6  260.27  5326.1  260.32  5331.6  260.37  5336.1  260.37  5341.6  260.37
  5346.1  260.37  5356.1  260.37  5361.6  260.37  5366.1  260.46  5371.6  260.57
  5376.1  260.75  5381.6  260.97  5386.1  261.11  5391.6  261.27  5396.1   261.5
  5401.6  261.77  5406.1     262  5411.6  262.27  5416.1   262.5  5421.6  262.77
  5426.1  263.04  5431.6  263.37  5436.1   263.6  5441.6  263.87  5446.1  264.07
  5456.1  264.51  5466.1  264.95  5476.1  265.39  5486.1  265.83  5491.6  266.07
  5496.1  266.16  5501.6  266.27  5506.1  266.41  5511.6  266.57  5516.1  266.62
  5521.6  266.67  5526.1  266.76  5531.6  266.87  5536.1     267  5541.6  267.17
  5546.1  267.31  5551.6  267.47  5556.1   267.7  5561.6  267.97  5566.1   268.2
  5571.6  268.47  5576.1   268.7  5581.6  268.97  5586.1   269.2  5591.6  269.47
  5596.1   269.7  5601.6  269.97  5606.1   270.2  5611.6  270.47  5616.1   270.7
  5621.6  270.97  5626.1   271.2  5631.6  271.47  5636.1   271.7  5641.6  271.97
  5646.1  272.15  5651.6  272.37  5656.1   272.6  5661.6  272.87  5666.1  273.35
  5676.1  274.41  5686.1  275.47  5696.1  276.53  5706.1  277.59  5711.6  278.17
  5716.1  278.58  5721.6  279.07  5726.1  279.39  5731.6  279.77  5736.1  280.09
  5741.6  280.47  5751.6  280.87  5756.1   281.1  5761.6  281.37  5766.1  280.57
BR D #Mann= 5
  4557.7    .115  4992.1    .038  5007.1    .115  5093.9    .155  5257.1    .115
BR D Banks=4992.1,5007.1
BC Design=,, 0 ,, 0 ,,,,,,

Type RM Length L Ch R = 1 ,24263.2 ,340.9,340.9,340.9
BEGIN DESCRIPTION:
Downstream Section of Bridge/Culvert/Weir
END DESCRIPTION:
XS GIS Cut Line= 5
      2142092.34       812305.58      2141722.96       812475.49
      2141697.02       812496.25      2141668.49       812522.19
      2141101.12       812981.58
#Sta/Elev= 30
  4557.7  278.95    4570  280.45    4590  275.75    4620  266.15    4650  262.45
    4710  257.55    4750  255.95    4770  258.05    4790  258.55    4820  255.85
  4857.9   257.2  4938.9  255.99  4992.1  253.54  4995.6  248.72  5001.5   248.7
  5004.7  248.99  5007.1  252.55  5014.1  255.08  5033.2  253.17  5049.1  255.97
  5093.9   255.7  5211.6  256.55  5257.1  257.82  5371.6  259.55  5491.6  265.05
  5551.6  266.45  5661.6  271.85  5741.6  279.45  5761.6  280.35  5766.1  279.55
#Mann= 5 , 1 , 0
  4557.7    .115       0  4992.1    .038       0  5007.1    .115       0
  5093.9    .155       0  5257.1    .115       0
#XS Ineff= 2 , 0
       0    4982   257.8    5017       0   257.8
Permanent Ineff=
       F       F
Bank Sta=4992.1,5007.1
XS Rating Curve= 0
Exp/Cntr=.5,.3

Type RM Length L Ch R = 1 ,23922.3 ,506.4,506.4,506.4
BEGIN DESCRIPTION:
Cross Section Richland Creek 34.5
END DESCRIPTION:
XS GIS Cut Line= 3
      2141647.43       812018.08      2141443.29       812257.15
      2141070.74       812491.32
#Sta/Elev= 30
  4683.1   279.5  4703.1   276.9  4731.7   272.8  4803.1   262.6  4843.1   257.1
  4853.1   256.4  4913.1   257.2  4968.8  256.49  4973.1   256.4  4992.1  252.65
    4995  249.14  4995.8  248.34  5001.5  247.81  5003.8  248.35    5005  249.19
  5017.1  251.66  5017.5   254.2  5027.5   254.6  5097.5   256.7  5107.5   256.6
  5197.5   256.7  5217.5   256.9  5231.8  256.85  5277.5   256.7  5307.5   256.8
  5367.5   258.3  5397.5   267.5  5405.4  269.79  5417.5   273.3  5437.5   279.5
#Mann= 7 , 1 , 0
  4683.1    .145       0  4731.7    .115       0  4968.8    .155       0
  4992.1    .038       0  5017.1    .155       0  5231.8    .115       0
  5405.4     .13       0
Bank Sta=4992.1,5017.1
XS Rating Curve= 0
Exp/Cntr=.3,.1