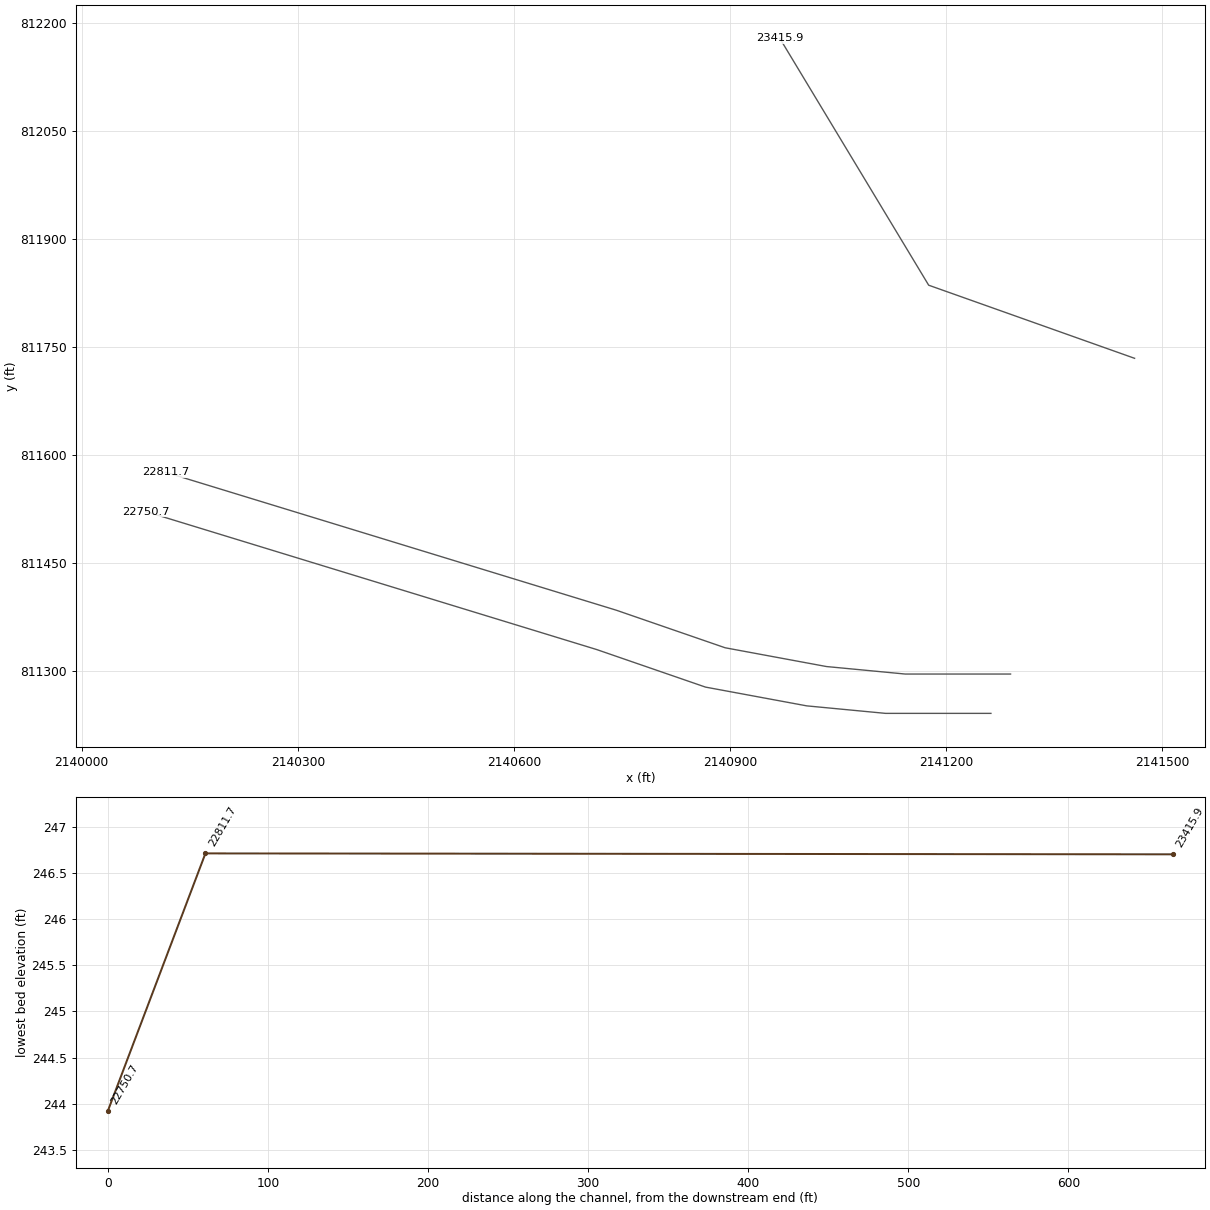
HEC-RAS study NE_Richland_Creek_FINAL.prj: Northeast Richland Creek

--- NE_Richland_Creek_FINAL.g01 (geometry) --- (continued)

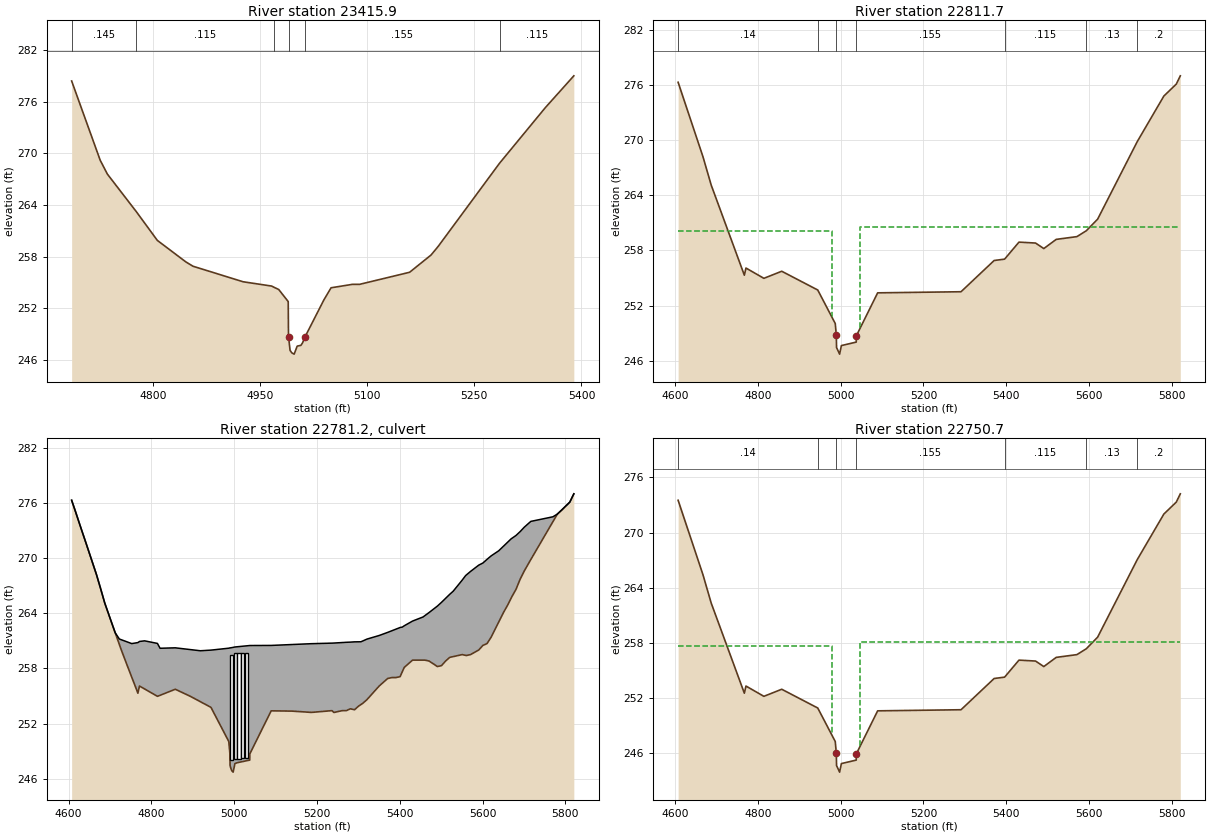
Type RM Length L Ch R = 1 ,23415.9 ,604.2,604.2,604.2
BEGIN DESCRIPTION:
Cross Section Richland Creek 34.0
END DESCRIPTION:
XS GIS Cut Line= 3
      2141461.61       811734.17      2141175.77        811835.6
      2140969.11       812178.07
#Sta/Elev= 30
    4686   278.4    4726   269.2    4736   267.6  4776.7  263.22    4806   259.9
    4846   257.4    4856   256.9    4926   255.1    4966   254.6  4969.9  254.44
    4976   254.2  4989.3   252.8  4989.7  248.74  4991.9  247.14  4994.3  246.85
  4997.6   246.7  5001.9  247.63  5007.1  247.72  5009.4  248.01  5012.7  248.68
  5039.3     253  5049.3   254.4  5079.3   254.8  5089.3   254.8  5159.3   256.2
  5189.3   258.2  5199.3   259.2  5285.2  268.85  5349.3   275.3  5389.3     279
#Mann= 6 , 1 , 0
    4686    .145       0  4776.7    .115       0  4969.9    .155       0
  4989.7    .038       0  5012.7    .155       0  5285.2    .115       0
Bank Sta=4989.7,5012.7
XS Rating Curve= 0
Exp/Cntr=.5,.3

Type RM Length L Ch R = 1 ,22811.7 ,61,61,61
BEGIN DESCRIPTION:
Upstream Section of Bridge/Culvert/Weir
END DESCRIPTION:
XS GIS Cut Line= 6
      2141289.46       811296.16      2141143.22       811296.16
      2141033.85       811306.57      2140893.22       811332.61
      2140742.18        811384.7      2140116.59       811576.03
#Sta/Elev= 30
  4607.5   276.3  4667.5   268.2  4687.5   265.1  4767.5   255.3  4771.4  256.08
  4814.7  254.96  4857.8  255.73  4944.8  253.69  4987.1  250.04  4989.7  248.75
  4990.2  247.43  4997.6  246.71  5001.9  247.64  5037.8  248.02  5037.9  248.69
  5089.5  253.38  5290.9   253.5  5370.9   256.9  5396.2  257.05  5430.9   258.9
  5470.9   258.8  5490.9   258.2  5520.9   259.2  5570.9   259.5  5593.6  260.14
  5620.9   261.4  5716.6  269.84  5780.9   274.8  5810.9   276.1  5820.6     277
#Mann= 7 , 1 , 0
  4607.5     .14       0  4944.8    .115       0  4989.7     .04       0
  5037.9    .155       0  5396.2    .115       0  5593.6     .13       0
  5716.6      .2       0
#XS Ineff= 2 , 0
       0    4979   260.1    5048       0   260.5
Permanent Ineff=
       F       F
Bank Sta=4989.7,5037.9
XS Rating Curve= 0
Exp/Cntr=.5,.3

Type RM Length L Ch R = 2 ,22781.2 ,,,
BEGIN DESCRIPTION:
DURHAM ROAD
Structure ID: WK_RLCR2
END DESCRIPTION:
Bridge Culvert--1,0,-1,-1, 0
Deck Dist Width WeirC Skew NumUp NumDn MinLoCord MaxHiCord MaxSubmerge Is_Ogee
10,41,3,0, 60, 60, , , .95, 0, 1,1,,
  4607.5  4667.5  4687.5  4712.7  4722.7  4752.7  4767.5  4771.4  4783.7  4814.7
  4821.1  4857.8  4918.4    4944  4987.1  4989.7  4990.2  4994.3  4997.6  5001.9
  5037.8  5037.9  5089.5  5186.8  5236.5  5240.9  5270.9  5280.9  5290.9  5306.4
  5320.9  5350.9  5370.9  5400.9  5406.4  5410.9  5430.9  5456.4  5470.9  5490.9
  5500.9  5520.9  5529.1  5550.9  5559.1  5570.9  5590.9  5600.9  5610.9  5620.9
  5639.1  5669.1  5680.9  5690.9  5700.9  5716.6    5770  5780.9  5810.9  5820.6
   276.3  268.21  265.11  261.88   261.2   260.7  260.81  260.93     261  260.72
  260.19  260.24  259.92  259.99   260.2  260.23  260.23  260.26  260.29  260.33
  260.49  260.49   260.5  260.69  260.75  260.76  260.84  260.86  260.89   260.9
  261.19  261.59  261.92  262.45   262.5  262.64  263.15   263.6  264.08  264.78
  265.19  266.07   266.4  267.61   268.1  268.55  269.24  269.47  269.87  270.25
   270.8   272.1  272.47  272.89  273.37     274   274.5   274.8   276.1     277
   276.3   268.2   265.1  261.87  260.61  257.05   255.3  256.08  255.76  254.96
  255.07  255.73  254.38  253.76  250.04  248.75  247.43  246.86  246.71  247.64
  248.02  248.69  253.38  253.21   253.4   253.2   253.4   253.6   253.5  254.07
   254.6   256.1   256.9   257.1  257.65   258.1   258.9   258.9   258.8   258.2
   258.3   259.2  259.28   259.5  259.42   259.5     260   260.5   260.7   261.4
  263.04  265.64   266.6   267.7   268.6  269.84  273.96   274.8   276.1     277
  4607.5  4667.5  4687.5  4712.7  4722.7  4752.7  4767.5  4771.4  4783.7  4814.7
  4821.1  4857.8  4918.4    4944  4987.1  4989.7  4990.2  4994.3  4997.6  5001.9
  5037.8  5037.9  5089.5  5186.8  5236.5  5240.9  5270.9  5280.9  5290.9  5306.4
  5320.9  5350.9  5370.9  5400.9  5406.4  5410.9  5430.9  5456.4  5470.9  5490.9
  5500.9  5520.9  5529.1  5550.9  5559.1  5570.9  5590.9  5600.9  5610.9  5620.9
  5639.1  5669.1  5680.9  5690.9  5700.9  5716.6    5770  5780.9  5810.9  5820.6
   276.3  268.21  265.11  261.88   261.2   260.7  260.81  260.93     261  260.72
  260.19  260.24  259.92  259.99   260.2  260.23  260.23  260.26  260.29  260.33
  260.49  260.49   260.5  260.69  260.75  260.76  260.84  260.86  260.89   260.9
  261.19  261.59  261.92  262.45   262.5  262.64  263.15   263.6  264.08  264.78
  265.19  266.07   266.4  267.61   268.1  268.55  269.24  269.47  269.87  270.25
   270.8   272.1  272.47  272.89  273.37     274   274.5   274.8   276.1     277
  275.09  266.99  263.89  260.66   259.4  255.84  254.09  254.87  254.55  253.75
  253.86  254.52  253.17  252.55  248.83  247.54  246.22  245.65   245.5  246.43
  246.81  247.48  252.17     252  252.19  251.99  252.19  252.39  252.29  252.86
  253.39  254.89  255.69  255.89  256.44  256.89  257.69  257.69  257.59  256.99
  257.09  257.99  258.07  258.29  258.21  258.29  258.79  259.29  259.49  260.19
  261.83  264.43  265.39  266.49  267.39  268.63  272.75  273.59  274.89  275.79
BR Coef= 1 , 0 , 0 ,1.25, 0 ,,,.8,-1,2,0,
WSPro=,,,, 1 ,,,, 0 ,,,, 0 ,,,,-1 ,-1 ,-1 , 0 , 0 , 0 , 0 , 0
Culvert=2,11.5,8,41,.015,.4,1,8,1,247.98,4993.6,247.99,4993.6,Culvert #1  , 0 ,10
Culvert Bottom n=.015
Culvert=2,11.5,8,41,.015,.4,1,8,1,248.15,5002.8,247.07,5002.8,Culvert #2  , 0 ,10
Culvert Bottom n=.015
Culvert=2,11.5,8,41,.015,.4,1,8,1,248.16,5011.9,247.17,5011.9,Culvert #3  , 0 ,10
Culvert Bottom n=.015
Culvert=2,11.5,8,41,.015,.4,1,8,1,248.2,5020.9,247.27,5020.9,Culvert #4  , 0 ,10
Culvert Bottom n=.015
Culvert=2,11.5,8,41,.015,.4,1,8,1,248.2,5029.6,247.3,5029.6,Culvert #5  , 0 ,10
Culvert Bottom n=.015
BR U #Sta/Elev= 156
  4607.5   276.3  4617.5     275  4622.7  274.27  4627.5   273.6  4632.7  272.92
  4637.5   272.3  4642.7  271.59  4652.7  270.22  4662.7  268.86  4667.5   268.2
  4672.7  267.42  4677.5   266.7  4682.7  265.87  4687.5   265.1  4692.7  264.42
  4697.5   263.8  4702.7  263.14  4712.7  261.87  4722.7  260.61  4727.5     260
  4732.7  259.38  4737.5   258.8  4742.7   258.2  4752.7  257.05  4753.7  256.94
  4757.5   256.5  4763.7  255.76  4767.5   255.3  4771.4  256.08  4773.7  256.02
  4783.7  255.76  4793.7   255.5  4803.7  255.24  4813.7  254.99  4814.7  254.96
  4821.1  255.07  4857.8  255.73  4868.7   255.5  4894.2  254.96  4918.4  254.38
    4944  253.76  4944.8  253.69  4968.6  251.64  4987.1  250.04  4989.7  248.75
  4990.2  247.43  4991.9  247.15  4994.3  246.86  4997.6  246.71  5001.9  247.64
  5007.1  247.73    5019  247.84  5037.8  248.02  5037.9  248.69  5067.6  251.39
  5089.5  253.38  5114.6  253.37    5140  253.35  5162.5  253.28  5186.8  253.21
  5209.8   253.3  5236.5   253.4  5240.9   253.2  5250.9   253.3  5260.9   253.4
  5270.9   253.4  5280.9   253.6  5290.9   253.5  5296.4  253.72  5300.9   253.9
  5306.4  254.07  5310.9   254.2  5316.4  254.42  5320.9   254.6  5326.4  254.88
  5336.4  255.38  5346.4  255.88  5350.9   256.1  5356.4  256.32  5360.9   256.5
  5370.9   256.9  5376.4  256.95  5380.9     257  5386.4     257  5390.9     257
  5396.2  257.05  5396.4  257.06  5400.9   257.1  5406.4  257.65  5410.9   258.1
  5416.4  258.32  5420.9   258.5  5426.4  258.72  5430.9   258.9  5436.4   258.9
  5440.9   258.9  5446.4   258.9  5450.9   258.9  5456.4   258.9  5460.9   258.9
  5466.4  258.85  5470.9   258.8  5476.4  258.64  5480.9   258.5  5486.4  258.34
  5490.9   258.2  5496.4  258.26  5499.1  258.28  5500.9   258.3  5509.1  258.71
  5510.9   258.8  5519.1  259.13  5520.9   259.2  5529.1  259.28  5530.9   259.3
  5539.1  259.38  5540.9   259.4  5549.1  259.48  5550.9   259.5  5559.1  259.42
  5560.9   259.4  5569.1  259.48  5570.9   259.5  5579.1  259.71  5589.1  259.96
  5590.9     260  5593.6  260.14  5599.1  260.41  5600.9   260.5  5609.1  260.66
  5610.9   260.7  5619.1  261.27  5620.9   261.4  5629.1  262.14  5630.9   262.3
  5639.1  263.04  5640.9   263.2  5649.1  263.94  5650.9   264.1  5660.9   264.9
  5669.1  265.64  5670.9   265.8  5679.1  266.46  5680.9   266.6  5689.1   267.5
  5690.9   267.7  5699.1  268.44  5700.9   268.6  5709.1  269.26  5710.9   269.4
  5716.6  269.84    5770  273.96  5780.9   274.8  5790.9   275.2  5810.9   276.1
  5820.6     277
BR U #Mann= 7
  4607.5     .14  4944.8    .115  4989.7     .04  5037.9    .155  5396.2    .115
  5593.6     .13  5716.6      .2
BR U Banks=4989.7,5037.9
BR D #Sta/Elev= 156
  4607.5  275.09  4617.5  273.79  4622.7  273.06  4627.5  272.39  4632.7  271.71
  4637.5  271.09  4642.7  270.38  4652.7  269.01  4662.7  267.65  4667.5  266.99
  4672.7  266.21  4677.5  265.49  4682.7  264.66  4687.5  263.89  4692.7  263.21
  4697.5  262.59  4702.7  261.93  4712.7  260.66  4722.7   259.4  4727.5  258.79
  4732.7  258.17  4737.5  257.59  4742.7  256.99  4752.7  255.84  4753.7  255.73
  4757.5  255.29  4763.7  254.55  4767.5  254.09  4771.4  254.87  4773.7  254.81
  4783.7  254.55  4793.7  254.29  4803.7  254.03  4813.7  253.78  4814.7  253.75
  4821.1  253.86  4857.8  254.52  4868.7  254.29  4894.2  253.75  4918.4  253.17
    4944  252.55  4944.8  252.48  4968.6  250.43  4987.1  248.83  4989.7  247.54
  4990.2  246.22  4991.9  245.94  4994.3  245.65  4997.6   245.5  5001.9  246.43
  5007.1  246.52    5019  246.63  5037.8  246.81  5037.9  247.48  5067.6  250.18
  5089.5  252.17  5114.6  252.16    5140  252.14  5162.5  252.07  5186.8     252
  5209.8  252.09  5236.5  252.19  5240.9  251.99  5250.9  252.09  5260.9  252.19
  5270.9  252.19  5280.9  252.39  5290.9  252.29  5296.4  252.51  5300.9  252.69
  5306.4  252.86  5310.9  252.99  5316.4  253.21  5320.9  253.39  5326.4  253.67
  5336.4  254.17  5346.4  254.67  5350.9  254.89  5356.4  255.11  5360.9  255.29
  5370.9  255.69  5376.4  255.74  5380.9  255.79  5386.4  255.79  5390.9  255.79
  5396.2  255.84  5396.4  255.85  5400.9  255.89  5406.4  256.44  5410.9  256.89
  5416.4  257.11  5420.9  257.29  5426.4  257.51  5430.9  257.69  5436.4  257.69
  5440.9  257.69  5446.4  257.69  5450.9  257.69  5456.4  257.69  5460.9  257.69
  5466.4  257.64  5470.9  257.59  5476.4  257.43  5480.9  257.29  5486.4  257.13
  5490.9  256.99  5496.4  257.05  5499.1  257.07  5500.9  257.09  5509.1   257.5
  5510.9  257.59  5519.1  257.92  5520.9  257.99  5529.1  258.07  5530.9  258.09
  5539.1  258.17  5540.9  258.19  5549.1  258.27  5550.9  258.29  5559.1  258.21
  5560.9  258.19  5569.1  258.27  5570.9  258.29  5579.1   258.5  5589.1  258.75
  5590.9  258.79  5593.6  258.93  5599.1   259.2  5600.9  259.29  5609.1  259.45
  5610.9  259.49  5619.1  260.06  5620.9  260.19  5629.1  260.93  5630.9  261.09
  5639.1  261.83  5640.9  261.99  5649.1  262.73  5650.9  262.89  5660.9  263.69
  5669.1  264.43  5670.9  264.59  5679.1  265.25  5680.9  265.39  5689.1  266.29
  5690.9  266.49  5699.1  267.23  5700.9  267.39  5709.1  268.05  5710.9  268.19
  5716.6  268.63    5770  272.75  5780.9  273.59  5790.9  273.99  5810.9  274.89
  5820.6  275.79
BR D #Mann= 7
  4607.5     .14  4944.8    .115  4989.7     .04  5037.9    .155  5396.2    .115
  5593.6     .13  5716.6      .2
BR D Banks=4989.7,5037.9
BC Design=,, 0 ,, 0 ,,,,,,

Type RM Length L Ch R = 1 ,22750.7 ,724.7,724.7,724.7
BEGIN DESCRIPTION:
Downstream Section of Bridge/Culvert/Weir
END DESCRIPTION:
XS GIS Cut Line= 6
      2141262.19        811241.6      2141115.94        811241.6
      2141006.57       811252.01      2140865.94       811278.05
       2140714.9       811330.14      2140089.31       811521.46
#Sta/Elev= 30
  4607.5  273.51  4667.5  265.41  4687.5  262.31  4767.5  252.51  4771.4  253.29
  4814.7  252.17  4857.8  252.94  4944.8   250.9  4987.1  247.25  4989.7  245.96
  4990.2  244.64  4997.6  243.92  5001.9  244.85  5037.8  245.23  5037.9   245.9
  5089.5  250.59  5290.9  250.71  5370.9  254.11  5396.2  254.26  5430.9  256.11
  5470.9  256.01  5490.9  255.41  5520.9  256.41  5570.9  256.71  5593.6  257.35
  5620.9  258.61  5716.6  267.05  5780.9  272.01  5810.9  273.31  5820.6  274.21
#Mann= 7 , 1 , 0
  4607.5     .14       0  4944.8    .115       0  4989.7     .04       0
  5037.9    .155       0  5396.2    .115       0  5593.6     .13       0
  5716.6      .2       0
#XS Ineff= 2 , 0
       0    4979   257.7    5048       0   258.1
Permanent Ineff=
       F       F
Bank Sta=4989.7,5037.9
XS Rating Curve= 0
Exp/Cntr=.5,.3