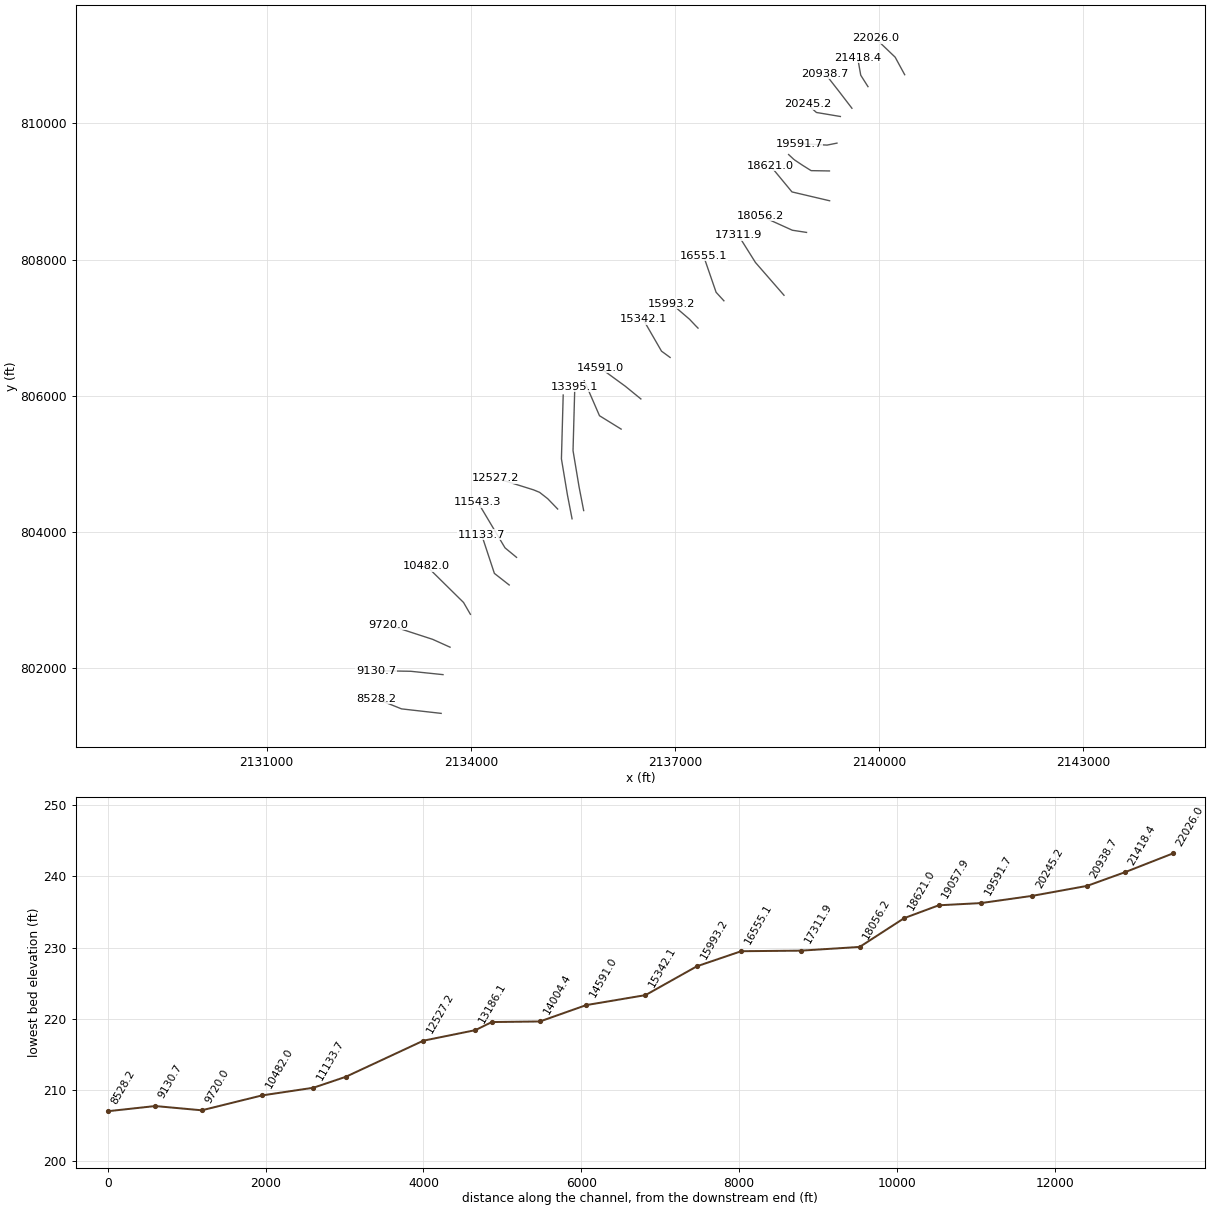
HEC-RAS study NE_Richland_Creek_FINAL.prj: Northeast Richland Creek

--- NE_Richland_Creek_FINAL.g01 (geometry) --- (continued)

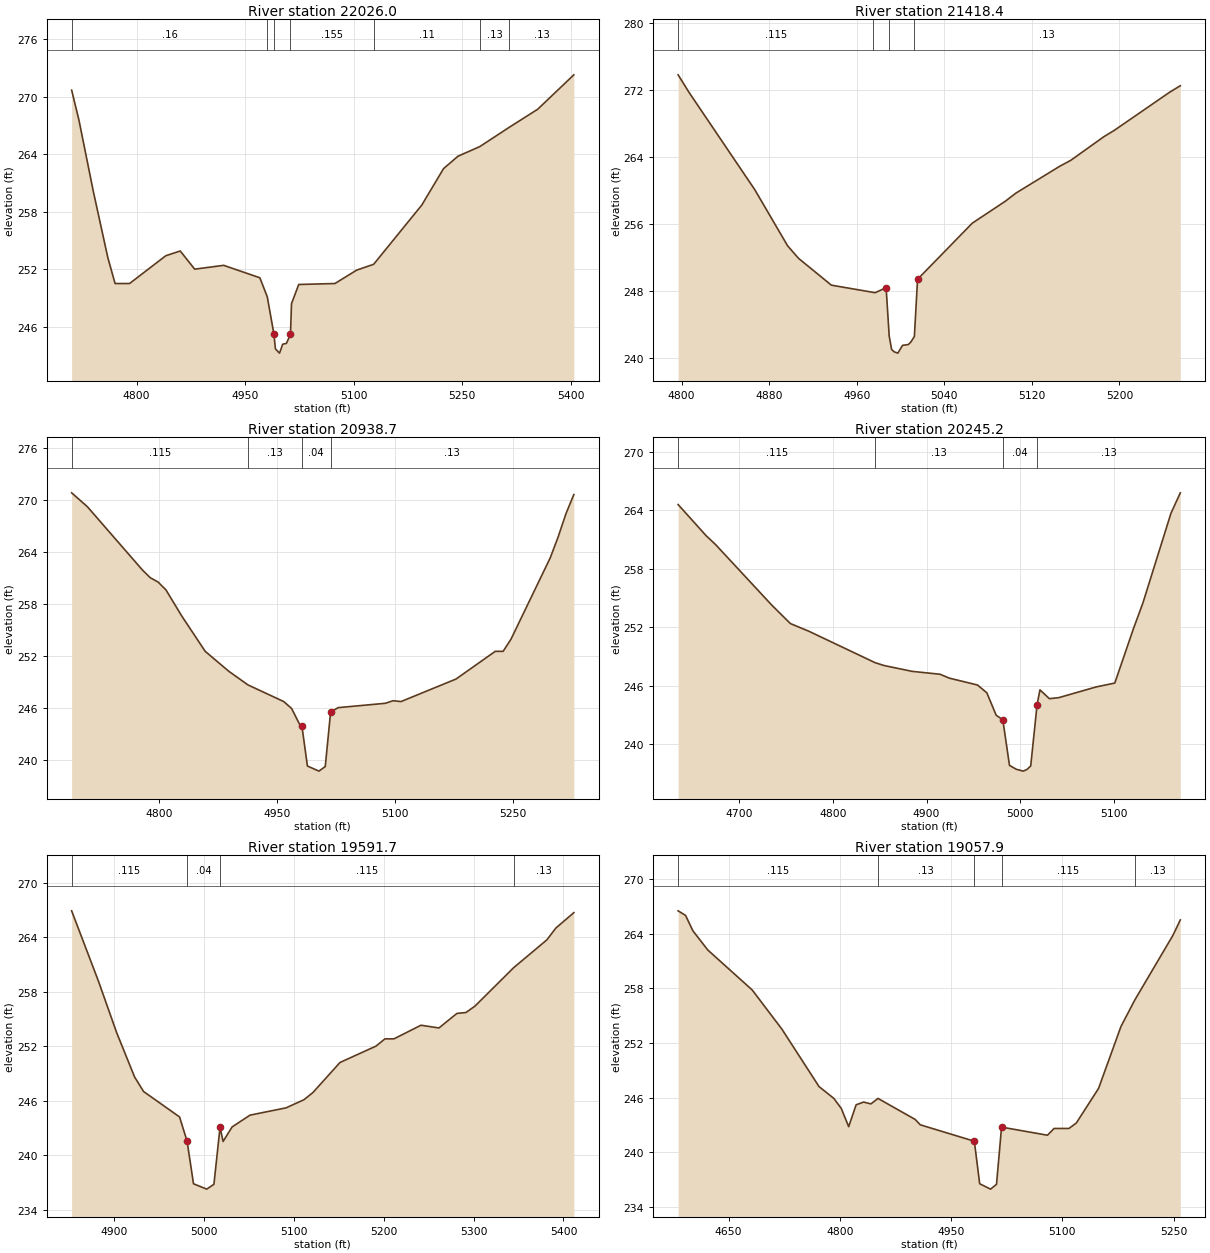
Type RM Length L Ch R = 1 ,22026.0 ,607.6,607.6,607.6
BEGIN DESCRIPTION:
Cross Section Richland Creek 33.0
END DESCRIPTION:
XS GIS Cut Line= 3
      2140374.21       810714.01      2140233.75         810972.
      2139944.36       811248.08
#Sta/Elev= 30
  4710.4   270.7  4720.4   267.6  4740.4   260.1  4760.4   253.2  4770.4   250.5
  4790.4   250.5  4840.4   253.4  4860.4   253.9  4880.4     252  4920.4   252.4
  4970.4   251.1  4980.6  249.12  4989.7  245.27  4991.9  243.67  4997.6  243.23
  5001.9  244.16  5007.1  244.25  5012.7  245.21  5014.1   248.4  5024.1   250.4
  5074.1   250.5  5104.1   251.9  5127.6  252.51  5194.1   258.7  5224.1   262.5
  5244.1   263.8  5274.1   264.8  5314.7  266.81  5354.1   268.7  5404.1   272.3
#Mann= 7 , 1 , 0
  4710.4     .16       0  4980.6    .155       0  4989.7     .04       0
  5012.7    .155       0  5127.6     .11       0  5274.1     .13       0
  5314.7     .13       0
Bank Sta=4989.7,5012.7
XS Rating Curve= 0
Exp/Cntr=.3,.1

Type RM Length L Ch R = 1 ,21418.4 ,479.7,479.7,479.7
BEGIN DESCRIPTION:
Cross Section Richland Creek 32.0
END DESCRIPTION:
XS GIS Cut Line= 3
      2139835.01       810538.68      2139728.54       810706.38
      2139683.07       810962.43
#Sta/Elev= 27
  4796.9   273.8  4806.9   271.7  4866.9   260.1  4896.9   253.4  4906.9   251.9
  4936.9   248.7  4975.1  247.84  4976.9   247.8  4986.9   248.4  4989.7  242.63
  4991.9  241.03  4994.3  240.74  4997.6  240.59  5001.9  241.52  5007.1  241.61
  5009.4   241.9  5012.7  242.57  5015.6   249.4  5065.6   256.1  5095.6   258.7
  5105.6   259.7  5145.6   262.9  5155.6   263.6  5185.6   266.4  5195.6   267.2
  5245.6   271.7  5255.6   272.5
#Mann= 4 , 1 , 0
  4796.9    .115       0  4975.1     .13       0  4989.7     .04       0
  5012.7     .13       0
Bank Sta=4986.9,5015.6
XS Rating Curve= 0
Exp/Cntr=.3,.1

Type RM Length L Ch R = 1 ,20938.7 ,693.5,693.5,693.5
BEGIN DESCRIPTION:
Cross Section Richland Creek 31.0
END DESCRIPTION:
XS GIS Cut Line= 3
        2139599.        810221.5      2139410.83       810466.79
      2139207.51       810726.77
#Sta/Elev= 30
  4688.5   270.8  4708.5   269.2  4778.5   261.9  4788.5     261  4798.5   260.5
  4808.5   259.6  4828.5   256.6  4858.5   252.5  4888.5   250.2    4913  248.62
  4958.5   246.7  4968.5   245.9  4978.5   244.1  4981.5  243.93  4988.6  239.26
  5003.3  238.67  5011.3   239.2  5018.1  245.48  5027.7     246  5087.7   246.5
  5097.7   246.8  5107.7   246.7  5177.7   249.3  5227.7   252.5  5237.7   252.5
  5247.7   253.9  5297.7   263.3  5307.7   265.7  5317.7   268.4  5327.7   270.6
#Mann= 4 , 1 , 0
  4688.5    .115       0    4913     .13       0  4981.5     .04       0
  5018.1     .13       0
Bank Sta=4981.5,5018.1
XS Rating Curve= 0
Exp/Cntr=.3,.1

Type RM Length L Ch R = 1 ,20245.2 ,653.5,653.5,653.5
BEGIN DESCRIPTION:
Cross Section Richland Creek 30.0
END DESCRIPTION:
XS GIS Cut Line= 3
      2139429.39       810100.33       2139077.5        810159.5
       2138943.3       810279.42
#Sta/Elev= 30
  4634.4   264.6  4664.4   261.4  4674.4   260.5  4734.4   254.3  4754.4   252.4
  4774.4   251.6  4844.9  248.39  4854.4   248.1  4884.4   247.5  4914.4   247.2
  4924.4   246.8  4954.4   246.1  4964.4   245.3  4974.4     243  4981.5  242.53
  4988.6  237.86  4995.9  237.46  5003.3  237.27  5007.3  237.44  5011.3   237.8
  5018.1  244.08  5021.2   245.6  5031.2   244.7  5041.2   244.8  5081.2   245.9
  5101.2   246.3  5121.2   251.9  5131.2   254.5  5161.2   263.7  5171.2   265.8
#Mann= 4 , 1 , 0
  4634.4    .115       0  4844.9     .13       0  4981.5     .04       0
  5018.1     .13       0
Bank Sta=4981.5,5018.1
XS Rating Curve= 0
Exp/Cntr=.3,.1

Type RM Length L Ch R = 1 ,19591.7 ,533.8,533.8,533.8
BEGIN DESCRIPTION:
Cross Section Richland Creek 29.0
END DESCRIPTION:
XS GIS Cut Line= 3
      2139379.22       809709.43      2139233.75       809680.33
      2138824.26       809701.66
#Sta/Elev= 30
  4853.1   266.9  4883.1   259.1  4903.1   253.5  4923.1   248.6  4933.1     247
  4973.1   244.2  4981.5  241.51  4988.6  236.84  5003.3  236.25  5011.3  236.78
  5018.1  243.06  5021.5   241.5  5031.5   243.1  5051.5   244.4  5091.5   245.2
  5111.5   246.1  5121.5   246.9  5151.5   250.2  5191.5     252  5201.5   252.8
  5211.5   252.8  5241.5   254.3  5261.5     254  5281.5   255.6  5291.5   255.7
  5301.5   256.4  5344.6  260.64  5381.5   263.7  5391.5     265  5411.5   266.7
#Mann= 4 , 1 , 0
  4853.1    .115       0  4981.5     .04       0  5018.1    .115       0
  5344.6     .13       0
Bank Sta=4981.5,5018.1
XS Rating Curve= 0
Exp/Cntr=.3,.1

Type RM Length L Ch R = 1 ,19057.9 ,436.9,436.9,436.9
BEGIN DESCRIPTION:
Cross Section Richland Creek 28.0-CCX224
END DESCRIPTION:
XS GIS Cut Line= 5
      2139268.79       809300.73      2138999.37       809305.33
      2138874.37       809383.46      2138749.37       809466.79
      2138668.71       809541.59
#Sta/Elev= 30
    4582   266.5    4592     266    4602   264.3    4622   262.2    4682   257.8
    4722   253.5    4772   247.2    4792   245.9    4802   244.8    4812   242.8
    4822   245.2    4832   245.5    4842   245.3  4851.5   245.9  4901.5   243.6
  4908.6     243  4981.4   241.2  4988.6  236.53  5003.3  235.94  5011.3  236.47
  5018.1  242.75    5080  241.86  5088.9   242.6  5108.9   242.6  5118.9   243.2
  5148.9     247  5179.1   253.8  5197.9  256.73  5249.1   263.8  5259.1   265.5
#Mann= 5 , 1 , 0
    4582    .115       0  4851.5     .13       0  4981.4     .04       0
  5018.1    .115       0  5197.9     .13       0
Bank Sta=4981.4,5018.1
XS Rating Curve= 0
Exp/Cntr=.3,.1

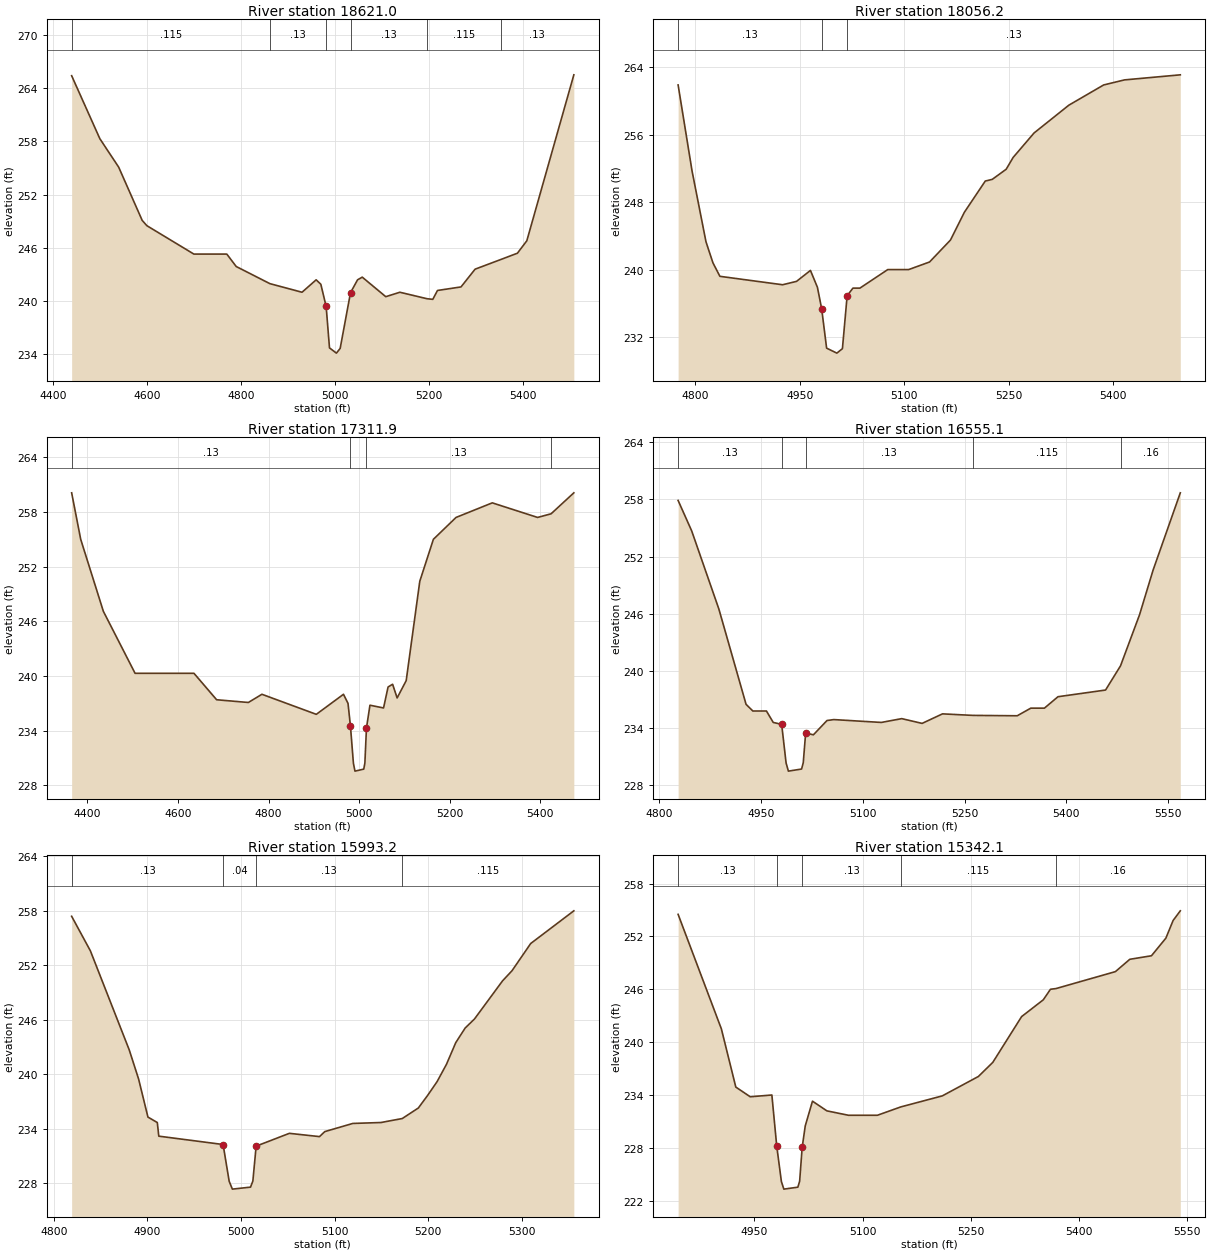
Type RM Length L Ch R = 1 ,18621.0 ,564.8,564.8,564.8
BEGIN DESCRIPTION:
Cross Section Richland Creek 27.0
END DESCRIPTION:
XS GIS Cut Line= 3
      2139271.19        808862.9      2138718.12       808992.83
      2138399.43       809378.07
#Sta/Elev= 30
  4440.2   265.4  4500.2   258.3  4540.2   255.1  4590.2   249.1  4600.2   248.5
  4700.2   245.3  4770.2   245.3  4790.2   243.9  4861.8  241.97  4930.2     241
  4960.2   242.4  4970.2   241.9  4981.5   239.4  4988.6  234.73  5003.3  234.14
  5011.3  234.67  5033.3  240.95  5048.3   242.4  5058.3   242.7  5108.3   240.5
  5138.3     241  5196.1  240.27  5208.3   240.2  5218.3   241.2  5268.3   241.6
  5298.3   243.6  5352.5  244.68  5388.3   245.4  5408.3   246.8  5508.3   265.5
#Mann= 6 , 1 , 0
  4440.2    .115       0  4861.8     .13       0  4981.5     .04       0
  5033.3     .13       0  5196.1    .115       0  5352.5     .13       0
Bank Sta=4981.5,5033.3
XS Rating Curve= 0
Exp/Cntr=.3,.1

Type RM Length L Ch R = 1 ,18056.2 ,744.3,744.3,744.3
BEGIN DESCRIPTION:
Cross Section Richland Creek 26.0
END DESCRIPTION:
XS GIS Cut Line= 3
      2138931.94       808398.24      2138723.33       808430.33
      2138258.87       808640.84
#Sta/Elev= 30
  4775.4   261.9  4795.4   251.7  4815.4   243.3  4825.4   240.8  4835.4   239.2
  4925.4   238.2  4945.4   238.6  4965.4   239.9  4975.4   237.9  4981.5  235.35
  4988.6  230.68  5003.3  230.09  5011.3  230.62  5018.1   236.9  5026.4   237.8
  5036.4   237.8  5076.4     240  5106.4     240  5136.4   240.9  5166.4   243.5
  5186.4   246.8  5216.4   250.5  5226.4   250.7  5246.4   251.9  5256.4   253.3
  5286.4   256.2  5336.4   259.5  5386.4   261.9  5416.4   262.5  5496.4   263.1
#Mann= 3 , 1 , 0
  4775.4     .13       0  4981.5     .04       0  5018.1     .13       0
Bank Sta=4981.5,5018.1
XS Rating Curve= 0
Exp/Cntr=.3,.1

Type RM Length L Ch R = 1 ,17311.9 ,756.8,756.8,756.8
BEGIN DESCRIPTION:
Cross Section Richland Creek 25.0
END DESCRIPTION:
XS GIS Cut Line= 3
      2138601.17       807475.18      2138181.67       807956.38
      2137931.73       808354.43
#Sta/Elev= 30
  4365.5   260.1  4385.5     255  4435.5   247.1  4505.5   240.3  4635.5   240.3
  4685.5   237.4  4755.5   237.1  4785.5     238  4905.5   235.8  4965.5     238
  4975.5     237  4980.9  234.48  4987.4  230.43  4990.8  229.57  5010.2  229.79
  5012.7  230.46  5016.2   234.3  5023.9   236.8  5053.9   236.5  5063.9   238.8
  5073.9   239.1  5083.9   237.6  5103.9   239.5  5133.9   250.4  5163.9     255
  5213.9   257.4  5293.9     259  5393.9   257.4  5423.7   257.8  5473.9   260.1
#Mann= 4 , 1 , 0
  4365.5     .13       0  4980.9     .04       0  5016.2     .13       0
  5423.7    .115       0
Bank Sta=4980.9,5016.2
XS Rating Curve= 0
Exp/Cntr=.3,.1

Type RM Length L Ch R = 1 ,16555.1 ,561.9,561.9,561.9
BEGIN DESCRIPTION:
Cross Section Richland Creek 24.0
END DESCRIPTION:
XS GIS Cut Line= 3
      2137717.83       807394.21      2137603.54       807518.88
      2137417.64       808057.68
#Sta/Elev= 30
  4828.5   257.9  4848.5   254.7  4888.5   246.5  4928.5   236.5  4938.5   235.8
  4958.5   235.8  4968.5   234.6  4980.9   234.4  4987.4  230.35  4990.8  229.49
  5010.2  229.71  5012.7  230.38  5016.2   233.5  5027.6   233.3  5047.6   234.8
  5057.6   234.9  5127.6   234.6  5157.6     235  5187.6   234.5  5217.6   235.5
  5262.1  235.34  5327.6   235.3  5347.6   236.1  5367.6   236.1  5387.6   237.3
  5457.6     238  5479.6  240.54  5507.6   245.9  5527.6   250.6  5567.6   258.7
#Mann= 5 , 1 , 0
  4828.5     .13       0  4980.9     .04       0  5016.2     .13       0
  5262.1    .115       0  5479.6     .16       0
Bank Sta=4980.9,5016.2
XS Rating Curve= 0
Exp/Cntr=.3,.1

Type RM Length L Ch R = 1 ,15993.2 ,651.1,651.1,651.1
BEGIN DESCRIPTION:
Cross Section Richland Creek 23.0-CCX223
END DESCRIPTION:
XS GIS Cut Line= 5
      2137337.81       806992.94      2137301.46       807029.29
      2137212.92       807123.04      2136957.71       807341.79
      2136941.28       807353.21
#Sta/Elev= 30
  4819.1   257.4  4839.1   253.6  4880.6   242.7  4890.6   239.5  4900.6   235.3
  4910.6   234.7  4912.2   233.2  4980.9  232.28  4987.4  228.23  4990.8  227.37
  5010.2  227.59  5012.7  228.26  5016.2   232.1  5051.7  233.51  5083.9  233.15
  5089.5   233.7  5119.5   234.6  5149.5   234.7  5172.3  235.14  5189.5   236.3
  5199.5   237.7  5209.5   239.2  5219.5   241.1  5229.5   243.5  5239.5   245.1
  5249.5   246.1  5279.5   250.3  5289.5   251.4  5309.5   254.4  5355.6     258
#Mann= 4 , 1 , 0
  4819.1     .13       0  4980.9     .04       0  5016.2     .13       0
  5172.3    .115       0
Bank Sta=4980.9,5016.2
XS Rating Curve= 0
Exp/Cntr=.3,.1

Type RM Length L Ch R = 1 ,15342.1 ,751.1,751.1,751.1
BEGIN DESCRIPTION:
Cross Section Richland Creek 22.0
END DESCRIPTION:
XS GIS Cut Line= 3
      2136927.67       806562.14      2136801.46       806654.29
       2136531.3       807121.89
#Sta/Elev= 30
  4844.2   254.5  4904.2   241.5  4924.2   234.9  4944.2   233.8  4974.2     234
  4980.9  228.23  4987.4  224.18  4990.8  223.32  5010.2  223.54  5012.7  224.21
  5016.2  228.05  5020.5   230.5  5030.5   233.3  5050.5   232.2  5080.5   231.7
  5120.5   231.7    5153  232.65  5210.5   233.9  5260.5   236.1  5280.5   237.7
  5320.5   242.9  5350.5   244.8  5360.5     246  5368.2  246.08  5450.5     248
  5470.5   249.4  5500.5   249.8  5520.5   251.8  5530.5   253.8  5540.5   254.9
#Mann= 5 , 1 , 0
  4844.2     .13       0  4980.9     .04       0  5016.2     .13       0
    5153    .115       0  5368.2     .16       0
Bank Sta=4980.9,5016.2
XS Rating Curve= 0
Exp/Cntr=.3,.1

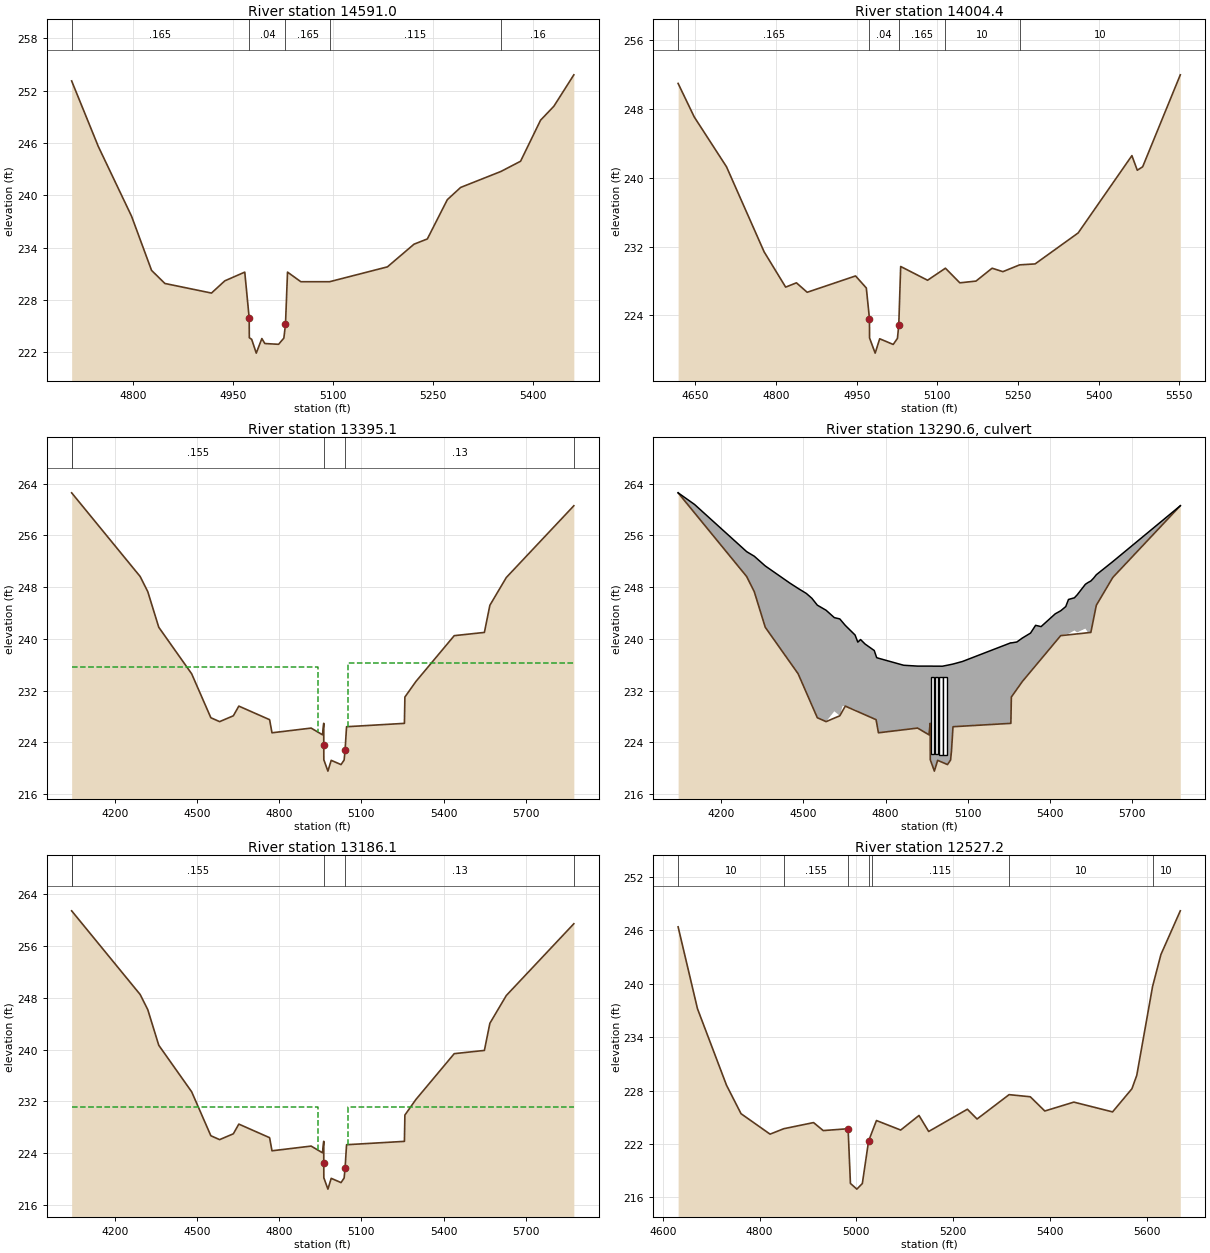
Type RM Length L Ch R = 1 ,14591.0 ,586.6,586.6,586.6
BEGIN DESCRIPTION:
Cross Section Richland Creek 21.0
END DESCRIPTION:
XS GIS Cut Line= 3
      2136498.24       805952.87      2136270.21       806138.67
      2135898.45       806409.68
#Sta/Elev= 30
  4707.2   253.1  4747.2   245.6  4797.2   237.6  4827.2   231.4  4847.2   229.9
  4917.2   228.8  4937.2   230.2  4967.2   231.2 4973.82  225.94 4974.03  223.68
  4977.6   223.5 4984.46  221.92 4992.86  223.59 4997.34  223.02 5017.99  222.93
  5025.9  223.64 5028.35  225.21  5031.4   231.2  5051.4   230.1  5094.6   230.1
  5181.4   231.8  5221.4   234.4  5241.4     235  5271.4   239.5  5291.4   240.9
  5351.9  242.73  5381.4   243.9  5411.4   248.6  5431.4   250.2  5461.4   253.8
#Mann= 5 , 1 , 0
  4707.2    .165       0 4973.82     .04       0 5028.35    .165       0
  5094.6    .115       0  5351.9     .16       0
Bank Sta=4973.82,5028.35
XS Rating Curve= 0
Exp/Cntr=.3,.1

Type RM Length L Ch R = 1 ,14004.4 ,609.3,609.3,609.3
BEGIN DESCRIPTION:
Cross Section Richland Creek 20.0
END DESCRIPTION:
XS GIS Cut Line= 3
      2136208.15       805509.96        2135890.       805706.38
        2135667.       806220.07
#Sta/Elev= 30
    4618     251    4648   247.1    4708   241.3    4778   231.4    4818   227.3
    4838   227.8    4858   226.7    4948   228.6    4968   227.2 4973.82  223.64
 4974.03  221.38 4984.46  219.62 4992.86  221.29 5017.99  220.63  5025.9  221.34
 5028.35  222.91  5031.9   229.7  5081.9   228.1  5115.1   229.5  5141.9   227.8
  5171.9     228  5201.9   229.5  5221.9   229.1  5253.2  229.89  5281.9     230
  5361.9   233.6  5461.9   242.6  5471.9   240.9  5481.9   241.3  5551.9     252
#Mann= 5 , 1 , 0
    4618    .165       0 4973.82     .04       0 5028.35    .165       0
  5115.1      10       0  5253.2      10       0
Bank Sta=4973.82,5028.35
XS Rating Curve= 0
Exp/Cntr=.5,.3

Type RM Length L Ch R = 1 ,13395.1 ,209,209,209
BEGIN DESCRIPTION:
Upstream Section of Bridge/Culvert/Weir
END DESCRIPTION:
XS GIS Cut Line= 4
      2135657.57       804313.65      2135589.86       804662.61
      2135501.32       805193.86      2135527.36       806131.36
#Sta/Elev= 30
    4043   262.6    4293  249.65  4320.8   247.3  4360.8   241.8  4480.8   234.6
  4550.8   227.8  4582.8   227.2  4632.8   228.1  4652.8   229.6  4765.1   227.5
  4773.8  225.47  4916.6   226.2    4958  225.16  4962.6  226.94  4962.7  223.56
  4962.9   221.3  4977.8  219.54  4989.8  221.21  5025.7  220.55    5037  221.26
  5040.5  222.83  5045.8  226.41  5256.9  226.93  5258.6     231  5298.6   233.4
  5438.6   240.5  5548.6     241  5568.6   245.2  5628.6   249.5  5874.9   260.6
#Mann= 5 , 1 , 0
    4043      .2       0    4043    .155       0  4962.7    .045       0
  5040.5     .13       0  5874.9      .2       0
#XS Ineff= 2 , 0
       0    4943   235.7    5051       0   236.2
Permanent Ineff=
       F       F
Bank Sta=4962.7,5040.5
XS Rating Curve= 0
Exp/Cntr=.5,.3

Type RM Length L Ch R = 2 ,13290.6 ,,,
BEGIN DESCRIPTION:
CAPITOL BLVD
Structure ID: WK_RLCR1
END DESCRIPTION:
Bridge Culvert--1,0,-1,-1, 0
Deck Dist Width WeirC Skew NumUp NumDn MinLoCord MaxHiCord MaxSubmerge Is_Ogee
10,189,3,0, 60, 60, , , .95, 0, 1,1,,
    4043    4103    4293  4320.8  4360.8  4450.8  4480.8  4510.8  4530.8  4550.8
  4582.8  4612.8  4632.8  4642.8  4652.8  4688.5  4698.5  4708.5  4725.1  4758.5
  4765.1  4767.3  4773.8  4865.9  4916.6    4958  4962.6  4962.7  4962.9    4968
  4974.7  4977.8  4989.8  4996.2  5006.5  5025.7    5037  5040.5  5045.8  5079.8
  5256.9  5258.6  5278.6  5298.6  5328.6    5347    5367  5418.6  5438.6    5457
    5467  5488.6  5498.6  5528.6  5538.6  5548.6  5558.6  5568.6  5628.6  5874.9
   262.6   260.8   253.5  252.79  251.29  248.63  247.81  247.03  246.29  245.22
  244.43  243.29  243.09  242.59  242.09   240.6   239.5   239.9   239.2   238.2
  237.37   237.1  237.01  235.92  235.79  235.79  235.79  235.79  235.79  235.79
  235.78  235.78  235.78  235.78  235.77  235.93  236.03  236.06  236.11   236.5
   239.4  239.38  239.52  240.13   240.9   242.1   241.9  243.88  244.35     245
   246.1  246.36  246.81  248.45  248.73  248.96   249.4  249.93  251.96   260.6
   262.6   259.5  249.65   247.3   241.8     236   234.6   231.1     230   227.8
   227.2   228.8   228.1   229.6   229.6   229.1  228.83  228.53   227.5   227.5
   227.5  226.99  225.47  225.54   226.2  225.16  226.94  223.56   221.3  221.12
  219.58  219.54  221.21  220.64  220.78  220.55  221.26  222.83  226.41  225.79
  226.93     231   231.8   233.4   234.2  235.35   236.9   239.1   240.5   240.7
  240.78   241.3     241   241.6   240.7     241   242.3   245.2   249.5   260.6
    4043    4103    4293  4320.8  4360.8  4450.8  4480.8  4510.8  4530.8  4550.8
  4582.8  4612.8  4632.8  4642.8  4652.8  4688.5  4698.5  4708.5  4725.1  4758.5
  4765.1  4767.3  4773.8  4865.9  4916.6    4958  4962.6  4962.7  4962.9    4968
  4974.7  4977.8  4989.8  4996.2  5006.5  5025.7    5037  5040.5  5045.8  5079.8
  5256.9  5258.6  5278.6  5298.6  5328.6    5347    5367  5418.6  5438.6    5457
    5467  5488.6  5498.6  5528.6  5538.6  5548.6  5558.6  5568.6  5628.6  5874.9
   262.6   260.8   253.5  252.79  251.29  248.63  247.81  247.03  246.29  245.22
  244.43  243.29  243.09  242.59  242.09   240.6   239.5   239.9   239.2   238.2
  237.37   237.1  237.01  235.92  235.79  235.79  235.79  235.79  235.79  235.79
  235.78  235.78  235.78  235.78  235.77  235.93  236.03  236.06  236.11   236.5
   239.4  239.38  239.52  240.13   240.9   242.1   241.9  243.88  244.35     245
   246.1  246.36  246.81  248.45  248.73  248.96   249.4  249.93  251.96   260.6
  261.45  258.35   248.5  246.15  240.65  234.85  233.45  229.95  228.85  226.65
  226.05  227.65  226.95  228.45  228.45  227.95  227.68  227.38  226.35  226.35
  226.35  225.84  224.32  224.39  225.05  224.01  225.79  222.41  220.15  219.97
  218.43  218.39  220.06  219.49  219.63   219.4  220.11  221.68  225.26  224.64
  225.78  229.85  230.65  232.25  233.05   234.2  235.75  237.95  239.35  239.55
  239.63  240.15  239.85  240.45  239.55  239.85  241.15  244.05  248.35  259.45
BR Coef= 1 , 0 , 0 ,1.25, 0 ,,,.8,-1,2,0,
WSPro=,,,, 1 ,,,, 0 ,,,, 0 ,,,,-1 ,-1 ,-1 , 0 , 0 , 0 , 0 , 0
Culvert=2,12,13.5,189,.015,.4,1,8,1,222.17,4970.6,220.64,4970.6,Culvert #1  , 0 ,10
Culvert Bottom n=.015
Culvert=2,12,13.5,189,.015,.4,1,8,1,222.14,4985.1,220.68,4985.1,Culvert #2  , 0 ,10
Culvert Bottom n=.015
Culvert=2,12,13.5,189,.015,.4,1,8,1,222.1,5000.8,220.71,5000.8,Culvert #3  , 0 ,10
Culvert Bottom n=.015
Culvert=2,12,13.5,189,.015,.4,1,8,1,222.07,5015.3,220.74,5015.3,Culvert #4  , 0 ,10
Culvert Bottom n=.015
BR U #Sta/Elev= 30
    4043   262.6    4293  249.65  4320.8   247.3  4360.8   241.8  4480.8   234.6
  4550.8   227.8  4582.8   227.2  4632.8   228.1  4652.8   229.6  4765.1   227.5
  4773.8  225.47  4916.6   226.2    4958  225.16  4962.6  226.94  4962.7  223.56
  4962.9   221.3  4977.8  219.54  4989.8  221.21  5025.7  220.55    5037  221.26
  5040.5  222.83  5045.8  226.41  5256.9  226.93  5258.6     231  5298.6   233.4
  5438.6   240.5  5548.6     241  5568.6   245.2  5628.6   249.5  5874.9   260.6
BR U #Mann= 5
    4043      .2    4043    .155  4962.7    .045  5040.5     .13  5874.9      .2
BR U Banks=4962.7,5040.5
BR D #Sta/Elev= 30
    4043  261.45    4293   248.5  4320.8  246.15  4360.8  240.65  4480.8  233.45
  4550.8  226.65  4582.8  226.05  4632.8  226.95  4652.8  228.45  4765.1  226.35
  4773.8  224.32  4916.6  225.05    4958  224.01  4962.6  225.79  4962.7  222.41
  4962.9  220.15  4977.8  218.39  4989.8  220.06  5025.7   219.4    5037  220.11
  5040.5  221.68  5045.8  225.26  5256.9  225.78  5258.6  229.85  5298.6  232.25
  5438.6  239.35  5548.6  239.85  5568.6  244.05  5628.6  248.35  5874.9  259.45
BR D #Mann= 5
    4043      .2    4043    .155  4962.7    .045  5040.5     .13  5874.9      .2
BR D Banks=4962.7,5040.5
BC Design=,, 0 ,, 0 ,,,,,,

Type RM Length L Ch R = 1 ,13186.1 ,658.9,658.9,658.9
BEGIN DESCRIPTION:
Downstream Section of Bridge/Culvert/Weir
END DESCRIPTION:
XS GIS Cut Line= 4
      2135487.01       804192.85       2135419.3       804541.81
      2135330.76       805073.06       2135356.8       806010.56
#Sta/Elev= 30
    4043  261.46    4293  248.51  4320.8  246.16  4360.8  240.66  4480.8  233.46
  4550.8  226.66  4582.8  226.06  4632.8  226.96  4652.8  228.46  4765.1  226.36
  4773.8  224.33  4916.6  225.06    4958  224.02  4962.6   225.8  4962.7  222.42
  4962.9  220.16  4977.8   218.4  4989.8  220.07  5025.7  219.41    5037  220.12
  5040.5  221.69  5045.8  225.27  5256.9  225.79  5258.6  229.86  5298.6  232.26
  5438.6  239.36  5548.6  239.86  5568.6  244.06  5628.6  248.36  5874.9  259.46
#Mann= 5 , 1 , 0
    4043      .2       0    4043    .155       0  4962.7    .045       0
  5040.5     .13       0  5874.9      .2       0
#XS Ineff= 2 , 0
       0    4943   231.1    5051       0   231.1
Permanent Ineff=
       F       F
Bank Sta=4962.7,5040.5
XS Rating Curve= 0
Exp/Cntr=.5,.3

Type RM Length L Ch R = 1 ,12527.2 ,983.9,983.9,983.9
BEGIN DESCRIPTION:
Cross Section Richland Creek 19.0-CCX222
END DESCRIPTION:
XS GIS Cut Line= 5
      2135275.38       804336.63      2135129.58       804487.63
      2135009.79       804581.38      2134921.25       804617.83
      2134367.62       804790.84
#Sta/Elev= 30
  4631.6   246.4  4671.6   237.2  4731.6   228.6  4761.6   225.4  4821.6   223.1
    4850  223.71  4911.5   224.4  4931.5   223.5  4982.9  223.71  4987.7  217.56
    5001  216.92  5012.3  217.55  5025.2  222.32  5031.8  223.26  5041.5  224.63
  5091.6  223.56  5129.4   225.2  5149.4   223.4  5229.4   225.9  5249.4   224.8
  5315.6  227.54  5359.4   227.3  5389.4   225.7  5449.4   226.7  5529.4   225.6
  5569.4   228.2  5579.4   229.7  5612.1   239.7  5629.4   243.3  5669.4   248.2
#Mann= 7 , 1 , 0
  4631.6      10       0    4850    .155       0  4982.9    .044       0
  5025.2    .155       0  5031.8    .115       0  5315.6      10       0
  5612.1      10       0
Bank Sta=4982.9,5025.2
XS Rating Curve= 0
Exp/Cntr=.3,.1

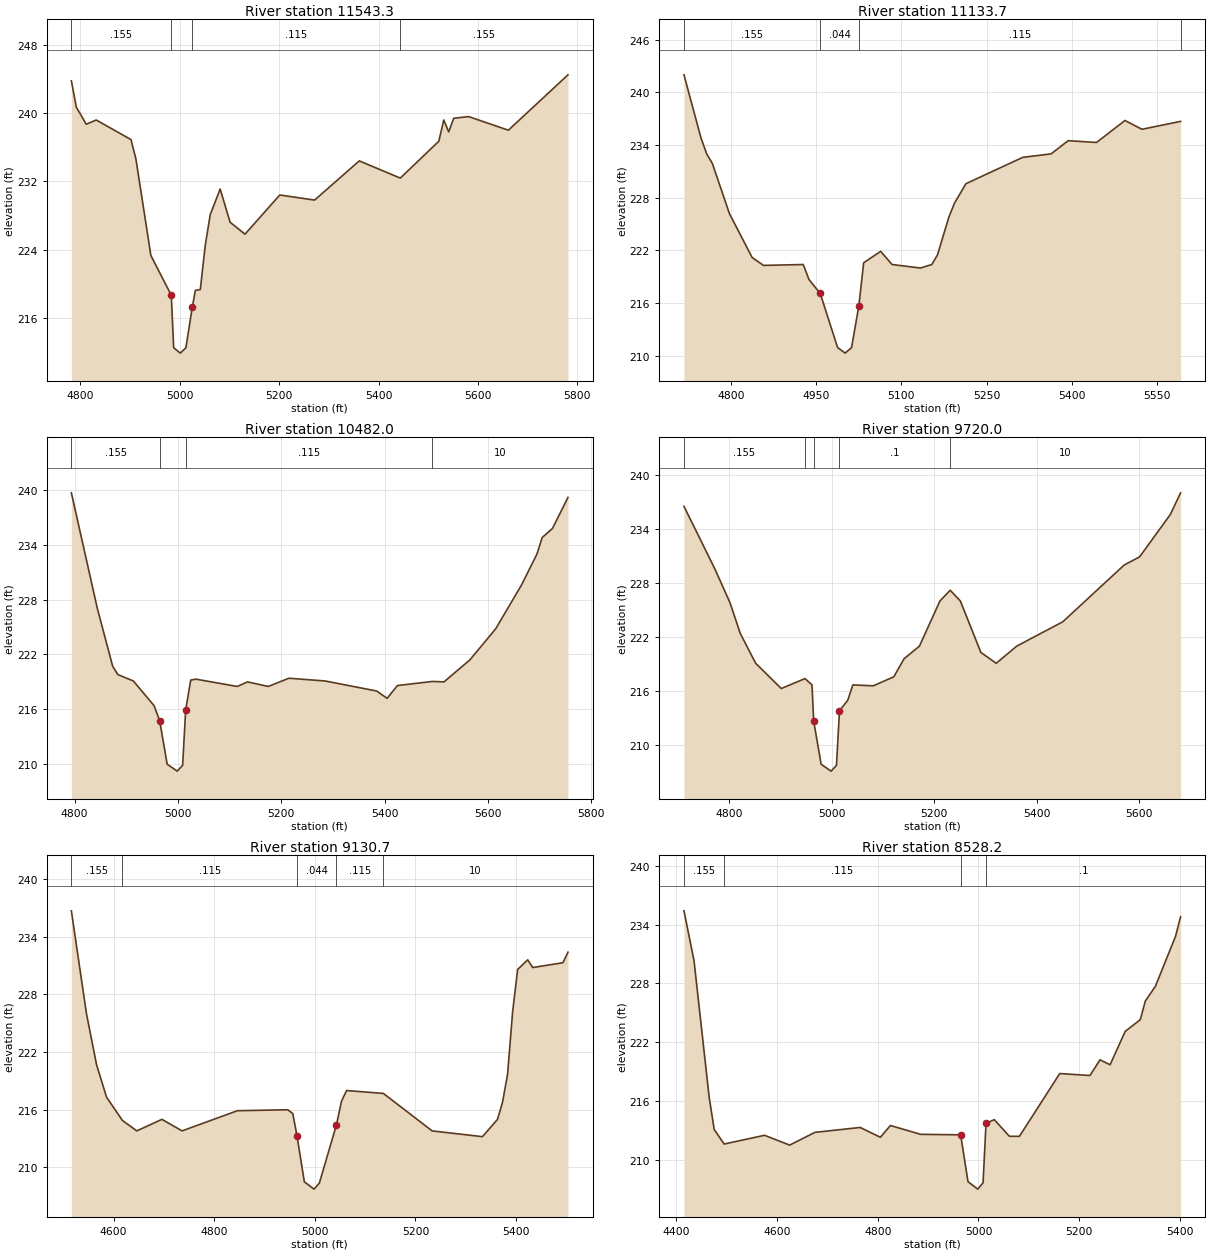
Type RM Length L Ch R = 1 ,11543.3 ,409.6,409.6,409.6
BEGIN DESCRIPTION:
Cross Section Richland Creek 18.0
END DESCRIPTION:
XS GIS Cut Line= 3
      2134671.33       803626.67      2134501.98       803766.27
      2134102.87       804436.46
#Sta/Elev= 30
  4781.8   243.8  4791.8   240.7  4811.8   238.7  4831.8   239.2  4901.8   236.9
  4911.8   234.6  4941.8   223.3  4982.9  218.63  4987.7  212.48    5001  211.84
  5012.3  212.47  5025.2  217.24  5031.3   219.2  5041.3   219.3  5051.3   224.5
  5061.3   228.1  5081.3   231.1  5101.3   227.2  5131.3   225.8  5201.3   230.4
  5271.3   229.8  5361.3   234.4  5443.8  232.38  5521.3   236.7  5531.3   239.2
  5541.3   237.8  5551.3   239.4  5581.3   239.6  5661.3     238  5781.3   244.5
#Mann= 4 , 1 , 0
  4781.8    .155       0  4982.9    .044       0  5025.2    .115       0
  5443.8    .155       0
Bank Sta=4982.9,5025.2
XS Rating Curve= 0
Exp/Cntr=.3,.1

Type RM Length L Ch R = 1 ,11133.7 ,651.7,651.7,651.7
BEGIN DESCRIPTION:
Cross Section Richland Creek 17.0
END DESCRIPTION:
XS GIS Cut Line= 3
      2134563.38       803220.94      2134345.73       803391.27
      2134158.23       803958.98
#Sta/Elev= 30
  4717.3     242  4747.3   234.8  4757.3     233  4767.3   231.9  4797.3   226.2
  4837.3   221.2  4857.3   220.3  4927.3   220.4  4937.3   218.7  4957.2   217.1
  4987.7  210.95    5001  210.31  5012.3  210.94  5025.2  215.71  5033.6   220.6
  5063.6   221.9  5083.6   220.4  5133.6     220  5153.6   220.4  5163.6   221.5
  5183.6   225.8  5193.6   227.4  5213.6   229.6  5313.6   232.6  5363.6     233
  5393.6   234.5  5443.6   234.3  5493.6   236.8  5523.6   235.8  5591.5   236.7
#Mann= 4 , 1 , 0
  4717.3    .155       0  4957.2    .044       0  5025.2    .115       0
  5591.5      .2       0
Bank Sta=4957.2,5025.2
XS Rating Curve= 0
Exp/Cntr=.3,.1

Type RM Length L Ch R = 1 ,10482.0 ,762,762,762
BEGIN DESCRIPTION:
Cross Section Richland Creek 16.0
END DESCRIPTION:
XS GIS Cut Line= 3
      2133993.46        802790.3       2133892.6       802964.19
      2133351.22       803497.55
#Sta/Elev= 30
  4793.8   239.7  4843.8   227.1  4873.8   220.7  4883.8   219.8  4913.8   219.1
  4953.8   216.4  4964.6  214.77  4979.2  209.99  4998.6  209.23  5009.1  209.87
    5015  215.93  5024.8   219.2  5034.8   219.3  5114.8   218.5  5134.8     219
  5174.8   218.5  5214.8   219.4  5284.8   219.1  5384.8     218  5404.8   217.2
  5424.8   218.6  5492.4  219.05  5514.8     219  5564.8   221.4  5614.8   224.8
  5664.8   229.6  5694.8     233  5704.8   234.8  5724.8   235.8  5754.8   239.2
#Mann= 4 , 1 , 0
  4793.8    .155       0  4964.6    .044       0    5015    .115       0
  5492.4      10       0
Bank Sta=4964.6,5015
XS Rating Curve= 0
Exp/Cntr=.3,.1

Type RM Length L Ch R = 1 ,9720.0  ,589.3,589.3,589.3
BEGIN DESCRIPTION:
Cross Section Richland Creek 15.0
END DESCRIPTION:
XS GIS Cut Line= 3
      2133694.61       802307.57      2133439.48       802422.52
      2132783.44       802636.21
#Sta/Elev= 30
  4711.3   236.5  4771.3   229.6  4801.3   225.8  4821.3   222.4  4851.3   219.1
  4901.3   216.3  4947.6   217.4  4961.3   216.7  4964.6  212.68  4979.2   207.9
  4998.6  207.14  5009.1  207.78    5015  213.84  5031.1     215  5041.1   216.7
  5081.1   216.6  5121.1   217.6  5141.1   219.6  5171.1     221  5211.1     226
  5231.2   227.2  5251.1     226  5291.1   220.3  5321.1   219.1  5361.1     221
  5451.1   223.7  5571.1     230  5601.1   230.9  5661.1   235.6  5681.1     238
#Mann= 5 , 1 , 0
  4711.3    .155       0  4947.6    .115       0  4964.6    .044       0
    5015      .1       0  5231.2      10       0
Bank Sta=4964.6,5015
XS Rating Curve= 0
Exp/Cntr=.3,.1

Type RM Length L Ch R = 1 ,9130.7  ,602.5,602.5,602.5
BEGIN DESCRIPTION:
Cross Section Richland Creek 14.0
END DESCRIPTION:
XS GIS Cut Line= 3
      2133590.93       801904.58      2133116.56       801953.77
      2132606.64       801962.27
#Sta/Elev= 30
  4516.2   236.7  4546.2     226  4566.2   220.7  4586.2   217.3  4617.6  214.89
  4646.2   213.8  4696.2     215  4736.2   213.8  4846.2   215.9  4946.2     216
  4956.2   215.6  4964.6  213.28  4979.2   208.5  4998.6  207.74  5009.1  208.38
    5043  214.44  5053.1   216.9  5063.1     218  5136.2   217.7  5233.1   213.8
  5333.1   213.2  5363.1     215  5373.1   216.8  5383.1   219.7  5393.1   226.2
  5403.1   230.6  5423.1   231.6  5433.1   230.8  5493.1   231.3  5503.1   232.4
#Mann= 5 , 1 , 0
  4516.2    .155       0  4617.6    .115       0  4964.6    .044       0
    5043    .115       0  5136.2      10       0
Bank Sta=4964.6,5043
XS Rating Curve= 0
Exp/Cntr=.3,.1

Type RM Length L Ch R = 1 ,8528.2  ,586.8,586.8,586.8
BEGIN DESCRIPTION:
Cross Section Richland Creek 13.0
END DESCRIPTION:
XS GIS Cut Line= 3
      2133563.69       801335.67      2132981.15       801401.69
      2132609.97       801550.85
#Sta/Elev= 30
  4415.1   235.4  4435.1   230.3  4465.1   216.4  4475.1   213.1  4494.9  211.61
  4575.1   212.5  4625.1   211.5  4675.1   212.8  4765.1   213.3  4805.1   212.3
  4825.1   213.5  4885.1   212.6  4964.6  212.55  4979.2  207.77  4998.6  207.01
  5009.1  207.65    5015  213.71  5031.4   214.1  5061.4   212.4  5081.4   212.4
  5161.4   218.8  5221.4   218.6  5241.4   220.2  5261.4   219.7  5291.4   223.1
  5321.4   224.3  5331.4   226.2  5351.4   227.7  5391.4   232.8  5401.4   234.8
#Mann= 4 , 1 , 0
  4415.1    .155       0  4494.9    .115       0  4964.6    .045       0
    5015      .1       0
Bank Sta=4964.6,5015
XS Rating Curve= 0
Exp/Cntr=.3,.1