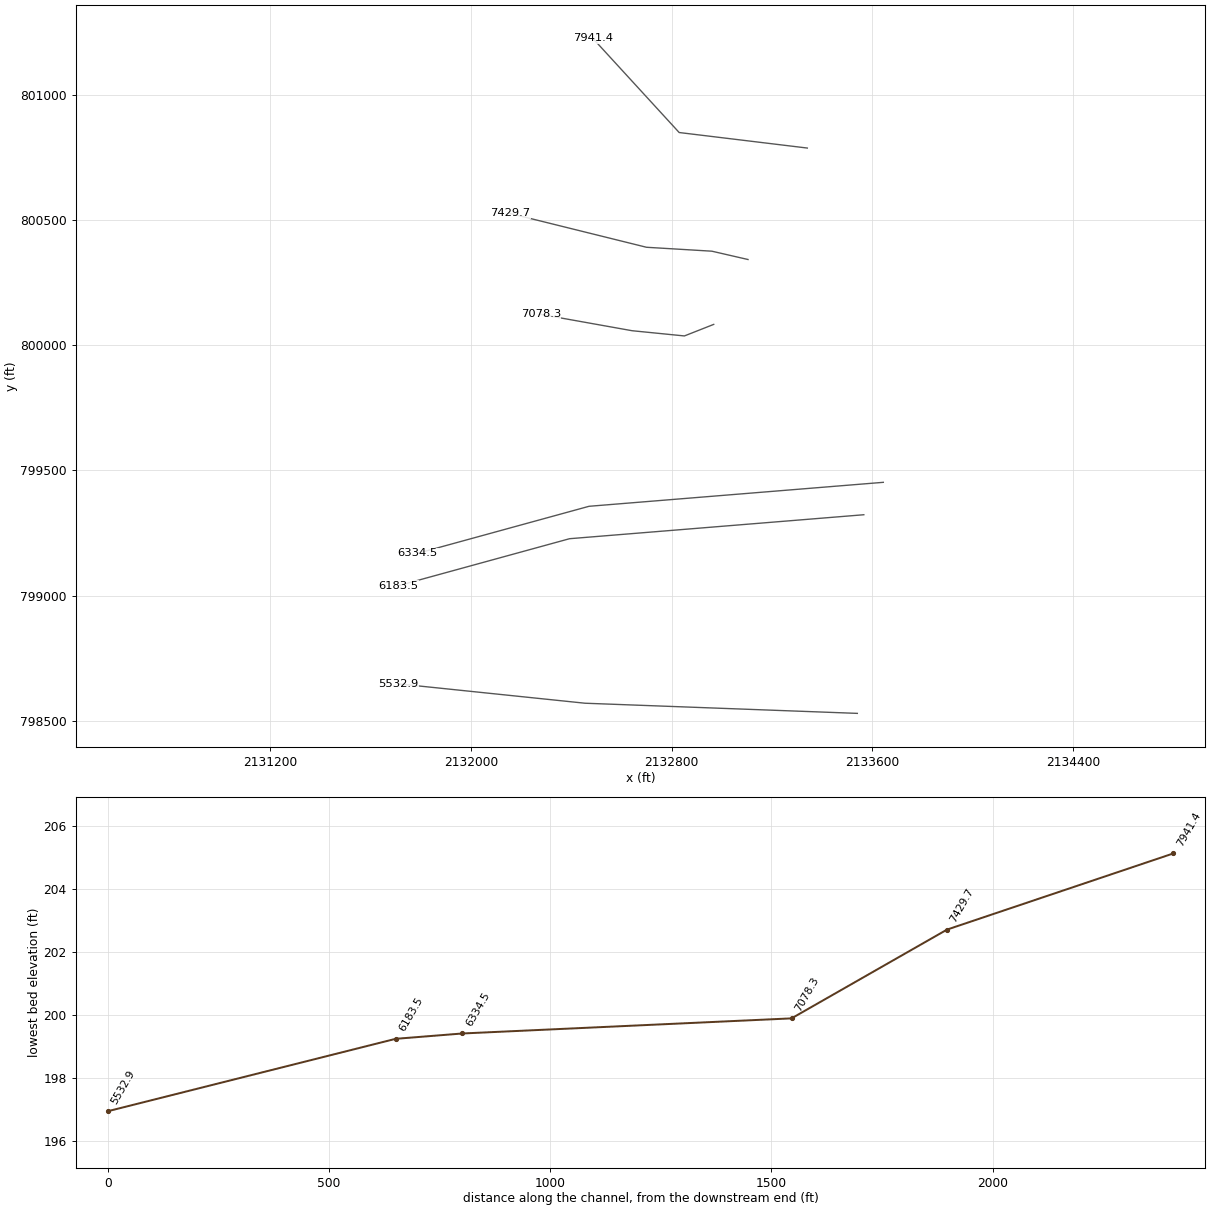
HEC-RAS study NE_Richland_Creek_FINAL.prj: Northeast Richland Creek

--- NE_Richland_Creek_FINAL.g01 (geometry) --- (continued)

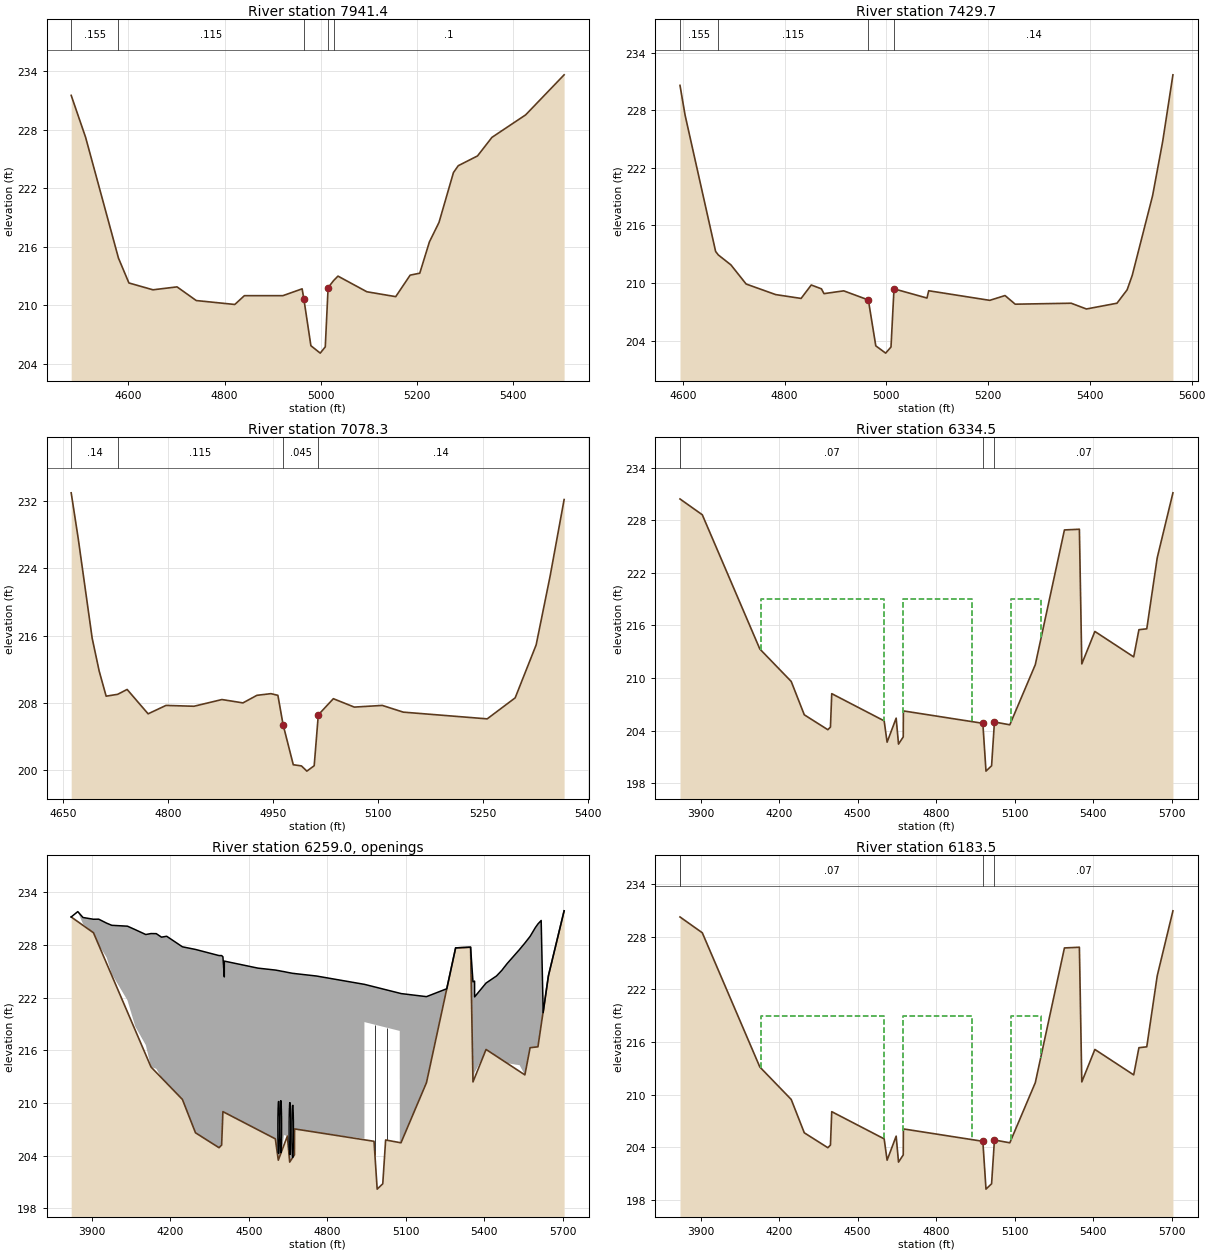
Type RM Length L Ch R = 1 ,7941.4  ,511.7,511.7,511.7
BEGIN DESCRIPTION:
Cross Section Richland Creek 12.0
END DESCRIPTION:
XS GIS Cut Line= 3
      2133340.92       800787.58       2132830.1       800849.61
       2132485.9       801225.84
#Sta/Elev= 30
    4481   231.5    4511   227.2  4579.3  214.84    4601   212.3    4651   211.6
    4701   211.9    4741   210.5    4821   210.1    4841     211    4921     211
    4961   211.7  4964.6  210.66  4979.2  205.88  4998.6  205.12  5009.1  205.76
    5015  211.82  5026.5  212.55  5035.5     213  5095.5   211.4  5155.5   210.9
  5185.5   213.1  5205.5   213.3  5225.5   216.5  5245.5   218.5  5275.5   223.6
  5285.5   224.3  5325.5   225.3  5355.5   227.2  5425.5   229.5  5505.5   233.6
#Mann= 5 , 1 , 0
    4481    .155       0  4579.3    .115       0  4964.6    .045       0
    5015     .14       0  5026.5      .1       0
Bank Sta=4964.6,5015
XS Rating Curve= 0
Exp/Cntr=.3,.1

Type RM Length L Ch R = 1 ,7429.7  ,351.4,351.4,351.4
BEGIN DESCRIPTION:
Cross Section Richland Creek 11.0-CCX220
END DESCRIPTION:
XS GIS Cut Line= 4
       2133104.5       800342.38      2132960.31       800375.65
       2132699.9       800391.27      2132156.46       800526.22
#Sta/Elev= 30
  4594.4   230.6  4604.4   227.5  4664.4   213.3  4669.7  212.93  4694.4   211.9
  4724.4   209.9  4782.4   208.8  4832.4   208.4  4852.4   209.8  4872.4   209.4
  4877.4   208.9  4916.2  209.19  4964.6  208.24  4979.2  203.46  4998.6   202.7
  5009.1  203.34    5015   209.4  5079.8  208.44  5083.2   209.2  5203.2   208.2
  5233.2   208.7  5253.2   207.8  5363.2   207.9  5393.2   207.3  5453.2   207.9
  5473.2   209.3  5483.2   210.8  5523.2   219.1  5543.2   224.8  5563.2   231.7
#Mann= 4 , 1 , 0
  4594.4    .155       0  4669.7    .115       0  4964.6    .045       0
    5015     .14       0
Bank Sta=4964.6,5015
XS Rating Curve= 0
Exp/Cntr=.3,.1

Type RM Length L Ch R = 1 ,7078.3  ,743.8,743.8,743.8
BEGIN DESCRIPTION:
Cross Section Richland Creek 10.0
END DESCRIPTION:
XS GIS Cut Line= 4
      2132967.77       800083.23      2132850.94       800037.11
       2132642.6       800057.94      2132278.48       800123.21
#Sta/Elev= 30
  4661.6     233  4671.6   227.6  4691.6   215.7  4701.6   211.8  4711.6   208.8
    4728  209.02  4741.6   209.6  4771.6   206.7  4797.2   207.7  4837.2   207.6
  4877.2   208.4  4907.2     208  4927.2   208.9  4947.2   209.1  4957.2   208.9
  4964.6  205.42  4979.2  200.64  4990.9   200.5  4998.6  199.88  5009.1  200.52
    5015  206.58  5036.5   208.5  5066.5   207.5  5106.5   207.7  5136.5   206.9
  5256.5   206.1  5296.5   208.6  5326.5   214.9  5346.5   223.1  5366.5   232.2
#Mann= 4 , 1 , 0
  4661.6     .14       0    4728    .115       0  4964.6    .045       0
    5015     .14       0
Bank Sta=4964.6,5015
XS Rating Curve= 0
Exp/Cntr=.5,.3

Type RM Length L Ch R = 1 ,6334.5  ,151,151,151
BEGIN DESCRIPTION:
Upstream Section of Bridge/Culvert/Weir
END DESCRIPTION:
XS GIS Cut Line= 3
      2133643.78       799452.41      2132470.83       799356.66
      2131788.51       799169.02
#Sta/Elev= 30
  3820.9  230.42  3906.1  228.62  4126.1  213.32  4246.1  209.62  4296.1  205.82
  4386.1  204.12  4396.1  204.42    4401  208.23  4601.4  205.13  4612.7   202.7
  4647.3  205.44  4656.3  202.48  4674.4   203.3  4674.8  205.95  4675.4  206.26
  4978.7  204.85  4990.7   199.4  5012.1  200.01    5023     205  5081.8  204.68
  5179.2  211.53  5290.6  226.89  5347.8  226.97    5357  211.62    5407  215.32
  5555.4  212.42  5575.4  215.52  5605.4  215.62  5645.4  223.72  5705.4  231.12
#Mann= 4 , 1 , 0
  3820.9      .2       0  3820.9     .07       0  4978.7    .045       0
    5023     .07       0
#XS Ineff= 3 ,-1
    4130    4600     219    4675    4938     219    5086    5200     219
Permanent Ineff=
       F       F       F
Bank Sta=4978.7,5023
XS Rating Curve= 0
Exp/Cntr=.5,.3

Type RM Length L Ch R = 4 ,6259.0  ,,,
BEGIN DESCRIPTION:
NEW FALLS OF THE NEUSE ROAD
Structure ID: WK_RLCRA
END DESCRIPTION:
Bridge Culvert--1,0,-1,-1, 0
Deck Dist Width WeirC Skew NumUp NumDn MinLoCord MaxHiCord MaxSubmerge Is_Ogee
10,131,2.6,0, 60, 60, , , .95, 0, 1,1,,
  3820.9  3846.1  3866.1  3906.1  3926.1  3956.1  3976.1  4036.1  4066.1  4106.1
  4126.1  4146.1  4166.1  4186.1  4246.1  4296.1  4386.1  4396.1    4401  4406.2
 4406.29  4406.4  4534.7  4601.4  4612.7    4628  4634.4  4647.3  4656.3  4668.6
  4674.4  4674.8  4675.4  4758.6    4942  4942.1 5076.99  5077.1  5081.8  5179.2
  5256.8  5290.6  5347.8    5357  5363.1 5363.21    5397    5407    5447    5467
    5487  5535.4  5555.4  5575.4  5595.4  5605.4  5617.7  5625.4  5645.4  5705.4
   231.2  231.81  231.14  230.94  230.95   230.5  230.25  230.15  229.75   229.2
  229.31   229.3   228.9     229   227.8   227.5   226.8   226.8  226.66  224.37
  224.37  226.17  225.37  225.15  225.09     225  224.97  224.89  224.84  224.77
  224.76  224.75  224.75  224.47  223.52  223.52  222.51  222.51  222.47  222.12
  223.02  227.68  227.76  223.81  223.89  222.09  223.31  223.67  224.48  225.11
  225.87  227.51  228.23  228.99  229.99  230.41   230.8   220.3   224.5   231.9
   231.2   231.8   230.4   229.4   227.3   226.6   224.7   221.7   218.7   216.6
   214.1   213.9   211.8     211   210.4   206.6   204.9   205.2  209.01  208.89
  208.88  208.88  205.79  205.91  203.48  204.39  206.34  206.22  203.26  203.28
  204.08  206.73  207.04  205.87  205.92  219.22  218.21   205.5  205.46  212.31
  223.01  227.67  227.75   212.4  213.44  213.46   214.7   216.1   214.4   214.5
   213.1   214.3   213.2   216.3   215.9   216.4   218.3   220.3   224.5   231.9
  3820.9  3846.1  3866.1  3906.1  3926.1  3956.1  3976.1  4036.1  4066.1  4106.1
  4126.1  4146.1  4166.1  4186.1  4246.1  4296.1  4386.1  4396.1    4401  4406.2
 4406.29  4406.4  4534.7  4601.4  4612.7    4628  4634.4  4647.3  4656.3  4668.6
  4674.4  4674.8  4675.4  4758.6    4942  4942.1 5076.99  5077.1  5081.8  5179.2
  5256.8  5290.6  5347.8    5357  5363.1 5363.21    5397    5407    5447    5467
    5487  5535.4  5555.4  5575.4  5595.4  5605.4  5617.7  5625.4  5645.4  5705.4
   231.2  231.81  231.14  230.94  230.95   230.5  230.25  230.15  229.75   229.2
  229.31   229.3   228.9     229   227.8   227.5   226.8   226.8  226.66  224.37
  224.37  226.17  225.37  225.15  225.09     225  224.97  224.89  224.84  224.77
  224.76  224.75  224.75  224.47  223.52  223.52  222.51  222.51  222.47  222.12
  223.02  227.68  227.76  223.81  223.89  222.09  223.31  223.67  224.48  225.11
  225.87  227.51  228.23  228.99  229.99  230.41   230.8   220.3   224.5   231.9
  230.91  231.51  230.11  229.11  227.01  226.31  224.41  221.41  218.41  216.31
  213.81  213.61  211.51  210.71  210.11  206.31  204.61  204.91  208.72   208.6
  208.59  208.59   205.5  205.62  203.19   204.1  206.05  205.93  202.97  202.99
  203.79  206.44  206.75  205.58  205.63  218.93  217.92  205.21  205.17  212.02
  222.72  227.38  227.46  212.11  213.15  213.17  214.41  215.81  214.11  214.21
  212.81  214.01  212.91  216.01  215.61  216.11  218.01  220.01  224.21  231.61
Pier Skew, UpSta & Num, DnSta & Num=  ,4982.1, 2 ,4982.1, 2 , 0 , 0 , 0 ,,
       1       1
  202.34  219.93
       1       1
  202.05  219.64
Pier Skew, UpSta & Num, DnSta & Num=  ,5027.8, 2 ,5027.8, 2 , 0 , 0 , 0 ,,
       1       1
  204.89  219.58
       1       1
   204.6  219.29
BR Coef= 1 , 0 , 0 ,1.25, 0 ,,,.8,-1,2,0,
WSPro=,,,, 1 ,,,, 0 ,,,, 0 ,,,,-1 ,-1 ,-1 , 0 , 0 , 0 , 0 , 0
BR Coef= 1 , 1 , 0 ,1.25, 0 ,,,.8,0,2,0,
WSPro=,,,, 1 ,,,, 0 ,,,, 0 ,,,,-1 ,-1 ,-1 , 0 , 0 , 0 , 0 , 0
Culvert=1,6,,131,.015,.4,1,1,3,204.22,4613.9,203.19,4613.9,Culvert #1  , 0 ,10
Culvert Bottom n=.015
Culvert=1,6,,131,.015,.4,1,1,3,204.29,4622.4,203.75,4622.4,Culvert #2  , 0 ,10
Culvert Bottom n=.015
Culvert=1,6,,131,.015,.4,1,1,3,204.07,4657,203.23,4657,Culvert #3  , 0 ,10
Culvert Bottom n=.015
Culvert=1,6,,131,.015,.4,1,1,3,203.78,4667.8,203.42,4667.8,Culvert #4  , 0 ,10
Culvert Bottom n=.015
BC Mult= 2 ,2820.9,4850.67,2820.9,4850.67
BC Mult= 3 ,4759.23,6705.4,4759.23,6705.4
BR U #Sta/Elev= 30
  3820.9   231.2  3906.1   229.4  4126.1   214.1  4246.1   210.4  4296.1   206.6
  4386.1   204.9  4396.1   205.2    4401  209.01  4601.4  205.91  4612.7  203.48
  4647.3  206.22  4656.3  203.26  4674.4  204.08  4674.8  206.73  4675.4  207.04
  4978.7  205.63  4990.7  200.18  5012.1  200.79    5023  205.78  5081.8  205.46
  5179.2  212.31  5290.6  227.67  5347.8  227.75    5357   212.4    5407   216.1
  5555.4   213.2  5575.4   216.3  5605.4   216.4  5645.4   224.5  5705.4   231.9
BR U #Mann= 4
  3820.9      .2  3820.9     .07  4978.7    .045    5023     .07
BR U Banks=4978.7,5023
BR D #Sta/Elev= 30
  3820.9  230.91  3906.1  229.11  4126.1  213.81  4246.1  210.11  4296.1  206.31
  4386.1  204.61  4396.1  204.91    4401  208.72  4601.4  205.62  4612.7  203.19
  4647.3  205.93  4656.3  202.97  4674.4  203.79  4674.8  206.44  4675.4  206.75
  4978.7  205.34  4990.7  199.89  5012.1   200.5    5023  205.49  5081.8  205.17
  5179.2  212.02  5290.6  227.38  5347.8  227.46    5357  212.11    5407  215.81
  5555.4  212.91  5575.4  216.01  5605.4  216.11  5645.4  224.21  5705.4  231.61
BR D #Mann= 4
  3820.9      .2  3820.9     .07  4978.7    .045    5023     .07
BR D Banks=4978.7,5023
BC Design=,, 0 ,, 0 ,,,,,,

Type RM Length L Ch R = 1 ,6183.5  ,650.6,650.6,650.6
BEGIN DESCRIPTION:
Downstream Section of Bridge/Culvert/Weir
END DESCRIPTION:
XS GIS Cut Line= 3
       2133566.1       799322.93      2132393.15       799227.18
      2131710.82       799039.54
#Sta/Elev= 30
  3820.9  230.25  3906.1  228.45  4126.1  213.15  4246.1  209.45  4296.1  205.65
  4386.1  203.95  4396.1  204.25    4401  208.06  4601.4  204.96  4612.7  202.53
  4647.3  205.27  4656.3  202.31  4674.4  203.13  4674.8  205.78  4675.4  206.09
  4978.7  204.68  4990.7  199.23  5012.1  199.84    5023  204.83  5081.8  204.51
  5179.2  211.36  5290.6  226.72  5347.8   226.8    5357  211.45    5407  215.15
  5555.4  212.25  5575.4  215.35  5605.4  215.45  5645.4  223.55  5705.4  230.95
#Mann= 4 , 1 , 0
  3820.9      .2       0  3820.9     .07       0  4978.7    .045       0
    5023     .07       0
#XS Ineff= 3 ,-1
    4130    4600     219    4675    4938     219    5086    5200     219
Permanent Ineff=
       F       F       F
Bank Sta=4978.7,5023
XS Rating Curve= 0
Exp/Cntr=.5,.3

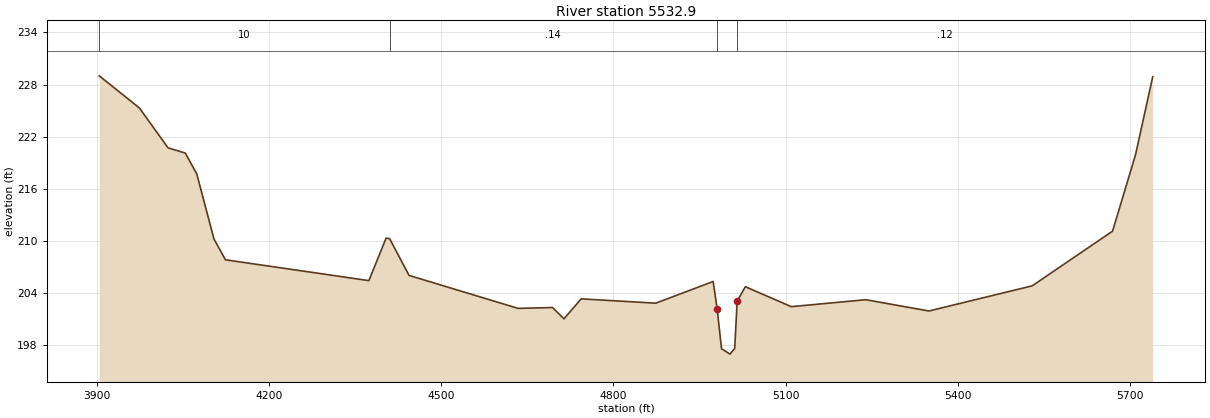
Type RM Length L Ch R = 1 ,5532.9  ,523.9,523.9,523.9
BEGIN DESCRIPTION:
Cross Section Richland Creek 9.0
END DESCRIPTION:
XS GIS Cut Line= 3
      2133540.25        798529.5       2132454.9       798570.04
      2131708.93       798647.66
#Sta/Elev= 30
  3903.9     229  3973.9   225.3  4023.9   220.7  4053.9   220.1  4073.9   217.7
  4103.9   210.2  4123.9   207.8  4373.9   205.4  4403.9   210.3    4410  210.24
  4443.9     206  4633.9   202.2  4693.9   202.3  4713.9     201  4743.9   203.3
  4873.9   202.8  4973.9   205.3  4980.8  202.17  4988.5  197.56  5003.1  196.93
  5011.5  197.59  5015.7  203.04    5030   204.7    5110   202.4    5240   203.2
    5350   201.9    5530   204.8    5670   211.1    5710   219.9    5740   228.9
#Mann= 4 , 1 , 0
  3903.9      10       0    4410     .14       0  4980.8    .045       0
  5015.7     .12       0
Bank Sta=4980.8,5015.7
XS Rating Curve= 0
Exp/Cntr=.3,.1