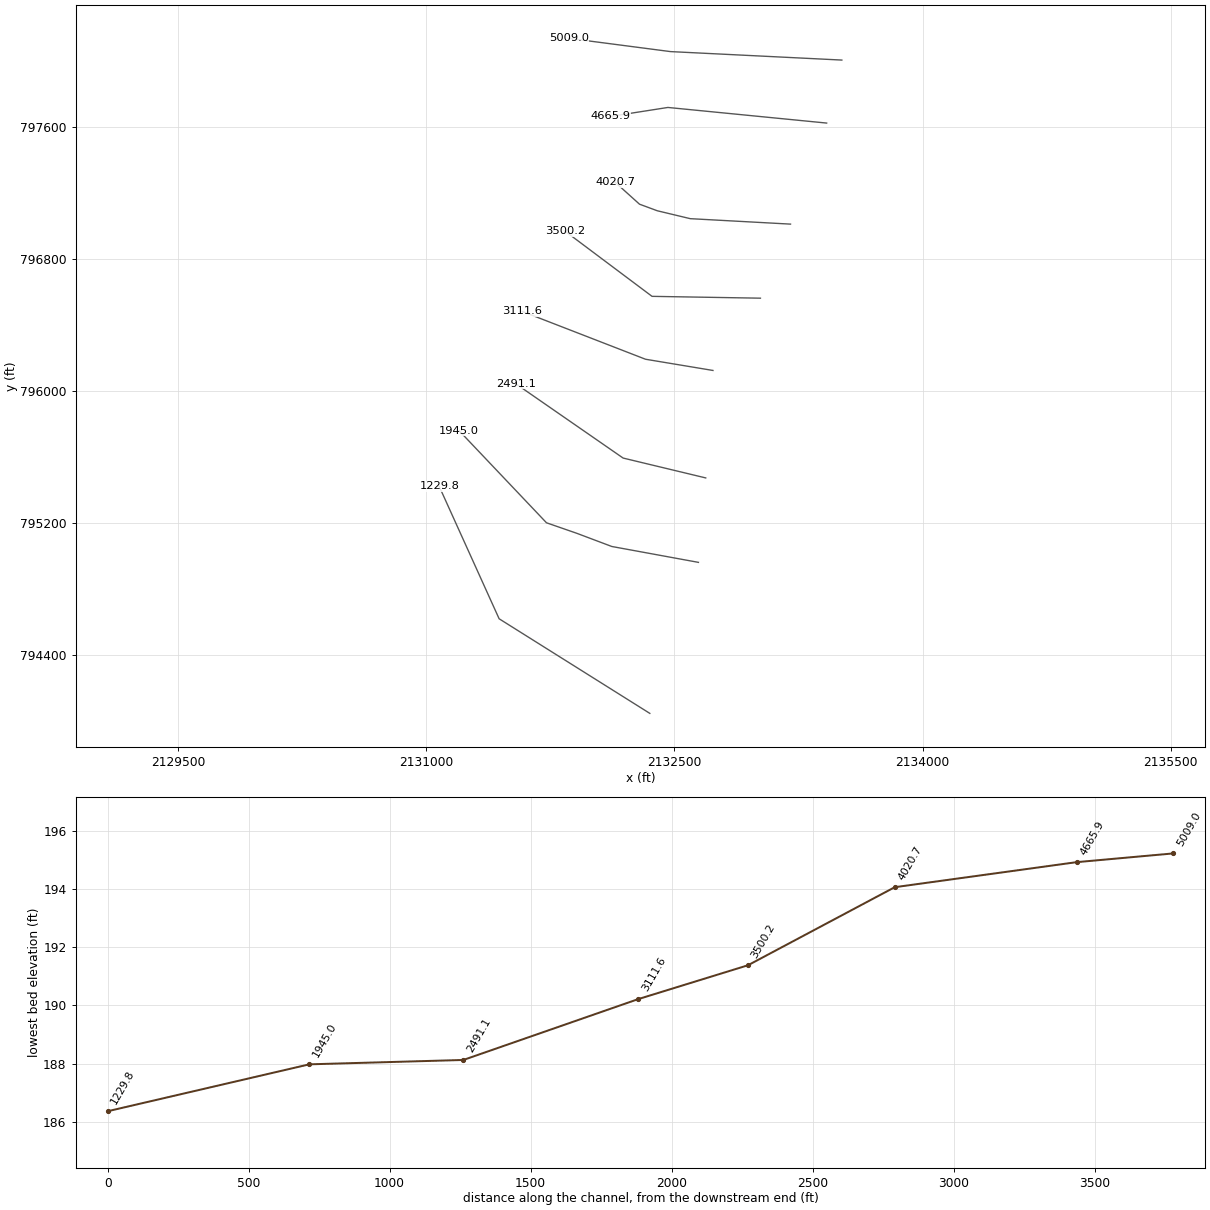
HEC-RAS study NE_Richland_Creek_FINAL.prj: Northeast Richland Creek

--- NE_Richland_Creek_FINAL.g01 (geometry) --- (continued)

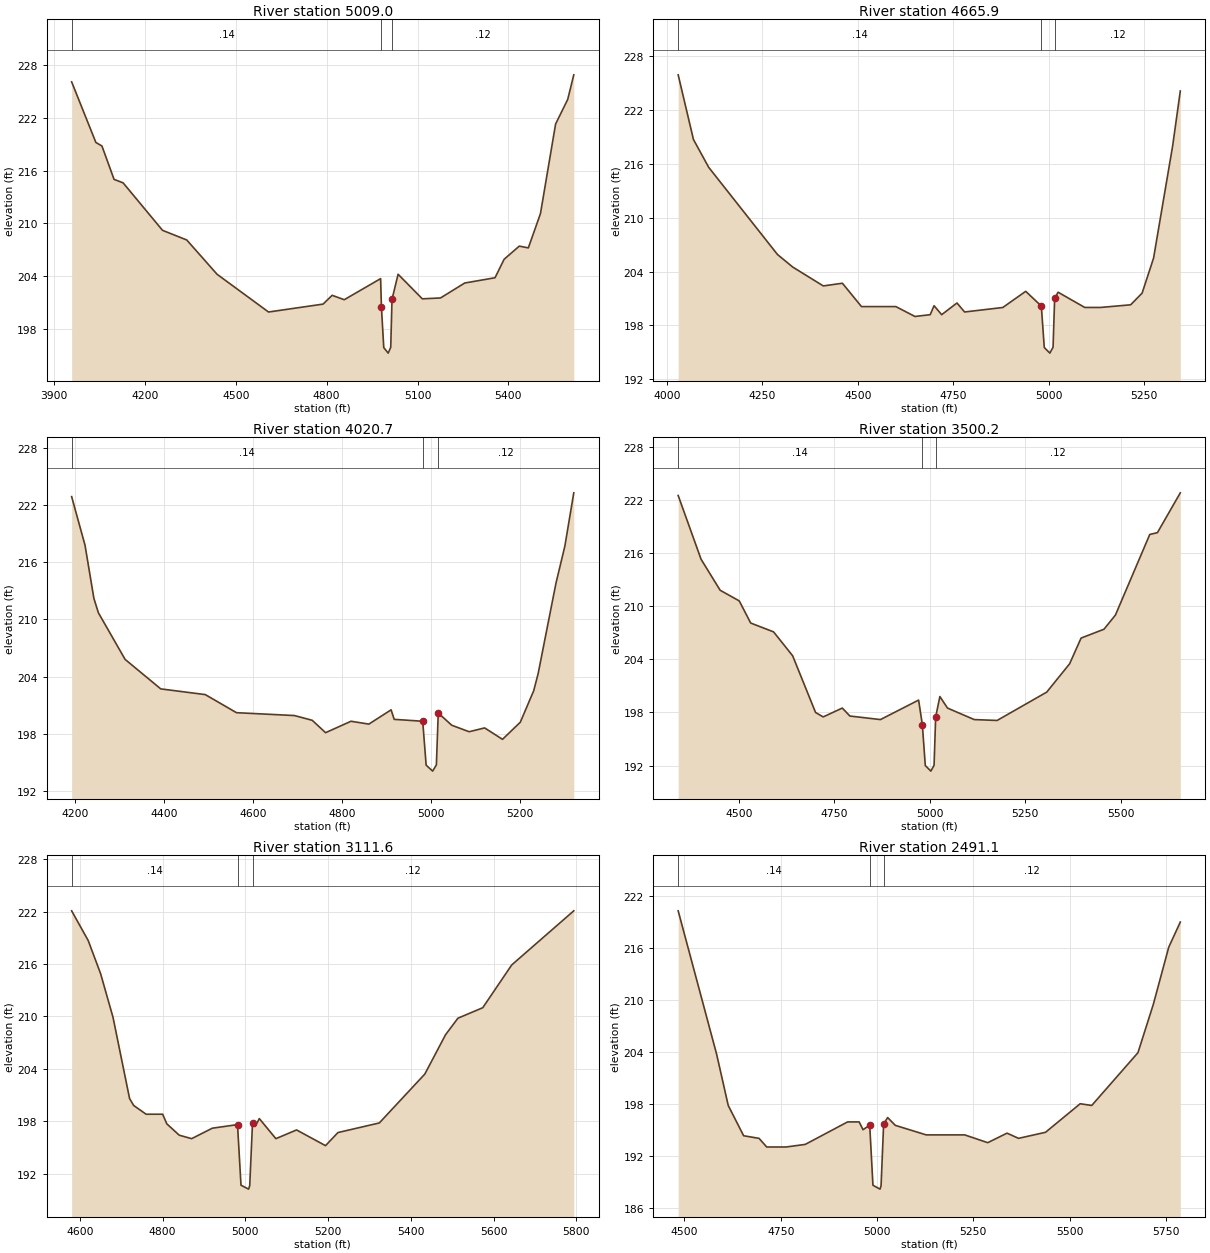
Type RM Length L Ch R = 1 ,5009.0  ,343.1,343.1,343.1
BEGIN DESCRIPTION:
Cross Section Richland Creek 8.0
END DESCRIPTION:
XS GIS Cut Line= 3
      2133512.16       798003.06      2132475.73       798054.41
      2131860.96       798134.78
#Sta/Elev= 30
  3958.1   226.1  4038.1   219.2  4058.1   218.8  4098.1     215  4128.1   214.6
  4258.1   209.2  4338.1   208.1  4438.1   204.2  4608.1   199.9  4788.1   200.8
  4818.1   201.8  4858.1   201.3  4978.1   203.7  4980.8  200.46  4988.5  195.85
  5003.1  195.22  5011.5  195.88  5015.7  201.33  5035.8   204.2  5115.8   201.4
  5175.8   201.5  5255.8   203.2  5355.8   203.8  5385.8   205.9  5435.8   207.4
  5465.8   207.2  5505.8   211.1  5555.8   221.3  5595.8   224.1  5615.8   226.9
#Mann= 3 , 1 , 0
  3958.1     .14       0  4980.8    .045       0  5015.7     .12       0
Bank Sta=4980.8,5015.7
XS Rating Curve= 0
Exp/Cntr=.3,.1

Type RM Length L Ch R = 1 ,4665.9  ,645.2,645.2,645.2
BEGIN DESCRIPTION:
Cross Section Richland Creek 7.0
END DESCRIPTION:
XS GIS Cut Line= 3
      2133420.25       797621.21      2132460.11       797715.87
      2132114.32       797661.71
#Sta/Elev= 30
  4029.9   225.9  4069.9   218.7  4109.9   215.6  4289.9   205.9  4329.9   204.5
  4409.9   202.4  4459.9   202.7  4509.9   200.1  4599.9   200.1  4649.9     199
  4689.9   199.2  4699.9   200.2  4719.9   199.2  4759.9   200.5  4779.9   199.5
  4879.9     200  4939.9   201.8  4980.8  200.16  4988.5  195.55  5003.1  194.92
  5011.5  195.58  5015.7  201.03  5024.7   201.7  5094.7     200  5134.7     200
  5214.7   200.3  5244.7   201.6  5274.7   205.5  5324.7     218  5344.7   224.1
#Mann= 3 , 1 , 0
  4029.9     .14       0  4980.8    .045       0  5015.7     .12       0
Bank Sta=4980.8,5015.7
XS Rating Curve= 0
Exp/Cntr=.3,.1

Type RM Length L Ch R = 1 ,4020.7  ,520.5,520.5,520.5
BEGIN DESCRIPTION:
Cross Section Richland Creek 6.0-CCX219
END DESCRIPTION:
XS GIS Cut Line= 5
      2133201.81       797008.77      2132595.57       797041.79
      2132396.09       797089.66      2132288.37       797129.56
      2132139.94       797263.54
#Sta/Elev= 30
  4192.8   222.9  4222.8   217.8  4242.8   212.2  4252.8   210.7  4312.8   205.8
  4392.8   202.7  4492.8   202.1  4562.8   200.2  4692.8   199.9  4732.8   199.4
  4762.8   198.1  4819.9   199.3  4859.9     199  4909.9   200.5  4916.8   199.5
  4980.8   199.3  4988.5  194.69  5003.1  194.06  5011.5  194.72  5015.7  200.17
    5046  198.88    5085   198.2  5119.9   198.6  5159.9   197.4  5199.9   199.2
  5229.9   202.5  5239.9   204.3  5279.9   213.8  5299.9   217.7  5319.9   223.3
#Mann= 3 , 1 , 0
  4192.8     .14       0  4980.8    .045       0  5015.7     .12       0
Bank Sta=4980.8,5015.7
XS Rating Curve= 0
Exp/Cntr=.3,.1

Type RM Length L Ch R = 1 ,3500.2  ,388.6,388.6,388.6
BEGIN DESCRIPTION:
Cross Section Richland Creek 5.0
END DESCRIPTION:
XS GIS Cut Line= 3
      2133019.76       796559.94      2132364.17       796571.01
      2131836.42       796967.36
#Sta/Elev= 30
    4341   222.5    4401   215.3    4451   211.8    4501   210.6    4531   208.1
    4591   207.1    4641   204.4    4701     198    4721   197.5    4771   198.5
    4791   197.6    4871   197.2    4971   199.4  4980.8  196.62  4988.5  192.01
  5003.1  191.38  5011.5  192.04  5015.7  197.49  5026.7   199.8  5046.7   198.5
  5116.7   197.2  5176.7   197.1  5306.7   200.3  5366.7   203.5  5396.7   206.4
  5456.7   207.4  5486.7     209  5576.7   218.1  5596.7   218.3  5656.7   222.8
#Mann= 3 , 1 , 0
    4341     .14       0  4980.8    .045       0  5015.7     .12       0
Bank Sta=4980.8,5015.7
XS Rating Curve= 0
Exp/Cntr=.3,.1

Type RM Length L Ch R = 1 ,3111.6  ,620.5,620.5,620.5
BEGIN DESCRIPTION:
Cross Section Richland Creek 4.0
END DESCRIPTION:
XS GIS Cut Line= 3
      2132732.68       796121.83      2132324.69       796189.83
      2131579.02       796479.55
#Sta/Elev= 30
  4580.1   222.1  4620.1   218.7  4650.1   214.9  4680.1   209.9  4720.1   200.6
  4730.1   199.8  4760.1   198.8  4800.1   198.8  4810.1   197.7  4840.1   196.4
  4870.1     196  4920.1   197.2    4981  197.61  4989.4  190.67  5007.8  190.22
  5010.5  190.62  5017.2  197.77  5023.7   197.4  5033.7   198.3  5073.7     196
  5123.7     197  5193.7   195.2  5223.7   196.7  5323.7   197.8  5433.7   203.4
  5483.7   207.9  5513.7   209.8  5573.7     211  5643.7   215.9  5793.7   222.1
#Mann= 3 , 1 , 0
  4580.1     .14       0    4981    .045       0  5017.2     .12       0
Bank Sta=4981,5017.2
XS Rating Curve= 0
Exp/Cntr=.3,.1

Type RM Length L Ch R = 1 ,2491.1  ,546.1,546.1,546.1
BEGIN DESCRIPTION:
Cross Section Richland Creek 3.0
END DESCRIPTION:
XS GIS Cut Line= 3
      2132688.94       795470.52      2132189.27       795590.87
      2131540.18       796041.26
#Sta/Elev= 30
  4483.6   220.3  4583.6   203.7  4613.6   197.8  4653.6   194.3  4693.6     194
  4713.6     193  4763.6     193  4813.6   193.3  4923.6   195.9  4953.6   195.9
  4963.6     195    4981  195.52  4989.4  188.58  5007.8  188.13  5010.5  188.53
  5017.2  195.68  5027.6   196.4  5047.6   195.5  5127.6   194.4  5227.6   194.4
  5287.6   193.5  5337.6   194.6  5367.6     194  5437.6   194.7  5527.6     198
  5557.6   197.8  5677.6   203.9  5717.6   209.5  5757.6   216.1  5787.6     219
#Mann= 3 , 1 , 0
  4483.6     .14       0    4981    .045       0  5017.2     .12       0
Bank Sta=4981,5017.2
XS Rating Curve= 0
Exp/Cntr=.3,.1

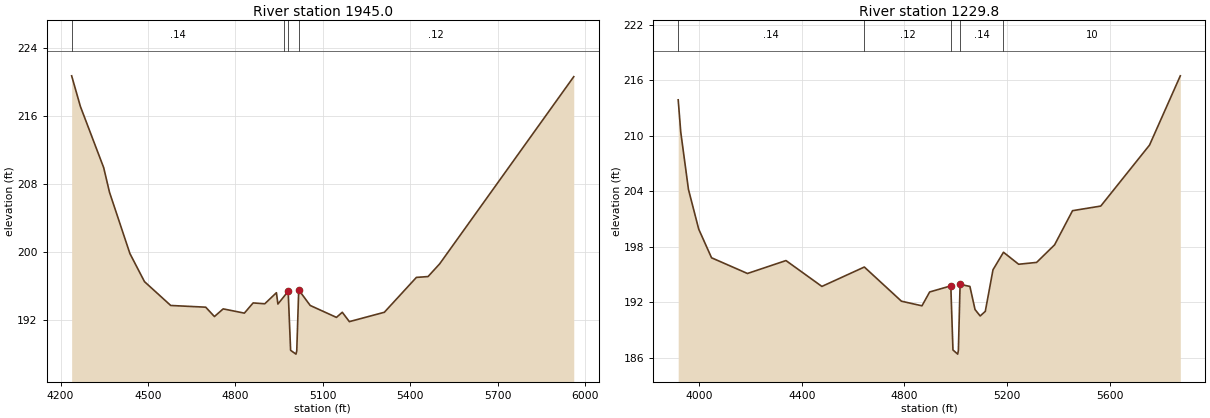
Type RM Length L Ch R = 1 ,1945.0  ,715.2,715.2,715.2
BEGIN DESCRIPTION:
Cross Section Richland Creek 2.0-CCX218
END DESCRIPTION:
XS GIS Cut Line= 5
      2132644.82       794958.73       2132120.8       795054.96
      2131909.36       795134.75      2131725.83       795198.59
      2131196.48       795757.65
#Sta/Elev= 30
    4238   220.7    4268   217.1    4348   209.9    4368     207    4438   199.8
    4488   196.5    4578   193.7    4698   193.5    4728   192.4    4758   193.3
  4830.7   192.8  4860.7     194  4900.7   193.9  4940.7   195.2  4945.8  193.87
  4965.1  194.69    4981  195.37  4989.4  188.43  5007.8  187.98  5010.5  188.38
  5017.2  195.53  5056.7   193.7  5146.7   192.3  5166.7   192.9    5191   191.8
    5311   192.9    5421     197    5461   197.1    5501   198.6    5961   220.6
#Mann= 4 , 1 , 0
    4238     .14       0  4965.1     .12       0    4981    .045       0
  5017.2     .12       0
Bank Sta=4981,5017.2
XS Rating Curve= 0
Exp/Cntr=.3,.1

Type RM Length L Ch R = 1 ,1229.8  ,0,0,0
BEGIN DESCRIPTION:
Cross Section Richland Creek 1.0
END DESCRIPTION:
XS GIS Cut Line= 3
      2132350.68       794043.48      2131439.27       794616.91
      2131077.08       795418.92
#Sta/Elev= 30
  3918.6   213.9  3928.6   210.4  3958.6   204.2  3998.6   199.9  4048.6   196.8
  4188.6   195.1  4338.6   196.5  4478.6   193.7    4644   195.8  4788.6   192.1
  4868.6   191.6  4898.6   193.1    4981  193.76  4989.4  186.82  5007.8  186.37
  5010.5  186.77  5017.2  193.92  5055.4   193.7  5075.4   191.2  5095.4   190.5
  5115.4     191  5145.4   195.5  5186.3   197.4  5245.4   196.1  5315.4   196.3
  5385.4   198.2  5455.4   201.9  5565.4   202.4  5755.4     209  5875.4   216.5
#Mann= 5 , 1 , 0
  3918.6     .14       0    4644     .12       0    4981    .045       0
  5017.2     .14       0  5186.3      10       0
Bank Sta=4981,5017.2
XS Rating Curve= 0
Exp/Cntr=.3,.1

Chan Stop Cuts=-1